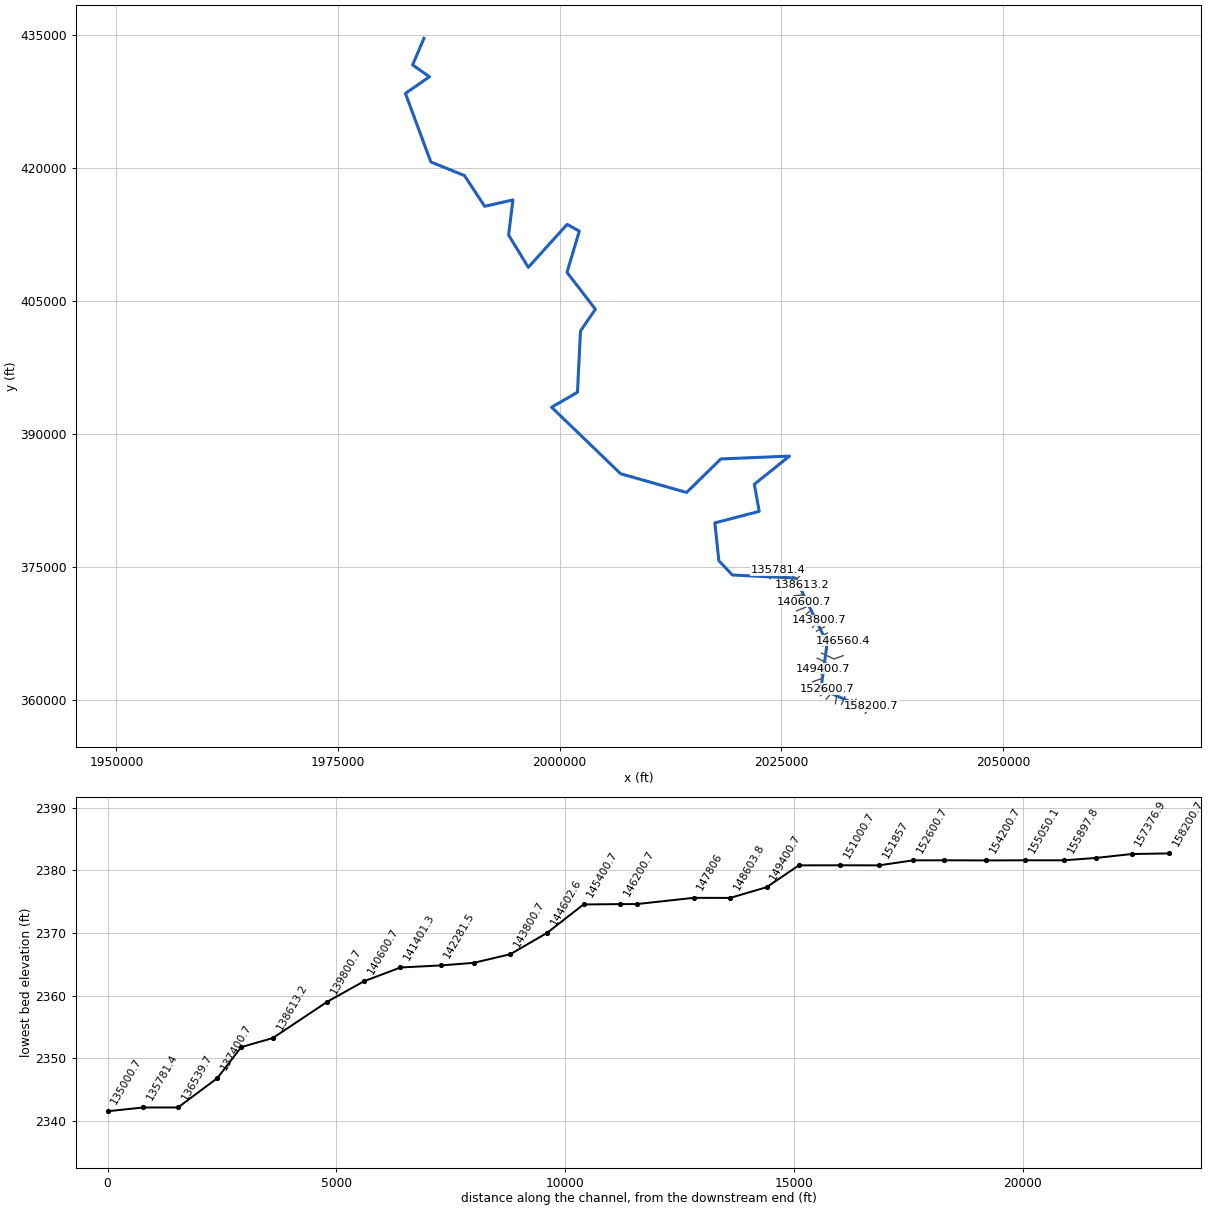
--- MeadowRvr.prj (project) ---

Proj Title=MeadowRvr
Current Plan=p01
Default Exp/Contr=0,0
English Units
Geom File=g01
Flow File=f01
Plan File=p01
BEGIN DESCRIPTION:
END DESCRIPTION:
DSS Export Rating Curves= 0
DSS Export Rating Curve Sorted= 0
DSS Export Volume Flow Curves= 0
DXF OffsetX= 0
DXF OffsetY= 0
DXF ScaleX= 0
DXF ScaleY= 0

--- MeadowRvr.p01 (plan) ---

Plan Title=Floodplain
Program Version=4.00
Geom File=g01
Flow File=f01
K Sum by GR=0
Std Step Tol=0.01
Critical Tol=0.01
Num of Std Step Trials=20
Max Error Tol=0.3
Flow Tol Ratio=0.001
Split Flow NTrial=30
Split Flow Tol=0.02
Split Flow Ratio=0.02
Log Output Level=0
Friction Slope Method=1
Unsteady Friction Slope Method=2
Unsteady Bridges Friction Slope Method=1
Global Log Level=0
CheckData=False
Run HTab=0
Run UNet=0
Run PostProcess=0
UNET Theta=0
UNET Theta Warmup=0
UNET ZTol=0
UNET ZSATol=0
UNET MxIter=0
UNET MaxInSteps=0
UNET DtIC=0
UNET DtMin=0
UNET MaxCRTS=0
UNET WFStab=0
UNET SFStab=0
UNET WFX=0
UNET SFX=0
UNET DSS MLevel=0
UNET DZMax Abort=0
UNET Convert EG Bridges=0
UNET Use Existing IB Tables=0
UNET Froude Limit=0
UNET Froude Power=0
Write IC File=0
Echo Input=False
Echo Output=False
Write Detailed=0

--- MeadowRvr.f01 (steady flow) ---

Flow Title=NFF Regression Equation
Program Version=4.00
Number of Profiles=1
Profile Names=P100yr
River Rch & RM=MeadowRvr,Main      ,158200.7
21015.14
River Rch & RM=MeadowRvr,Main      ,141401.3
22462.74
River Rch & RM=MeadowRvr,Main      ,97400.7
24809.65
River Rch & RM=MeadowRvr,Main      ,50200.7
27558.68
River Rch & RM=MeadowRvr,Main      ,40471.3
30284.05
Boundary for River Rch & Prof#=MeadowRvr,Main      ,1
Up Type=0
Dn Type=3
Dn Slope=0.01193

--- MeadowRvr.g01 (geometry) ---

Geom Title=USGS 3m DEM
Program Version=4.10

River Reach=MeadowRvr       ,Main
Reach XY= 30
     2034833.401      358909.425     2029477.139      361260.264
      2030177.39      366434.664     2026594.451      373769.747
     2019485.287      374112.774      2017962.12      375720.912
     2017508.501      379993.505     2022514.261      381291.296
     2021965.047      384350.823     2025924.131      387528.606
     2018179.266      387204.461     2014320.995      383424.866
     2006875.099      385539.676     1999092.469      393039.073
     2002010.006      394729.838     2002349.655      401639.932
     2004033.322      404100.918     2000829.635       408255.01
     2002217.417      412909.607     2000842.492      413669.128
     1996461.126      408822.585     1994240.833      412466.112
     1994729.596      416430.903      1991542.72      415707.201
     1989261.208       419176.77     1985466.369      420711.547
     1982598.833      428446.418     1985321.002      430324.504
     1983411.445      431655.126      1984686.04      434659.353

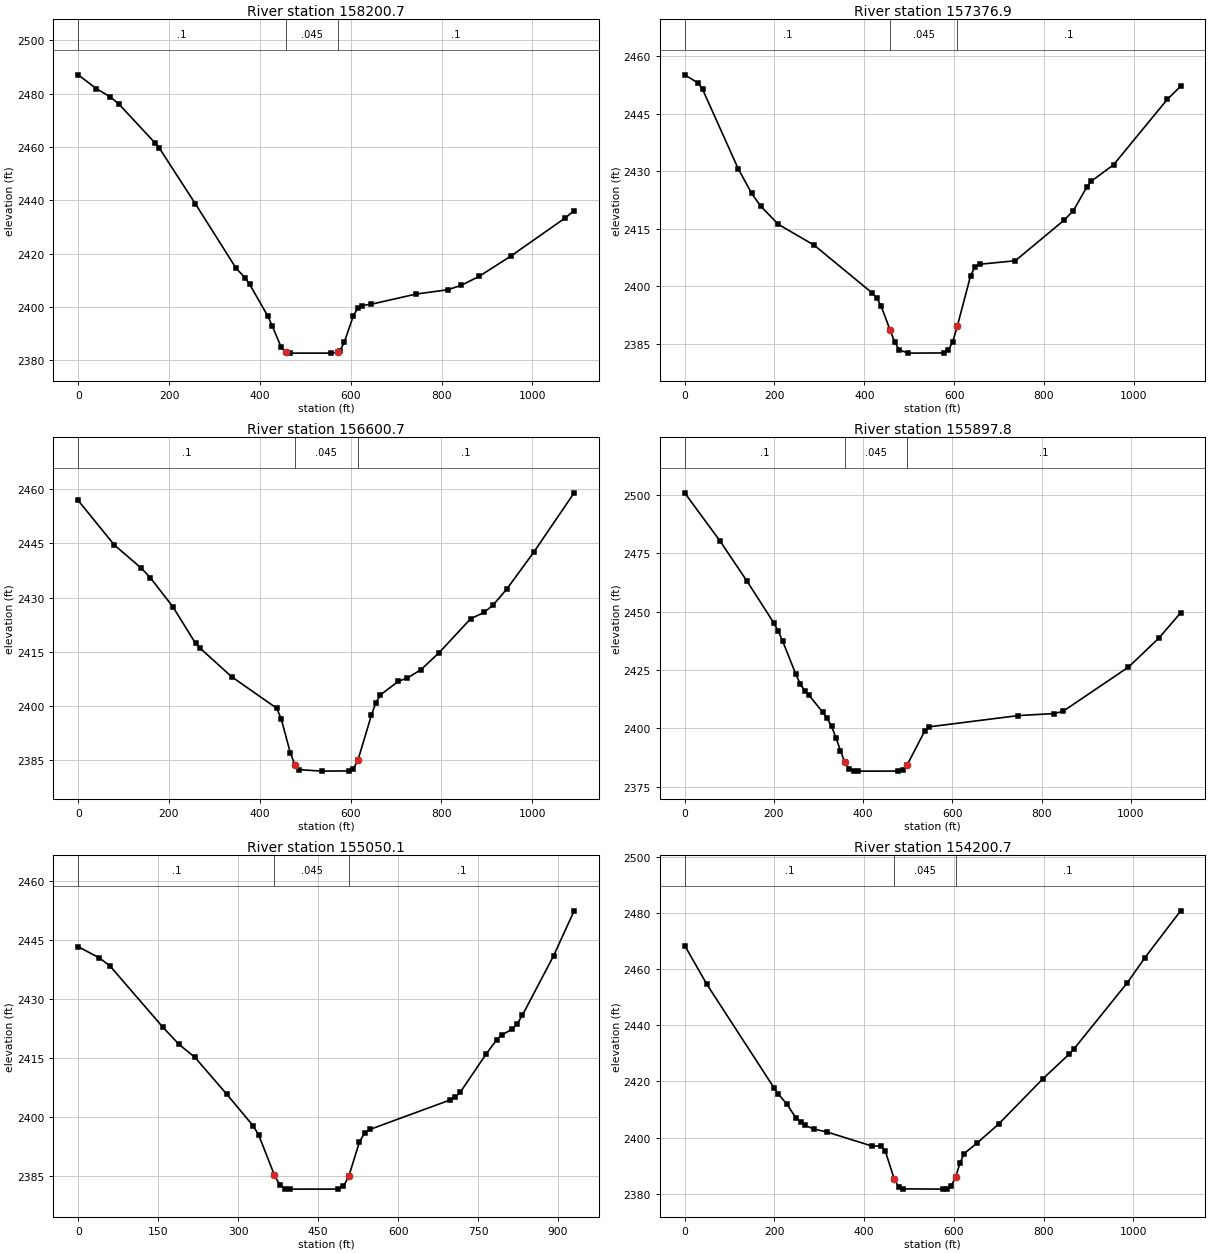
Type RM Length L Ch R = 1 ,158200.7,816.9,823.8,830.7
XS GIS Cut Line= 3
     2034469.446      358502.298     2034825.825      358915.952
     2035182.204      359329.606
#Sta/Elev= 30
       0 2487.12    39.7 2481.95    69.5 2478.97    89.4 2476.18   168.8 2461.64
   178.7  2459.6   258.1  2438.7   347.4 2414.62   367.3 2410.96   377.2 2408.61
     417 2396.74   426.9 2393.04   446.7 2385.04   456.6 2382.97   466.6 2382.72
   555.9 2382.72     571 2383.08   575.8 2383.37   585.7 2386.75   605.6 2396.59
   615.5  2399.6   625.4 2400.58   645.3 2401.07   744.6  2404.9     814  2406.5
   843.8 2408.18   883.5 2411.59     953 2419.17  1072.2 2433.41    1092 2436.17
#Mann= 3 , 0 , 0
       0      .1       0   456.6    .045       0     571      .1       0
Bank Sta=456.6,571
XS Rating Curve= 0 ,0
Exp/Cntr=0.3,0.1

Type RM Length L Ch R = 1 ,157376.9,768.3,776.2,783.8
XS GIS Cut Line= 2
     2033922.746      358848.065     2034356.777      359863.533
#Sta/Elev= 30
       0 2455.16    29.8 2453.04    39.8 2451.39   119.4 2430.64   149.2 2424.24
   169.1 2420.93   208.9 2416.16   288.5 2410.74   417.9 2398.26   427.8 2397.02
   437.8 2394.79   457.6 2388.56   467.6 2385.51   477.6 2383.47   497.4 2382.62
     577 2382.67     587 2383.34   596.9 2385.62   606.9 2389.57   636.7 2402.82
   646.7 2405.16   656.6 2405.78   736.2  2406.7   845.7 2417.36   865.6 2419.78
   895.4 2425.91   905.4 2427.43   955.1 2431.72  1074.5 2448.74  1104.3 2452.18
#Mann= 3 , 0 , 0
       0      .1       0   457.6    .045       0   606.9      .1       0
Bank Sta=457.6,606.9
XS Rating Curve= 0 ,0
Exp/Cntr=0.3,0.1

Type RM Length L Ch R = 1 ,156600.7,713.9,702.8,692
XS GIS Cut Line= 3
     2033361.566      358996.368     2033389.867      359542.487
     2033426.999      360087.072
#Sta/Elev= 30
       0 2456.85    79.5 2444.55   139.2 2438.12   159.1 2435.46   208.8 2427.41
   258.5 2417.34   268.4 2416.02     338 2408.11   437.5 2399.38   447.4  2396.4
   467.3 2387.08   477.2  2383.8   487.2  2382.4   536.9    2382   596.5 2382.06
   606.4 2382.68   616.3 2385.03   646.1 2397.53     656 2400.98     666 2403.09
   705.6 2406.87   725.5 2407.75   755.3 2410.08     795 2414.74   864.4 2424.12
   894.2  2425.9   914.1 2427.94   943.8 2432.28  1003.4  2442.5  1092.7 2458.97
#Mann= 3 , 0 , 0
       0      .1       0   477.2    .045       0   616.3      .1       0
Bank Sta=477.2,616.3
XS Rating Curve= 0 ,0
Exp/Cntr=0.3,0.1

Type RM Length L Ch R = 1 ,155897.8,846.4,847.7,849.1
XS GIS Cut Line= 3
     2032480.939      359079.984     2032927.881      359823.319
     2033003.454       360055.16
#Sta/Elev= 30
       0 2500.84    79.8 2480.03   139.6 2463.02   199.4 2445.19   209.4 2441.72
   219.3 2437.39   249.2 2423.07   259.2 2418.83   269.2 2415.98   279.2 2414.02
   309.1 2406.87     319 2404.27     329 2400.86     339 2395.98   348.9 2390.43
   358.9 2385.41   368.9  2382.5   378.8 2381.67   388.8 2381.62   478.5 2381.64
   488.5 2382.19   498.5 2384.28   538.4 2398.99   548.3 2400.61   747.7 2405.42
   827.5 2406.28   847.4  2407.2   994.2 2426.16  1062.4 2438.58  1111.2 2449.46
#Mann= 3 , 0 , 0
       0      .1       0   358.9    .045       0   498.5      .1       0
Bank Sta=358.9,498.5
XS Rating Curve= 0 ,0
Exp/Cntr=0.3,0.1

Type RM Length L Ch R = 1 ,155050.1,842,849.4,856.8
XS GIS Cut Line= 3
     2031796.359       359529.85     2032137.695      360182.129
     2032167.988      360373.699
#Sta/Elev= 30
       0  2443.2    39.8 2440.34    59.7 2438.29   159.2 2422.68     189 2418.39
   218.9 2415.09   278.6 2405.73   328.3 2397.66   338.2 2395.45   368.1 2385.14
     378 2382.64     388 2381.74   397.9 2381.62   487.5 2381.63   497.4 2382.31
   507.4 2384.88   527.3 2393.56   537.2 2395.91   547.2 2396.79   696.4 2404.21
   706.4 2404.92   716.3  2406.2   765.3 2415.98   784.7 2419.55   794.4 2420.77
   813.8 2422.27   823.5 2423.65   833.2 2425.84   891.4 2440.85   930.1 2452.31
#Mann= 3 , 0 , 0
       0      .1       0   368.1    .045       0   507.4      .1       0
Bank Sta=368.1,507.4
XS Rating Curve= 0 ,0
Exp/Cntr=0.3,0.1

Type RM Length L Ch R = 1 ,154200.7,926.1,914.6,903.2
XS GIS Cut Line= 4
     2031111.777      359597.499     2031195.797      360136.996
     2031223.881      360317.328     2031321.345      360681.061
#Sta/Elev= 30
       0 2468.45    49.6 2454.57   198.6 2417.82   208.5 2415.55   228.3 2411.78
   248.2 2406.91   258.1  2405.4     268 2404.34   287.9 2403.01   317.7 2401.94
     417 2396.98   436.8 2396.94   446.7 2395.33   466.6 2385.35   476.5 2382.51
   486.4  2381.7   574.8  2381.6   584.4 2381.75     594 2382.82   603.6  2385.9
   613.2 2390.76   622.8 2394.29   651.7 2398.04   699.7 2404.82   797.9  2420.9
   857.3 2429.81   867.2 2431.54   986.2 2455.15  1025.8 2464.17  1105.1 2480.82
#Mann= 3 , 0 , 0
       0      .1       0   466.6    .045       0   603.6      .1       0
Bank Sta=466.6,603.6
XS Rating Curve= 0 ,0
Exp/Cntr=0.3,0.1

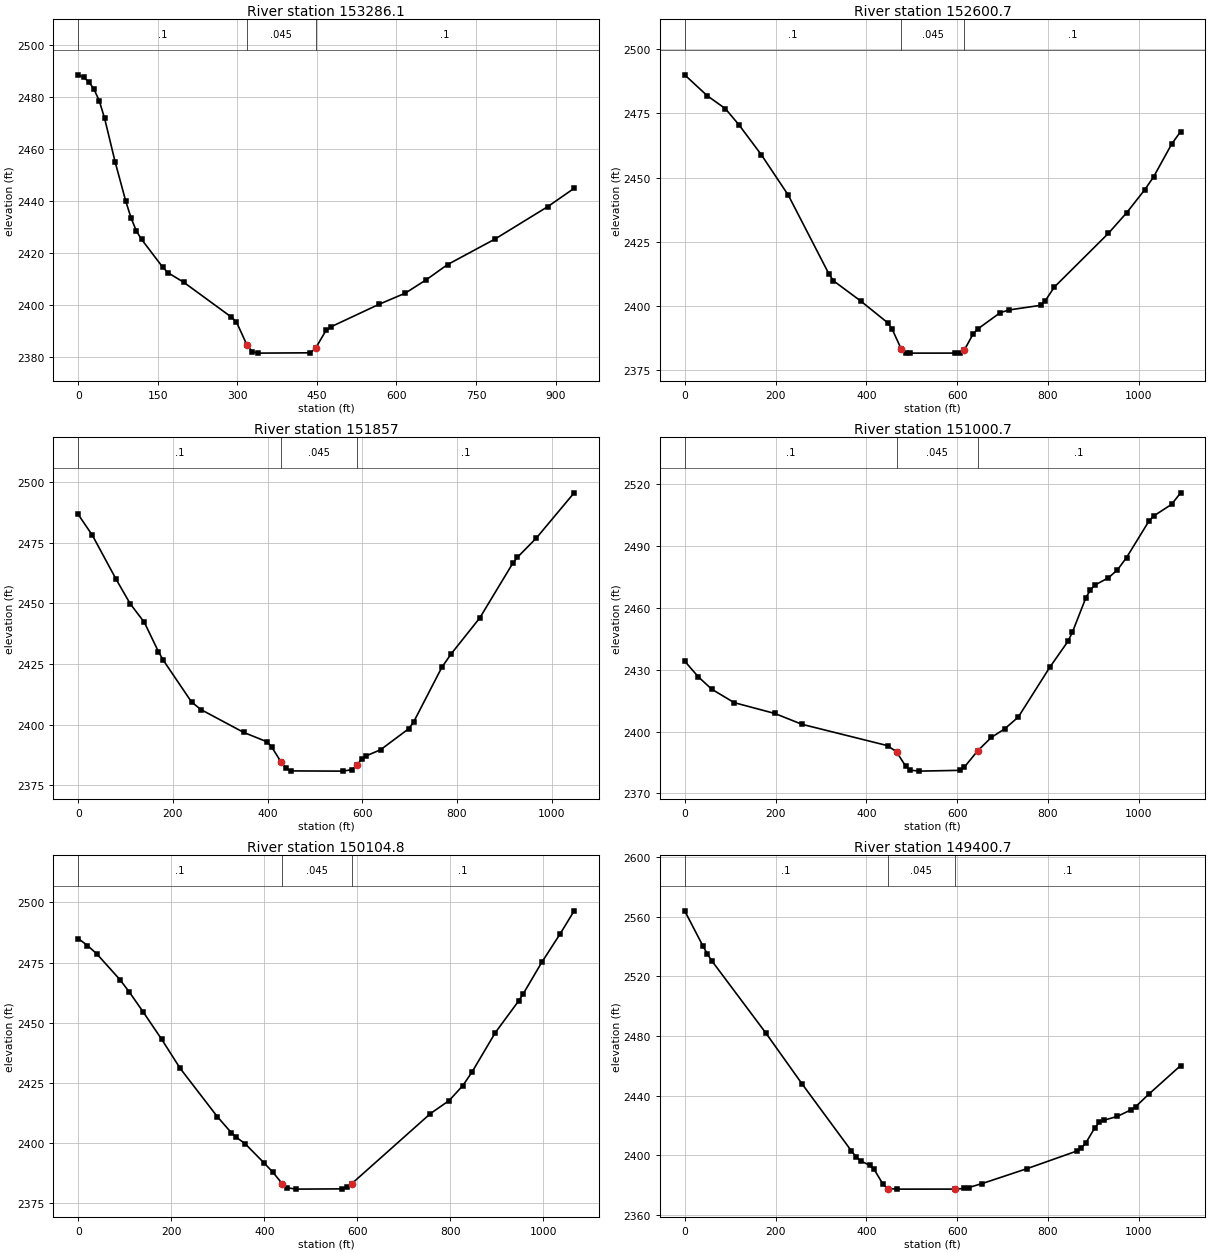
Type RM Length L Ch R = 1 ,153286.1,688.4,685.4,682.3
XS GIS Cut Line= 2
     2030094.691      360105.455     2030669.307      360843.152
#Sta/Elev= 30
       0 2488.56      10 2487.56    19.9 2485.92    29.8 2483.01    39.8 2478.51
    49.7 2471.88    69.6  2455.1    89.5 2440.12    99.5 2433.66   109.4 2428.66
   119.4 2425.34   159.2 2414.68   169.1 2412.53     199 2408.84   288.5 2395.51
   298.4 2393.57   318.3 2384.67   328.3 2382.17   338.2 2381.62   437.7 2381.74
   447.6 2383.53   467.5 2390.43   477.5 2391.82     567 2400.36   616.8 2404.68
   656.6 2409.86   696.3 2415.63   785.9 2425.46   885.4 2437.92   935.1 2444.95
#Mann= 3 , 0 , 0
       0      .1       0   318.3    .045       0   447.6      .1       0
Bank Sta=318.3,447.6
XS Rating Curve= 0 ,0
Exp/Cntr=0.3,0.1

Type RM Length L Ch R = 1 ,152600.7,749.9,743.7,737.5
XS GIS Cut Line= 2
     2029438.572      360493.115     2030219.978      361255.917
#Sta/Elev= 30
       0 2489.99    49.6 2481.86    89.4 2476.84   119.1 2470.61   168.8 2458.86
   228.3 2443.08   317.7 2412.41   327.6 2409.77   387.2 2401.96   446.7 2393.48
   456.6 2391.03   476.5 2383.35   486.4 2381.74   496.4 2381.61   595.6 2381.62
   605.6 2381.74   615.5 2382.72   635.4 2389.17   645.3 2391.01   694.9 2397.38
   714.8 2398.44   784.2 2400.24   794.2 2402.08     814 2407.34   933.2  2428.3
   972.9 2436.22  1012.6 2445.14  1032.4 2450.23  1072.2    2463    1092  2467.9
#Mann= 3 , 0 , 0
       0      .1       0   476.5    .045       0   615.5      .1       0
Bank Sta=476.5,615.5
XS Rating Curve= 0 ,0
Exp/Cntr=0.3,0.1

Type RM Length L Ch R = 1 ,151857  ,859.6,856.3,853.1
XS GIS Cut Line= 2
      2028943.48      361220.342     2029863.476      361721.668
#Sta/Elev= 30
       0 2486.58    29.9 2477.99    79.8 2459.96   109.8 2449.78   139.7 2442.12
   169.6 2429.99   179.6 2426.55   239.5 2409.27   259.4 2406.16   349.2  2396.8
   399.1 2392.87   409.1 2390.64   429.1  2384.4     439 2381.95     449  2380.9
   558.8 2380.81   578.7 2381.42   588.7  2383.3   598.7  2385.7   608.7 2387.14
   638.6  2389.6   698.5 2398.32   708.5 2401.02   768.3 2423.64   788.3 2429.23
   848.2  2443.9     918 2466.45     928 2468.95   967.9 2476.87  1047.7 2495.49
#Mann= 3 , 0 , 0
       0      .1       0   429.1    .045       0   588.7      .1       0
Bank Sta=429.1,588.7
XS Rating Curve= 0 ,0
Exp/Cntr=0.3,0.1

Type RM Length L Ch R = 1 ,151000.7,911,895.9,880.7
XS GIS Cut Line= 3
     2028530.235      362055.238     2029042.308      362244.704
      2029554.38      362434.171
#Sta/Elev= 30
       0 2434.11    29.8 2426.54    59.6  2420.5   109.2 2413.98   198.6 2408.74
   258.1 2403.51   446.7 2393.16   466.6 2390.13   486.4 2383.27   496.4  2381.3
   516.2 2380.82   605.6  2381.2   615.5 2382.69   645.3  2390.7     675 2397.11
   704.8 2401.32   734.6 2407.02   804.1 2431.19   843.8 2443.65   853.8 2448.15
   883.5 2464.87   893.4 2468.62   903.4 2470.96   933.2  2474.5     953 2478.32
   972.9 2484.26  1022.5 2502.03  1032.4 2504.38  1072.2 2510.05    1092 2515.63
#Mann= 3 , 0 , 0
       0      .1       0   466.6    .045       0   645.3      .1       0
Bank Sta=466.6,645.3
XS Rating Curve= 0 ,0
Exp/Cntr=0.3,0.1

Type RM Length L Ch R = 1 ,150104.8,707,704.1,701.3
XS GIS Cut Line= 2
      2028504.79       363274.08     2029517.906      362942.735
#Sta/Elev= 30
       0 2484.99    19.9 2482.09    39.8 2478.64    89.7 2467.89   109.6 2462.82
   139.5 2454.51   179.3 2443.12   219.2    2431   298.9 2410.96   328.7 2404.34
   338.7 2402.51   358.6 2399.71   398.5 2391.87   418.4 2387.85   438.3 2383.09
   448.3 2381.39   468.2 2380.81   567.8 2380.92   577.8 2381.63   587.8 2383.06
   757.1 2412.23     797  2417.6   826.8 2423.88   846.8 2429.62   896.6 2445.92
   946.4 2458.99   956.3 2461.96   996.2 2475.07    1036 2486.99  1065.9 2496.51
#Mann= 3 , 0 , 0
       0      .1       0   438.3    .045       0   587.8      .1       0
Bank Sta=438.3,587.8
XS Rating Curve= 0 ,0
Exp/Cntr=0.3,0.1

Type RM Length L Ch R = 1 ,149400.7,796.9,796.9,796.9
XS GIS Cut Line= 3
     2028762.199      363996.761     2029255.775      363763.312
     2029749.352      363529.864
#Sta/Elev= 30
       0 2564.01    39.7 2540.72    49.6 2535.27    59.6 2530.53   178.7 2482.04
   258.1 2448.06   367.3 2402.88   377.2 2399.03   387.2 2396.32     407 2393.36
     417 2390.61   436.8 2380.55   446.7 2377.74   466.6 2377.32   595.6 2377.34
   615.5 2377.76   625.4 2378.38   655.2 2381.08   754.5 2391.13   863.7  2402.9
   873.6 2405.01   883.5 2408.41   903.4 2418.62   913.3  2422.2   923.2 2423.54
     953 2426.15   982.8 2430.52   992.7 2432.56  1022.5 2441.17    1092  2460.2
#Mann= 3 , 0 , 0
       0      .1       0   446.7    .045       0   595.6      .1       0
Bank Sta=446.7,595.6
XS Rating Curve= 0 ,0
Exp/Cntr=0.3,0.1

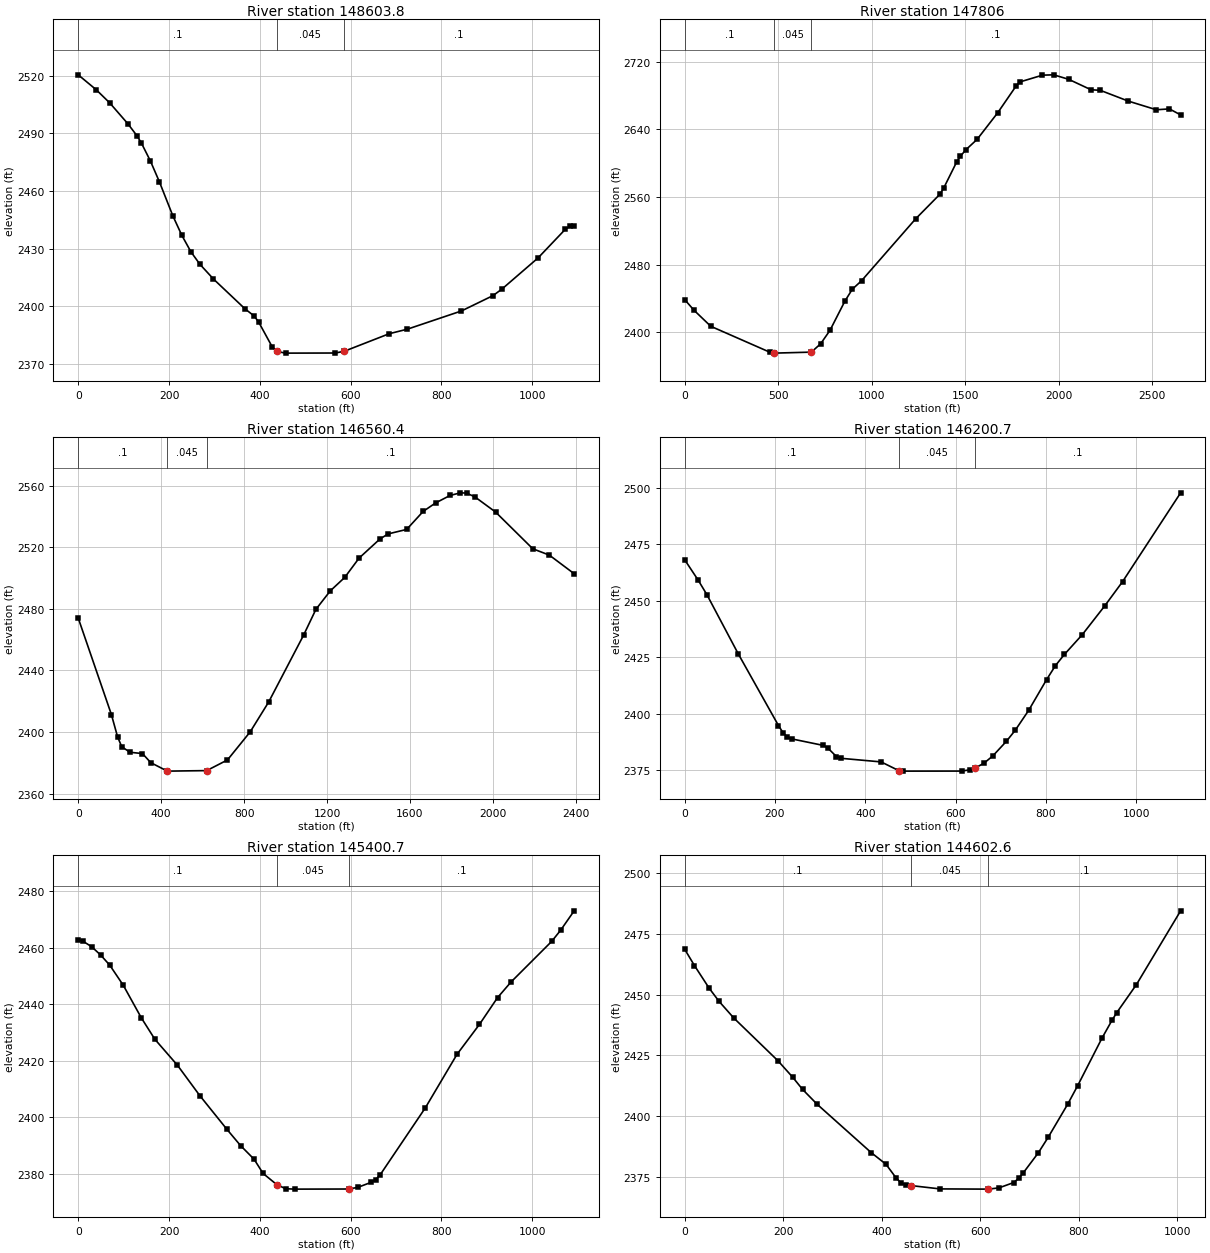
Type RM Length L Ch R = 1 ,148603.8,798,797.8,797.7
XS GIS Cut Line= 2
     2029058.042       364724.27     2030045.652      364257.339
#Sta/Elev= 30
       0  2520.5    39.7 2512.73    69.5 2505.86   109.2 2495.07   129.1 2488.88
     139 2485.06   158.9  2475.7   178.8 2464.82   208.6    2447   228.4 2436.86
   248.3 2428.34   268.1 2421.85   297.9 2414.19   367.4 2398.66   387.3 2394.99
   397.2  2391.9     427 2379.01     437  2376.5   456.8 2375.61   566.1 2375.67
   585.9 2376.57   685.2 2385.73     725 2388.08   844.2 2397.57   913.7 2405.56
   933.5 2408.99    1013  2425.2  1072.6    2440  1082.5 2441.55  1092.4    2442
#Mann= 3 , 0 , 0
       0      .1       0     437    .045       0   585.9      .1       0
Bank Sta=437,585.9
XS Rating Curve= 0 ,0
Exp/Cntr=0.3,0.1

Type RM Length L Ch R = 1 ,147806  ,1228.6,1245.6,1262.6
XS GIS Cut Line= 3
     2029548.112      365306.636     2030949.872      364635.894
     2031980.219      365015.833
#Sta/Elev= 30
       0 2438.87    49.8 2426.32   139.5 2407.34   458.2 2376.44   478.1 2375.62
   677.4  2376.8   727.2 2386.69     777 2402.52   856.7 2437.03   896.5 2451.15
   946.3 2461.28  1235.2 2534.34  1364.7 2563.33  1384.6 2570.44  1454.4 2601.48
  1474.3 2608.31  1504.2 2616.05    1564 2628.28  1673.8 2659.61  1773.6 2691.69
  1793.6 2696.16  1913.4 2704.11  1973.3  2704.5  2053.1 2699.23  2172.9 2686.87
  2222.8 2686.16  2372.6 2673.43  2522.4 2663.22  2592.2 2664.24  2652.1 2657.14
#Mann= 3 , 0 , 0
       0      .1       0   478.1    .045       0   677.4      .1       0
Bank Sta=478.1,677.4
XS Rating Curve= 0 ,0
Exp/Cntr=0.3,0.1

Type RM Length L Ch R = 1 ,146560.4,357.5,359.7,362.8
XS GIS Cut Line= 4
     2029683.943      366132.548     2030432.789      366350.495
     2030969.162       366557.56     2031997.138      366696.436
#Sta/Elev= 30
       0 2474.09     160 2411.41     190 2396.84     210 2390.46     250 2386.87
     310 2386.02     350 2380.12     430 2374.62   619.9 2374.96   719.9 2381.89
   829.5 2400.12   918.7 2419.53  1087.2 2462.98  1146.7 2479.76  1216.1 2491.76
  1285.5 2500.46  1354.9 2513.04  1454.6 2525.34  1494.5 2528.73  1584.3 2531.65
  1664.1 2543.39  1723.9 2548.86  1793.7 2553.73  1843.6 2555.43  1873.5 2555.25
  1913.4 2552.79  2013.2 2542.94  2192.7 2519.07  2272.5 2514.97  2392.2 2502.88
#Mann= 3 , 0 , 0
       0      .1       0     430    .045       0   619.9      .1       0
Bank Sta=430,619.9
XS Rating Curve= 0 ,0
Exp/Cntr=0.3,0.1

Type RM Length L Ch R = 1 ,146200.7,797.7,800,800.8
XS GIS Cut Line= 3
     2029601.895      366403.163     2030111.633      366619.639
     2030604.108      366852.197
#Sta/Elev= 30
       0 2468.19    29.7 2459.22    49.4 2452.67   118.7 2426.52   207.7 2394.81
   217.6  2391.7   227.4 2389.66   237.3 2388.88   306.6 2386.02   316.5 2384.94
   336.2 2381.05   346.1  2380.3   435.1  2378.7   474.7  2374.8   484.6 2374.62
   613.2 2374.64     633 2375.24   642.9 2375.96   662.7  2378.1   682.5 2381.36
   712.2 2387.75     732 2392.68   761.8  2401.5   801.4 2415.08   821.2 2421.34
     841 2426.28   880.6 2435.03   930.1 2447.71   969.7 2458.46  1098.4 2497.82
#Mann= 3 , 0 , 0
       0      .1       0   474.7    .045       0   642.9      .1       0
Bank Sta=474.7,642.9
XS Rating Curve= 0 ,0
Exp/Cntr=0.3,0.1

Type RM Length L Ch R = 1 ,145400.7,798.4,798,798.2
XS GIS Cut Line= 3
     2029239.998      367048.084     2029717.982      367312.445
     2030202.368      367564.326
#Sta/Elev= 30
       0 2462.76     9.9 2462.31    29.8 2460.28    49.7 2457.32    69.5 2453.77
    99.3 2446.66     139 2435.14   168.8 2427.57   218.5 2418.39   268.1 2407.57
   327.7 2395.67   357.5 2389.97   387.3 2385.14   407.2  2380.1     437 2376.19
   456.8  2374.7   476.7 2374.56   595.8  2374.6   615.7 2375.18   645.5 2376.99
   655.4 2377.94   665.3  2379.7   764.6 2403.35   834.1 2422.21   883.7 2432.84
   923.4 2442.28   953.2 2447.83  1042.6 2462.17  1062.4 2466.13  1092.2    2473
#Mann= 3 , 0 , 0
       0      .1       0     437    .045       0   595.8      .1       0
Bank Sta=437,595.8
XS Rating Curve= 0 ,0
Exp/Cntr=0.3,0.1

Type RM Length L Ch R = 1 ,144602.6,794.5,802,809.4
XS GIS Cut Line= 2
     2028970.947      367780.784     2029859.978      368253.346
#Sta/Elev= 30
       0 2468.64    19.9  2461.9    49.8 2452.58    69.8  2447.2    99.7 2440.36
   189.4 2422.77   219.3 2416.01   239.2 2411.03   269.2 2404.84   378.8    2385
   408.7 2380.23   428.6 2374.78   438.6 2372.66   448.6 2371.73   458.6 2371.49
   518.4  2370.1   616.6 2370.01     638 2370.52   667.9 2372.71   677.9 2374.42
   687.8 2376.82   717.7 2384.87   737.7 2391.24   777.6 2404.95   797.5 2412.42
   847.3 2432.14   867.3 2439.35   877.2 2442.58   917.1  2454.1  1006.8 2484.42
#Mann= 3 , 0 , 0
       0      .1       0   458.6    .045       0   616.6      .1       0
Bank Sta=458.6,616.6
XS Rating Curve= 0 ,0
Exp/Cntr=0.3,0.1

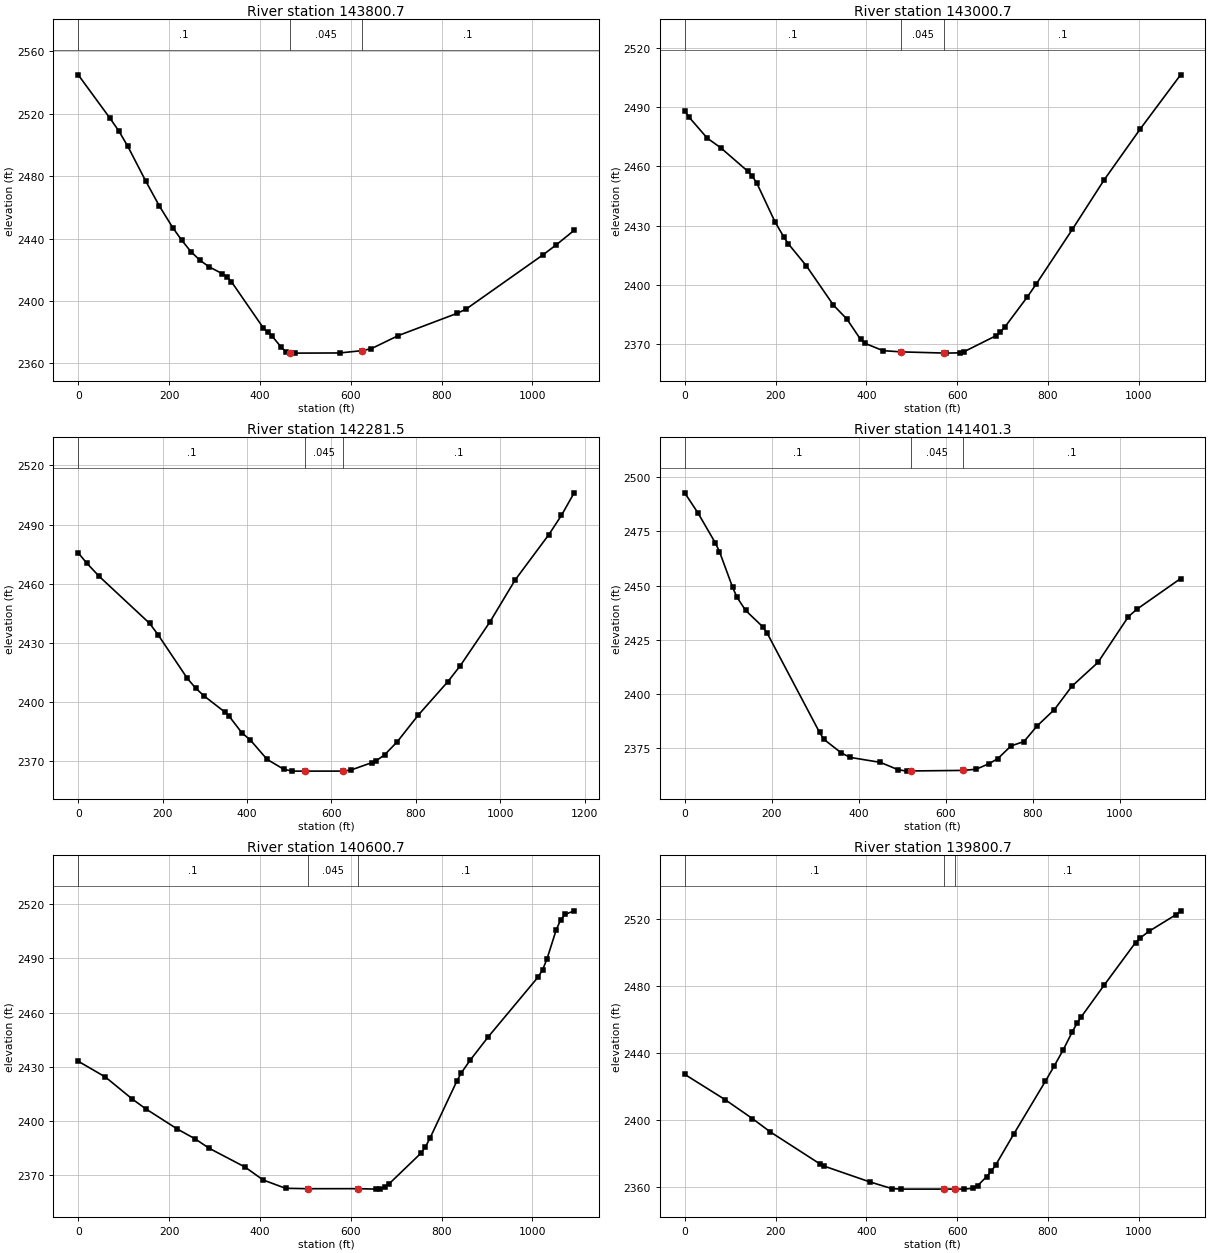
Type RM Length L Ch R = 1 ,143800.7,797.5,800,802.5
XS GIS Cut Line= 3
     2028534.033      368206.461     2028908.597      368603.725
      2029283.16      369000.988
#Sta/Elev= 30
       0  2544.9    69.5 2517.28    89.4 2508.95   109.2 2499.08   148.9 2476.71
   178.7 2460.86   208.5 2446.84   228.3  2438.8   248.2 2431.61     268 2426.12
   287.9 2421.94   317.7 2417.45   327.6 2415.53   337.5  2412.3     407    2383
     417 2379.91   426.9 2377.51   446.7  2370.5   456.6 2367.65   466.6 2366.67
   476.5 2366.61   575.8 2366.72   625.4 2368.22   645.3 2369.45   704.8 2377.85
   833.9 2392.06   853.8 2394.77  1022.5 2429.39  1052.3 2435.91    1092 2445.28
#Mann= 3 , 0 , 0
       0      .1       0   466.6    .045       0   625.4      .1       0
Bank Sta=466.6,625.4
XS Rating Curve= 0 ,0
Exp/Cntr=0.3,0.1

Type RM Length L Ch R = 1 ,143000.7,719.6,719.1,718.7
XS GIS Cut Line= 3
     2027977.289       368689.36     2028306.112       369125.24
     2028634.934      369561.121
#Sta/Elev= 30
       0 2488.28     9.9 2484.94    49.6 2474.38    79.4 2469.46     139 2457.54
   148.9 2455.04   158.8 2451.54   198.6    2432   218.4 2424.12   228.3  2420.7
     268 2409.51   327.6 2389.59   357.4 2382.45   387.2 2372.24   397.1 2370.19
   436.8 2366.48   476.5 2365.87     571 2365.26   575.8 2365.23   605.6 2365.39
   615.5    2366     685    2374   694.9 2375.79   704.8 2378.42   754.5 2393.76
   774.3 2400.38   853.8 2428.12   923.2 2453.03  1002.6 2478.86    1092  2506.5
#Mann= 3 , 0 , 0
       0      .1       0   476.5    .045       0     571      .1       0
Bank Sta=476.5,571
XS Rating Curve= 0 ,0
Exp/Cntr=0.3,0.1

Type RM Length L Ch R = 1 ,142281.5,892.4,880.2,868.1
XS GIS Cut Line= 3
     2027359.168       369080.43     2027826.269      369674.628
     2028130.367      369963.398
#Sta/Elev= 30
       0 2475.65    19.9  2470.5    49.7 2463.71   169.1 2439.86     189 2434.14
   258.6 2411.89   278.5  2406.9   298.4 2402.97   348.1  2394.7     358  2392.6
   387.8 2384.27   407.7 2380.65   447.5 2370.81   487.3 2365.74   507.2 2364.82
     537 2364.82   626.5 2364.84   646.4 2365.37   696.1 2369.17   706.1  2370.1
     726 2373.09   755.8 2379.68   805.7 2393.24   875.6 2410.17   905.6  2418.4
   975.5 2440.53  1035.4 2461.89  1115.3 2484.92  1145.2 2494.71  1175.2 2506.12
#Mann= 3 , 0 , 0
       0      .1       0     537    .045       0   626.5      .1       0
Bank Sta=537,626.5
XS Rating Curve= 0 ,0
Exp/Cntr=0.3,0.1

Type RM Length L Ch R = 1 ,141401.3,806.5,800.6,794.8
XS GIS Cut Line= 2
     2026719.296      370061.195     2027778.298      370483.119
#Sta/Elev= 30
       0 2492.81      30  2483.7      70 2469.88      80 2465.69     110 2449.34
     120 2444.74     140 2438.61     180 2430.94     190 2427.96     310 2382.36
     320 2379.16     360 2372.89     380 2370.83     450 2368.52     490 2365.18
     510 2364.49     520 2364.57     640 2364.82     670 2365.37     700 2367.95
     720 2370.29     750 2376.09     780 2378.15     810  2385.3     850  2392.9
     890 2403.61     950 2414.62    1020 2435.75    1040 2439.21    1140 2453.28
#Mann= 3 , 0 , 0
       0      .1       0     520    .045       0     640      .1       0
Bank Sta=520,640
XS Rating Curve= 0 ,0
Exp/Cntr=0.3,0.1

Type RM Length L Ch R = 1 ,140600.7,800.1,800,799.9
XS GIS Cut Line= 3
     2026493.935      370967.909     2027036.686      371027.389
     2027579.437      371086.869
#Sta/Elev= 30
       0 2433.07    59.6 2424.38   119.1 2412.14   148.9  2406.7   218.4 2395.52
   258.1    2390   287.9 2384.96   367.3  2374.5     407 2367.37   456.6 2362.74
   506.3 2362.52   615.5 2362.54   655.2 2362.28   665.1 2362.42     675 2363.35
     685 2365.33   754.5 2382.14   764.4  2385.6   774.3 2390.35   833.9 2422.19
   843.8 2426.75   863.7 2433.88   903.4 2446.76  1012.6 2479.68  1022.5 2483.68
  1032.4 2489.87  1052.3 2505.64  1062.2 2511.36  1072.2 2514.36    1092 2516.34
#Mann= 3 , 0 , 0
       0      .1       0   506.3    .045       0   615.5      .1       0
Bank Sta=506.3,615.5
XS Rating Curve= 0 ,0
Exp/Cntr=0.3,0.1

Type RM Length L Ch R = 1 ,139800.7,1187.6,1187.4,1187.3
XS GIS Cut Line= 3
     2026434.962      371766.452     2026977.855      371824.619
     2027520.748      371882.786
#Sta/Elev= 30
       0 2427.47    89.4  2412.3   148.9 2401.12   188.6 2393.12   297.8 2374.05
   307.8 2372.66     407 2363.37   456.6  2359.3   476.5 2359.02     571 2359.02
   595.6 2359.02   615.5 2359.01   635.4 2359.55   645.3 2361.14   665.1 2366.53
     675 2369.62     685 2373.48   724.7 2391.89   794.2 2423.33     814 2432.59
   833.9 2442.27   853.8 2452.98   863.7 2457.86   873.6 2461.89   923.2 2480.49
   992.7 2506.02  1002.6 2508.71  1022.5 2512.79  1082.1 2522.72    1092 2524.97
#Mann= 3 , 0 , 0
       0      .1       0     571    .045       0   595.6      .1       0
Bank Sta=571,595.6
XS Rating Curve= 0 ,0
Exp/Cntr=0.3,0.1

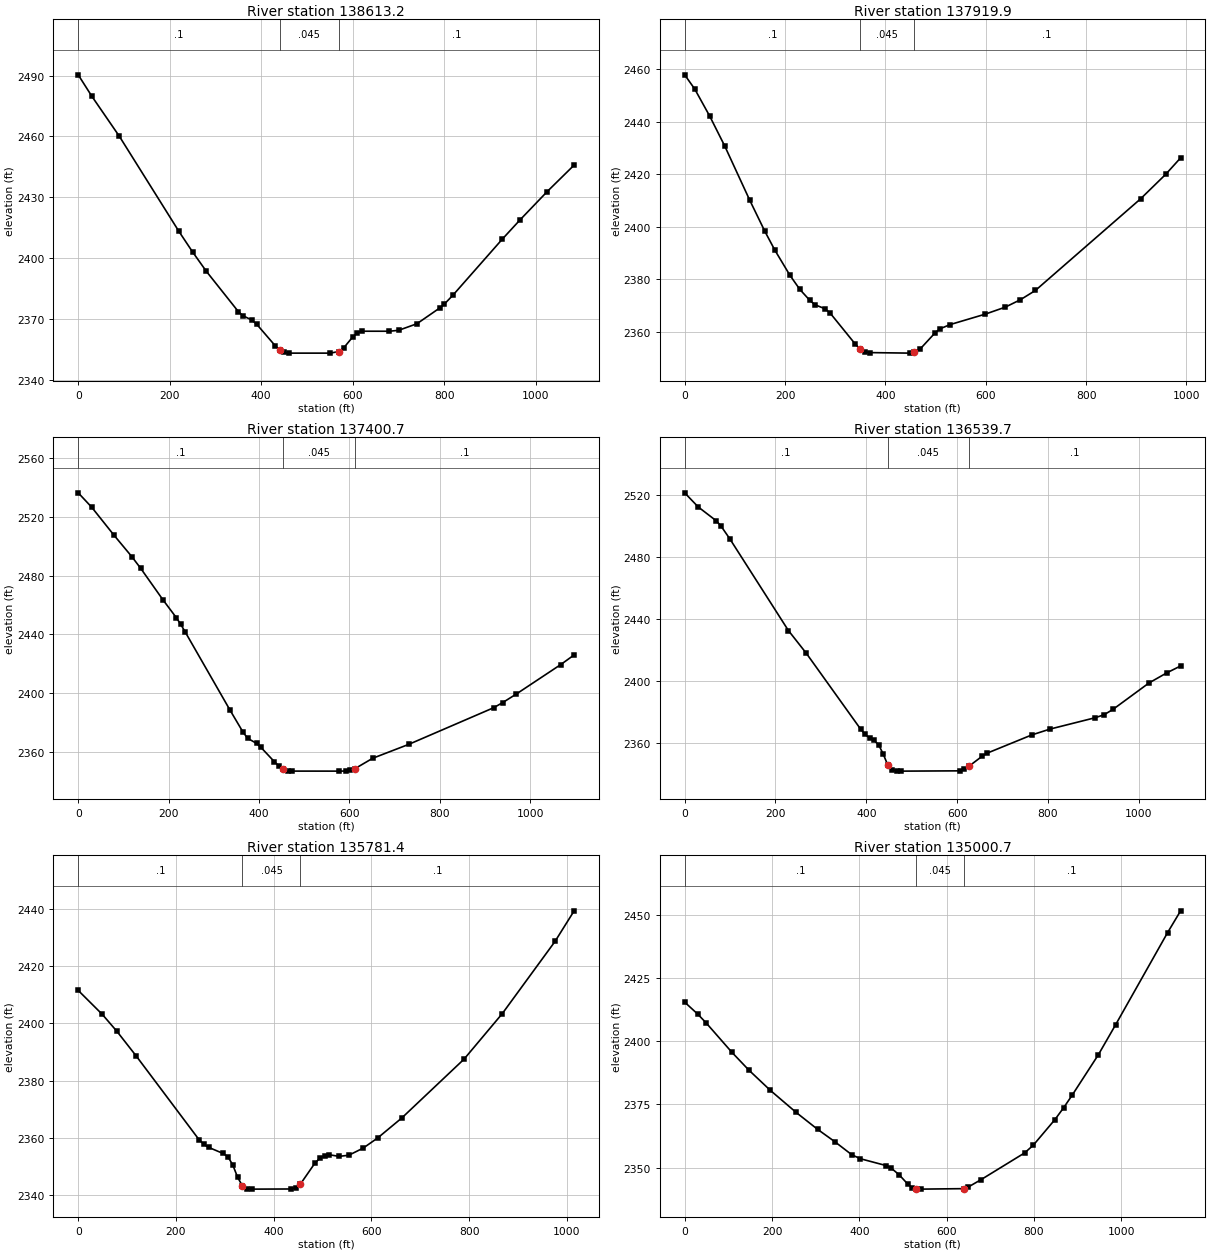
Type RM Length L Ch R = 1 ,138613.2,677.7,693.5,709.3
XS GIS Cut Line= 3
     2026306.146      372937.937     2027065.174      372985.206
     2027385.485      372936.778
#Sta/Elev= 30
       0 2490.39      30 2479.75    90.1 2460.04   220.1 2413.25   250.2 2403.05
   280.2 2393.54   350.2 2373.67   360.2 2371.65   380.2 2369.45   390.3 2367.45
   430.3 2356.97   440.3 2354.79   450.3 2353.55   460.3 2353.22   550.4 2353.22
   570.4    2354   580.4 2355.78   600.4 2361.23   610.4 2363.21   620.4 2364.02
   680.4 2364.01   700.5 2364.46   740.5 2367.69     790  2375.4   799.8 2377.21
   819.4 2381.79   927.4 2409.43   966.6 2419.02  1025.6 2432.88  1084.4 2445.91
#Mann= 3 , 0 , 0
       0      .1       0   440.3    .045       0   570.4      .1       0
Bank Sta=440.3,570.4
XS Rating Curve= 0 ,0
Exp/Cntr=0.3,0.1

Type RM Length L Ch R = 1 ,137919.9,510.1,519,528.7
XS GIS Cut Line= 2
     2026414.825      373300.775     2027103.994      374009.358
#Sta/Elev= 30
       0 2457.82      20 2452.42    49.9 2442.08    79.9 2430.66   129.8 2409.98
   159.8 2398.17   179.7 2391.01   209.7 2381.44   229.6 2376.02   249.6 2371.83
   259.6  2370.2   279.6 2368.67   289.6 2367.09   339.5 2355.32   349.4 2353.32
   359.4 2352.21   369.4 2351.96   449.3 2351.76   456.6 2352.02   469.3 2353.33
   499.2 2359.52   509.2 2361.06   529.2 2362.65   599.1 2366.62     639 2369.29
     669  2372.1   698.9 2375.63   908.6 2410.56   958.5 2419.87   988.4 2426.18
#Mann= 3 , 0 , 0
       0      .1       0   349.4    .045       0   456.6      .1       0
Bank Sta=349.4,456.6
XS Rating Curve= 0 ,0
Exp/Cntr=0.3,0.1

Type RM Length L Ch R = 1 ,137400.7,853,861,868.2
XS GIS Cut Line= 3
     2026126.149      373428.603     2026328.869      373942.527
     2026511.859       374455.74
#Sta/Elev= 30
       0 2536.52    29.6 2526.79    78.9 2507.74   118.4  2493.1   138.1 2485.11
   187.4 2463.62     217 2451.46   226.9 2446.83   236.8 2441.63   335.4 2388.65
     365  2373.2   374.9  2369.2   394.6  2365.7   404.5 2362.92   434.1 2353.21
   443.9 2350.35   453.8 2348.06   463.7    2347   473.5 2346.83   577.5 2346.81
   592.1 2346.87     602 2347.31   611.9 2348.42   651.5 2355.57   730.8 2364.99
     919    2390   938.8 2393.46   968.5  2399.2  1067.6 2419.44  1097.3 2426.02
#Mann= 3 , 0 , 0
       0      .1       0   453.8    .045       0   611.9      .1       0
Bank Sta=453.8,611.9
XS Rating Curve= 0 ,0
Exp/Cntr=0.3,0.1

Type RM Length L Ch R = 1 ,136539.7,758.1,758.3,758.5
XS GIS Cut Line= 2
     2025468.588      373528.306     2025493.882      374620.306
#Sta/Elev= 30
       0 2521.48    29.8 2512.38    69.5 2503.47    79.4 2500.31    99.3 2491.88
   228.4 2432.75   268.1 2417.99   387.3 2369.28   397.2 2365.87   407.1 2363.49
   417.1 2361.86     427 2359.17   436.9 2353.39   446.8 2346.39   456.8 2343.02
   466.7 2342.17   476.6 2342.12   605.7  2342.3   615.7 2343.28   625.6 2345.16
   655.4 2351.77   665.3  2353.6   764.6 2365.46   804.3 2369.19   903.6  2376.5
   923.5 2378.42   943.3  2381.9  1022.8 2398.97  1062.5 2405.56  1092.3  2409.9
#Mann= 3 , 0 , 0
       0      .1       0   446.8    .045       0   625.6      .1       0
Bank Sta=446.8,625.6
XS Rating Curve= 0 ,0
Exp/Cntr=0.3,0.1

Type RM Length L Ch R = 1 ,135781.4,782.9,780.7,778.5
XS GIS Cut Line= 3
     2024716.785      373663.386      2024726.07      374276.213
     2024643.369      374669.407
#Sta/Elev= 30
       0  2411.5    49.4 2403.11    79.1 2397.23   118.6 2388.62   247.1 2359.41
     257 2357.76   266.9  2356.7   296.6 2354.56   306.4 2353.41   316.3 2350.55
   326.2 2346.22   336.1 2343.23     346 2342.25   355.9 2342.12     435 2342.17
   444.8 2342.58   454.7  2343.9   484.4 2351.22   494.3 2352.88   504.2 2353.84
     514 2354.11   533.8 2353.56   553.6 2353.95   583.2 2356.46   612.9 2360.01
   661.9 2366.94   789.3 2387.48   867.7 2403.41   975.5 2428.59  1014.7 2439.29
#Mann= 3 , 0 , 0
       0      .1       0   336.1    .045       0   454.7      .1       0
Bank Sta=336.1,454.7
XS Rating Curve= 0 ,0
Exp/Cntr=0.3,0.1

Type RM Length L Ch R = 1 ,135000.7,806.2,800,792.9
XS GIS Cut Line= 4
     2023699.695      373689.465     2023923.183      373950.263
     2023950.799      374194.867     2024012.055       374737.42
#Sta/Elev= 30
       0 2415.45    29.4  2410.8    49.1 2407.26   107.9 2395.66   147.2 2388.54
   196.3 2380.55   255.1 2371.87   304.2 2365.18   343.5 2360.31   382.8 2355.09
   402.5 2353.53   461.6 2350.82   471.5 2350.04   491.2 2347.17   510.8 2343.52
   520.7 2342.16   530.5 2341.57   540.4 2341.52   639.2 2341.71   649.2 2342.34
     679 2345.31   778.2 2355.82   798.1 2358.86   847.7    2369   867.6 2373.67
   887.4  2378.7     947 2394.59   986.7  2406.5  1105.8 2442.96  1135.6 2451.56
#Mann= 3 , 0 , 0
       0      .1       0   530.5    .045       0   639.2      .1       0
Bank Sta=530.5,639.2
XS Rating Curve= 0 ,0
Exp/Cntr=0.3,0.1