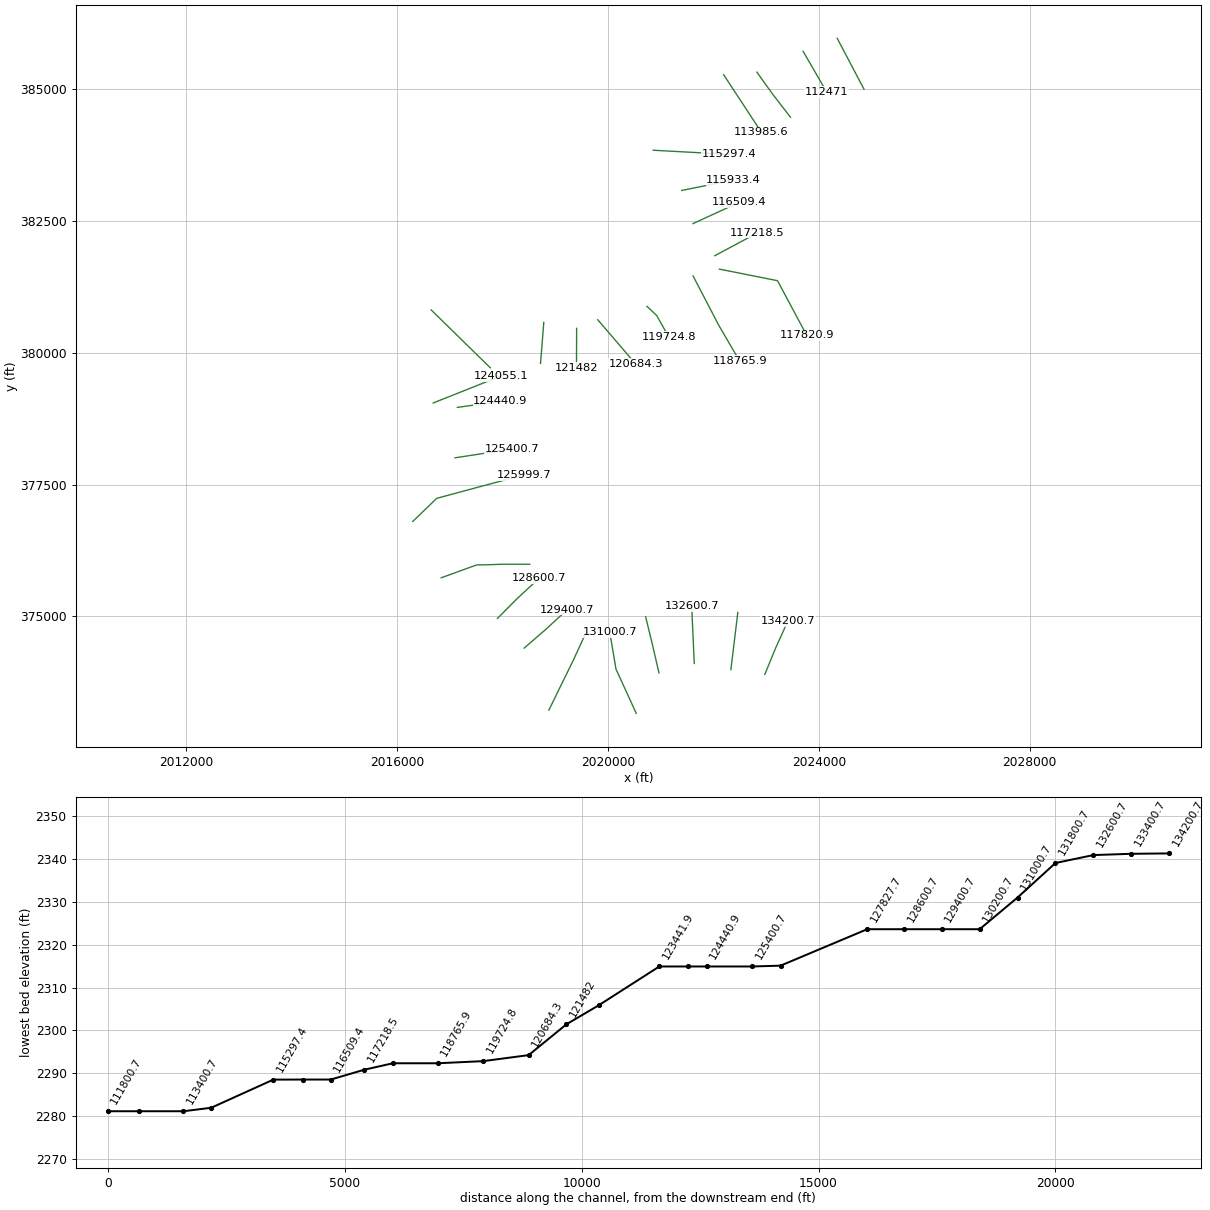
HEC-RAS study MeadowRvr.prj: MeadowRvr

--- MeadowRvr.g01 (geometry) --- (continued)

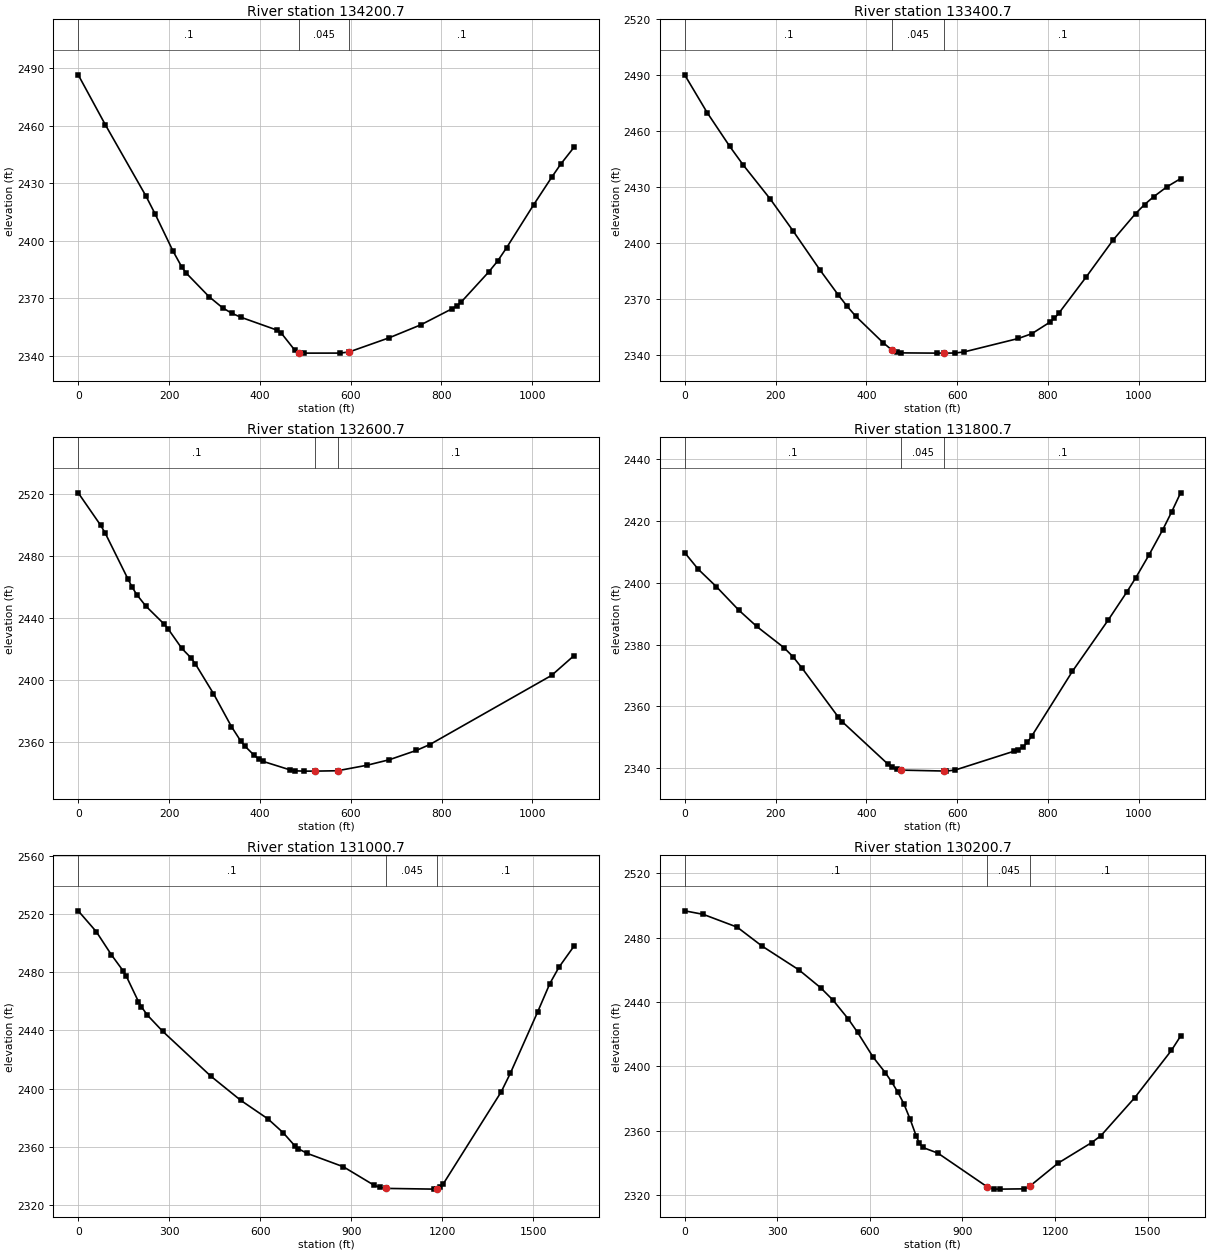
Type RM Length L Ch R = 1 ,134200.7,793.9,800,806.9
XS GIS Cut Line= 3
     2022977.034      373899.331     2023184.299      374404.937
     2023409.618      374902.192
#Sta/Elev= 30
       0 2486.48    59.6  2460.5     149 2423.34   168.9 2414.14   208.6 2394.63
   228.5 2386.08   238.4 2382.94   288.1 2370.78   317.9 2364.97   337.8 2362.17
   357.7 2360.08   437.2 2353.37   447.1 2351.81   476.9 2342.89   486.8 2341.55
   496.8 2341.31   576.2 2341.33   596.1 2341.87   685.4 2349.35   754.9  2356.1
   824.4 2364.57   834.3 2366.06   844.2 2368.11   903.8 2383.54   923.6 2389.26
   943.5 2396.26    1003 2418.64  1042.7 2432.96  1062.6 2439.82  1092.4  2448.8
#Mann= 3 , 0 , 0
       0      .1       0   486.8    .045       0   596.1      .1       0
Bank Sta=486.8,596.1
XS Rating Curve= 0 ,0
Exp/Cntr=0.3,0.1

Type RM Length L Ch R = 1 ,133400.7,796.3,800,803.7
XS GIS Cut Line= 3
     2022332.837      373989.599     2022398.538      374531.632
     2022464.239      375073.664
#Sta/Elev= 30
       0 2490.23    49.6 2469.96    99.3 2451.89     129 2441.92   188.6 2423.67
   238.2 2406.83   297.8 2385.78   337.5  2372.6   357.4  2366.4   377.2 2360.84
   436.8 2346.83   456.8 2342.78   466.6 2341.71   476.5 2341.35   555.9 2341.22
     571 2341.22   595.6 2341.28   615.5 2341.88   734.6 2349.06   764.4 2351.63
   804.1 2357.78     814 2359.87     824 2362.65   883.5 2381.81   943.1 2401.72
   992.7  2415.9  1012.6 2420.78  1032.4 2424.92  1062.2 2430.33    1092 2434.65
#Mann= 3 , 0 , 0
       0      .1       0   456.8    .045       0     571      .1       0
Bank Sta=456.8,571
XS Rating Curve= 0 ,0
Exp/Cntr=0.3,0.1

Type RM Length L Ch R = 1 ,132600.7,795.9,800,804.4
XS GIS Cut Line= 3
       2021637.3      374106.353     2021613.236      374651.822
     2021589.172      375197.291
#Sta/Elev= 30
       0 2521.05    49.6 2499.96    59.6 2494.88   109.2 2465.46   119.1 2459.83
     129 2455.14   148.9 2447.75   188.6 2436.25   198.6  2432.7   228.3  2420.3
   248.2 2414.27   258.1 2410.24   297.8  2391.1   337.5 2369.69   357.4 2360.61
   367.3 2357.02   387.2 2351.24   397.1 2348.83     407 2347.23   466.6 2341.71
   476.5 2341.13   496.4 2340.92     521 2340.92     571 2341.17   635.4  2344.7
     685 2348.29   744.6 2354.33   774.3 2358.14  1042.4  2402.9    1092 2415.76
#Mann= 3 , 0 , 0
       0      .1       0     521    .045       0     571      .1       0
Bank Sta=521,571
XS Rating Curve= 0 ,0
Exp/Cntr=0.3,0.1

Type RM Length L Ch R = 1 ,131800.7,801.4,800,798.3
XS GIS Cut Line= 3
     2020967.876      373927.807     2020844.781      374459.793
     2020715.735      374990.316
#Sta/Elev= 30
       0 2409.73    29.8 2404.36    69.5 2398.75   119.1 2391.13   158.8 2385.84
   218.4 2379.02   238.3  2376.1   258.1 2372.45   337.6 2356.68   347.5 2354.96
   446.8 2341.44   456.7 2340.34   466.6 2339.64   476.6  2339.4     571  2339.1
   575.8 2339.07   595.7 2339.43   724.7 2345.49   734.7 2346.03   744.6 2346.88
   754.5 2348.35   764.4 2350.45   853.8 2371.36   933.2 2388.06   972.9 2396.84
   992.8 2401.49  1022.5    2409  1052.3 2417.03  1072.2 2422.87    1092 2429.06
#Mann= 3 , 0 , 0
       0      .1       0   476.6    .045       0     571      .1       0
Bank Sta=476.6,571
XS Rating Curve= 0 ,0
Exp/Cntr=0.3,0.1

Type RM Length L Ch R = 1 ,131000.7,814,800,786.5
XS GIS Cut Line= 3
     2020537.459      373159.423     2020152.944      373998.694
     2020034.832      374699.987
#Sta/Elev= 30
       0 2522.05    59.6 2507.74   109.2  2491.9   148.9  2480.6   158.8 2477.05
   198.5 2459.75   208.5 2456.08   228.3 2450.37   277.9 2439.45   436.8 2408.59
     536  2391.9   625.4 2379.19     675 2369.83   714.7 2360.52   724.6 2358.81
   754.4 2355.56   873.5 2346.39   973.2 2333.89   993.3 2332.22  1013.3 2331.51
  1173.6 2331.01  1183.6 2331.14  1193.6 2332.37  1203.6 2334.81  1393.9 2397.79
    1424 2410.53  1514.1 2452.68  1554.2 2472.12  1584.2 2483.34  1634.3 2497.96
#Mann= 3 , 0 , 0
       0      .1       0  1013.3    .045       0  1183.6      .1       0
Bank Sta=1013.3,1183.6
XS Rating Curve= 0 ,0
Exp/Cntr=0.3,0.1

Type RM Length L Ch R = 1 ,130200.7,809.1,800,791.1
XS GIS Cut Line= 3
     2018879.415      373221.459     2019346.095      374174.097
      2019574.27      374670.133
#Sta/Elev= 30
       0 2496.64      60 2494.46   170.1 2486.49   250.2 2474.78   370.3  2459.9
   440.3 2448.85   480.4 2441.14   530.4 2429.33   560.4 2421.02   610.5 2405.67
   650.5 2395.89   670.5 2390.27   690.5 2383.94   710.5  2376.5   730.6 2366.99
   750.6 2356.41   760.6 2352.22   770.6 2349.59   820.6 2345.96   980.7 2324.95
  1000.8 2323.67  1020.8 2323.61  1100.5 2323.79  1120.4  2325.8  1209.7 2339.75
  1318.9 2352.58  1348.7 2356.86  1457.9  2380.4    1577 2409.86  1606.8 2418.78
#Mann= 3 , 0 , 0
       0      .1       0   980.7    .045       0  1120.4      .1       0
Bank Sta=980.7,1120.4
XS Rating Curve= 0 ,0
Exp/Cntr=0.3,0.1

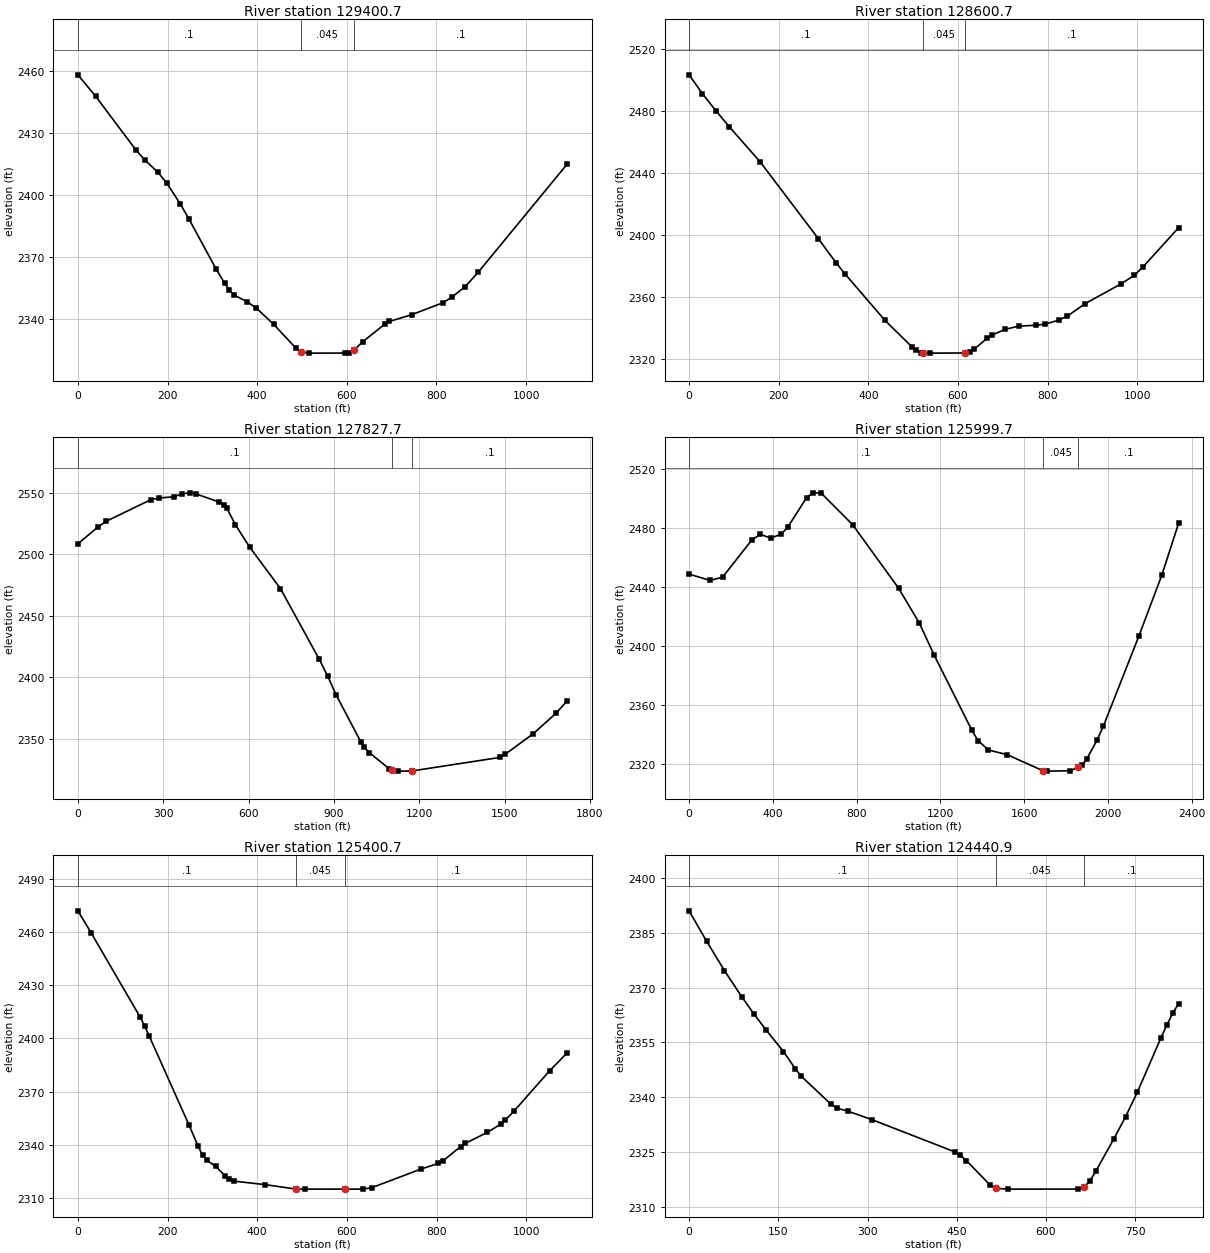
Type RM Length L Ch R = 1 ,129400.7,798.3,800,800
XS GIS Cut Line= 3
     2018411.228      374397.842     2018824.342      374755.368
       2019225.5      375125.668
#Sta/Elev= 30
       0 2458.25    39.7 2447.84   129.1 2422.01     149 2417.12   178.8 2411.04
   198.7 2405.74   228.5 2395.81   248.3 2388.28   307.9 2364.48   327.8  2357.3
   337.7 2354.12   347.7 2351.81   377.5 2348.48   397.3 2345.58   437.1 2337.48
   486.7 2325.94   496.7 2324.33   516.5 2323.61     596 2323.64   605.9 2323.85
   615.8 2325.04   635.7 2329.14   685.3 2337.72   695.2 2338.93   744.9 2342.22
   814.4 2347.97   834.2 2350.68     864 2355.73   893.8 2362.91  1092.3 2415.23
#Mann= 3 , 0 , 0
       0      .1       0   496.7    .045       0   615.8      .1       0
Bank Sta=496.7,615.8
XS Rating Curve= 0 ,0
Exp/Cntr=0.3,0.1

Type RM Length L Ch R = 1 ,128600.7,789.9,773,757
XS GIS Cut Line= 3
     2017903.311      374960.761     2018289.324      375347.643
     2018689.889      375718.538
#Sta/Elev= 30
       0 2503.58    29.8  2491.4    59.6 2480.43    89.4 2470.12     159 2447.16
   288.2 2397.72   327.9  2382.1   347.8 2374.87   437.2 2344.77   496.8 2327.82
   506.8 2325.33   516.7 2323.91   521.5 2323.78   536.6 2323.61     616  2323.7
   625.9 2324.34   635.8 2326.07   665.6 2333.31   675.6  2335.2   705.3    2339
   735.1 2341.05   774.8 2341.65   794.7 2342.37   824.4  2344.9   844.3 2347.56
     884 2355.66   963.4 2368.31   993.2 2373.84    1013 2379.39  1092.4 2404.74
#Mann= 3 , 0 , 0
       0      .1       0   521.5    .045       0     616      .1       0
Bank Sta=521.5,616
XS Rating Curve= 0 ,0
Exp/Cntr=0.3,0.1

Type RM Length L Ch R = 1 ,127827.7,1823,1828,1833
XS GIS Cut Line= 5
      2016837.55      375731.414     2017507.051      375974.253
     2017809.357      375981.078     2017988.348      375988.161
      2018515.76      375988.204
#Sta/Elev= 30
       0  2508.3    69.2 2521.72    98.9 2526.55   257.2 2544.24   286.8 2545.54
   336.3 2546.49     366 2548.96   395.7 2549.74   415.4 2548.84   494.6 2542.45
   514.4 2539.72   524.2 2537.02   553.9 2523.77   603.4 2505.78   712.2 2471.89
   848.7 2414.39     878 2400.89   907.3 2385.77   995.1 2347.22  1004.8 2343.46
  1024.5 2338.65  1094.2 2325.62  1105.9 2324.18    1124 2323.61  1173.8 2323.73
  1482.3 2334.69  1502.2 2337.29  1601.7 2354.16  1681.3 2370.71  1721.1 2380.95
#Mann= 3 , 0 , 0
       0      .1       0  1105.9    .045       0  1173.8      .1       0
Bank Sta=1105.9,1173.8
XS Rating Curve= 0 ,0
Exp/Cntr=0.3,0.1

Type RM Length L Ch R = 1 ,125999.7,601.4,599,597
XS GIS Cut Line= 3
     2016297.846      376800.576      2016751.96      377238.526
     2018400.158      377681.665
#Sta/Elev= 30
       0 2448.84   100.1 2444.57   160.2  2446.8   300.4 2472.14   340.5 2475.82
   390.6 2473.27   440.6 2476.04   470.7 2480.61   560.8 2500.66   590.8 2504.02
   630.9 2503.82   780.6 2482.45  1000.2 2439.33    1100 2415.45  1169.9 2393.95
  1349.5 2343.08  1379.4 2335.84  1429.4 2329.45  1519.2 2326.27  1688.9 2315.41
  1708.8  2315.1  1818.6 2315.34  1858.5  2317.6  1878.5 2319.42  1898.5  2323.2
  1948.4 2336.27  1978.3 2345.65    2148 2406.86  2257.8 2448.31  2337.6 2483.39
#Mann= 3 , 0 , 0
       0      .1       0  1688.9    .045       0  1858.5      .1       0
Bank Sta=1688.9,1858.5
XS Rating Curve= 0 ,0
Exp/Cntr=0.3,0.1

Type RM Length L Ch R = 1 ,125400.7,960.1,959.8,959
XS GIS Cut Line= 3
     2017097.538      378006.575     2017637.166      378089.594
     2018175.203      378183.259
#Sta/Elev= 30
       0 2472.07    29.8 2459.52     139    2412   148.9 2407.05   158.8 2401.54
   248.2 2350.95     268 2339.24     278 2334.15   287.9 2331.17   307.7 2327.72
   327.6 2322.54   337.5 2320.48   347.4 2319.44   416.9 2317.48   486.4 2314.95
   506.3 2314.91   595.6 2314.91   635.3 2314.92   655.2 2315.69   764.4 2326.16
   804.2 2329.45   814.1 2330.75   853.8 2338.96   863.7 2340.68   913.4 2346.95
   943.2 2351.61   953.1  2353.8     973 2359.02  1052.4 2381.76  1092.1 2392.04
#Mann= 3 , 0 , 0
       0      .1       0   486.4    .045       0   595.6      .1       0
Bank Sta=486.4,595.6
XS Rating Curve= 0 ,0
Exp/Cntr=0.3,0.1

Type RM Length L Ch R = 1 ,124440.9,380.4,385.8,391.2
XS GIS Cut Line= 2
     2017143.412      378963.502     2017958.543       379076.53
#Sta/Elev= 30
       0 2390.95    29.7 2382.59    59.5  2374.6    89.2 2367.32   109.1 2362.75
   128.9 2358.51   158.6 2352.51   178.5 2347.83   188.4 2345.77     238  2338.2
   247.9 2337.08   267.7 2336.17   307.4  2333.9   446.2 2325.12   456.1 2324.12
     466 2322.73   505.7 2316.08   515.6 2315.14   535.4 2314.91   654.4 2314.92
   664.3 2315.48   674.2 2317.23   684.1 2319.94   713.9 2328.62   733.7 2334.67
   753.5  2341.4   793.2 2356.25   803.1 2359.77     813 2363.01   822.9  2365.6
#Mann= 3 , 0 , 0
       0      .1       0   515.6    .045       0   664.3      .1       0
Bank Sta=515.6,664.3
XS Rating Curve= 0 ,0
Exp/Cntr=0.3,0.1

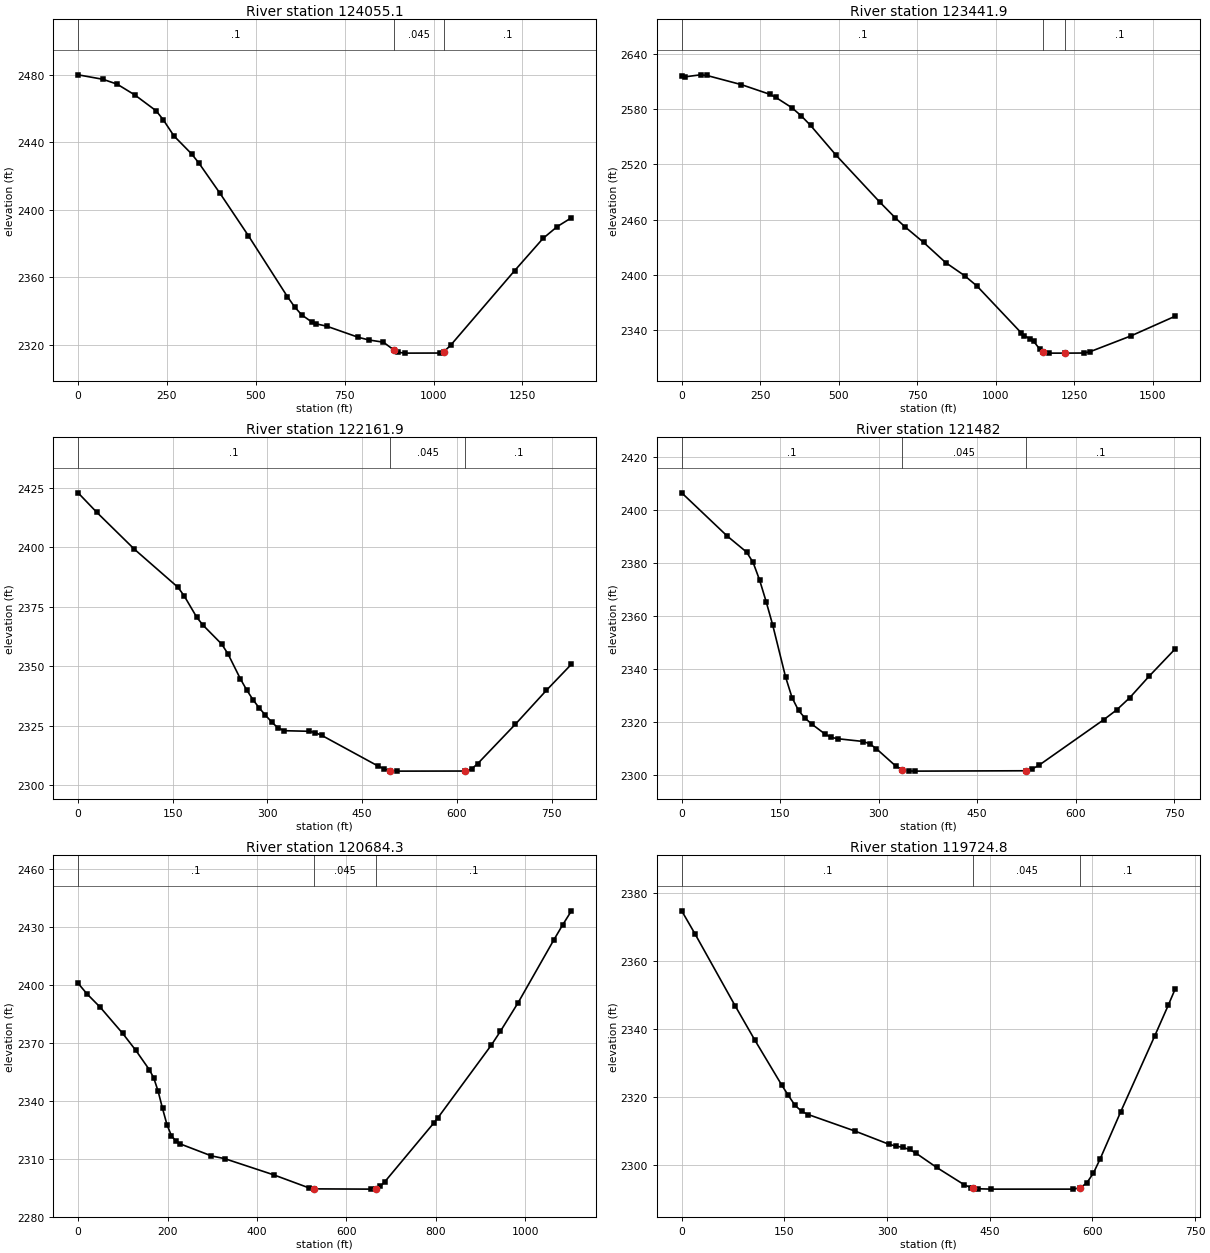
Type RM Length L Ch R = 1 ,124055.1,639.4,613.2,587
XS GIS Cut Line= 2
     2016685.609      379047.171     2017975.308      379559.927
#Sta/Elev= 30
       0 2480.09    69.9 2477.44   109.8 2474.56   159.8 2468.12   219.7 2458.72
   239.6 2453.42   269.6 2443.84   319.5 2433.12   339.5 2427.83   399.4 2409.71
   479.3 2384.54   589.1 2348.36   609.1 2342.38     629 2337.62     659 2333.17
     669 2332.32   698.9 2330.94   788.8 2324.27   818.8 2322.69   858.7 2321.42
   888.6 2316.76   898.6 2315.48   918.6 2314.91  1018.4 2314.97  1028.4 2315.59
  1048.4 2319.66  1228.1 2363.86    1308 2382.99    1348 2390.02  1387.9 2395.24
#Mann= 3 , 0 , 0
       0      .1       0   888.6    .045       0  1028.4      .1       0
Bank Sta=888.6,1028.4
XS Rating Curve= 0 ,0
Exp/Cntr=0.3,0.1

Type RM Length L Ch R = 1 ,123441.9,1299.7,1279.9,1260.1
XS GIS Cut Line= 2
     2016646.132      380812.368     2017768.537      379713.608
#Sta/Elev= 30
       0 2615.65      10 2615.14      60 2617.32      80 2616.64   190.1 2606.66
   280.1 2596.22   300.1 2592.69   350.2 2581.73   380.2 2572.89   410.2 2562.39
   490.2 2530.49   630.3 2479.15   680.3 2461.81   710.3 2452.31   770.3 2435.18
   840.4 2413.29   900.4 2399.15   940.4 2387.73  1080.5  2337.1  1090.5 2333.86
  1110.5 2330.23  1120.5 2327.72  1140.5 2319.06  1150.5 2315.87  1170.5 2314.91
  1219.8 2314.91  1280.6 2315.02  1300.6 2316.52  1430.6 2333.67  1570.7 2354.97
#Mann= 3 , 0 , 0
       0      .1       0  1150.5    .045       0  1219.8      .1       0
Bank Sta=1150.5,1219.8
XS Rating Curve= 0 ,0
Exp/Cntr=0.3,0.1

Type RM Length L Ch R = 1 ,122161.9,678.2,680,681.7
XS GIS Cut Line= 2
      2018782.98      380576.544      2018721.36      379797.434
#Sta/Elev= 30
       0 2422.94    29.7 2414.72      89 2399.26   158.3 2383.17   168.2 2379.52
     188 2370.57   197.9 2367.26   227.5 2359.28   237.4  2355.2   257.2 2344.61
   267.1 2339.99     277 2335.92   286.9 2332.43   296.8 2329.39   306.7 2326.48
   316.6 2324.03   326.5 2322.85     366  2322.6   375.9 2322.01   385.8 2320.91
   474.9 2308.02   484.8 2306.78   494.6 2306.02   504.5 2305.84   613.4 2305.88
   623.3 2306.73   633.2 2309.04   692.5 2325.51     742 2339.88   781.5 2350.82
#Mann= 3 , 0 , 0
       0      .1       0   494.6    .045       0   613.4      .1       0
Bank Sta=494.6,613.4
XS Rating Curve= 0 ,0
Exp/Cntr=0.3,0.1

Type RM Length L Ch R = 1 ,121482  ,781.6,797.7,813.7
XS GIS Cut Line= 2
     2019405.939      380462.454     2019403.145      379710.813
#Sta/Elev= 30
       0 2406.55    69.2 2390.25    98.9 2384.16   108.8 2380.23   118.7 2373.58
   128.6 2365.49   138.5 2356.75   158.2 2337.03   168.1 2329.19     178 2324.32
   187.9 2321.43   197.8 2319.25   217.6 2315.55   227.5 2314.18   237.4 2313.66
   276.9  2312.6   286.8 2311.66   296.7 2309.85   326.4 2303.26   336.3 2301.91
   346.2 2301.48     356 2301.41   524.2 2301.55   534.1 2302.25     544 2303.58
   642.8 2320.81   662.6 2324.52   682.4  2329.1   712.1 2337.26   751.6 2347.53
#Mann= 3 , 0 , 0
       0      .1       0   336.3    .045       0   524.2      .1       0
Bank Sta=336.3,524.2
XS Rating Curve= 0 ,0
Exp/Cntr=0.3,0.1

Type RM Length L Ch R = 1 ,120684.3,963.8,959.5,955.1
XS GIS Cut Line= 2
     2019806.296      380626.107     2020524.564      379788.729
#Sta/Elev= 30
       0 2400.77    19.9  2395.3    49.7 2388.31    99.4 2374.93   129.2 2366.02
     159 2356.14     169 2351.91   178.9 2344.96   188.8 2335.99   198.8 2327.57
   208.7 2321.87   218.7 2319.08   228.6  2317.6   298.2 2311.42     328 2309.98
   437.3 2301.62   516.8 2294.81   526.8 2294.34     656 2294.21   665.9 2294.43
   675.8  2295.7   685.8    2298   795.1 2328.36   805.1 2331.29   924.3 2368.84
   944.2 2375.86     984 2390.73  1063.5 2423.11  1083.4 2430.93  1103.2 2438.29
#Mann= 3 , 0 , 0
       0      .1       0   526.8    .045       0   665.9      .1       0
Bank Sta=526.8,665.9
XS Rating Curve= 0 ,0
Exp/Cntr=0.3,0.1

Type RM Length L Ch R = 1 ,119724.8,959.7,958.9,958
XS GIS Cut Line= 3
     2020741.568       380878.79     2020925.667      380705.017
     2021155.109      380297.596
#Sta/Elev= 30
       0 2374.88    19.5 2368.06    77.9 2346.93   107.1 2336.67     146 2323.54
   155.8 2320.44   165.5 2317.54   175.3 2315.73     185 2314.79   253.2 2309.93
   302.9 2306.03   312.8 2305.51   322.8 2305.14   332.8  2304.5   342.7 2303.35
   372.5  2299.2   412.3 2294.15   422.3 2293.27   425.9 2293.14   432.2 2292.92
   452.1 2292.81   571.5 2292.81   581.5 2293.15   591.4 2294.54   601.4 2297.52
   611.3 2301.72   641.2 2315.56   690.9 2337.93   710.8 2347.04   720.7 2351.74
#Mann= 3 , 0 , 0
       0      .1       0   425.9    .045       0   581.5      .1       0
Bank Sta=425.9,581.5
XS Rating Curve= 0 ,0
Exp/Cntr=0.3,0.1

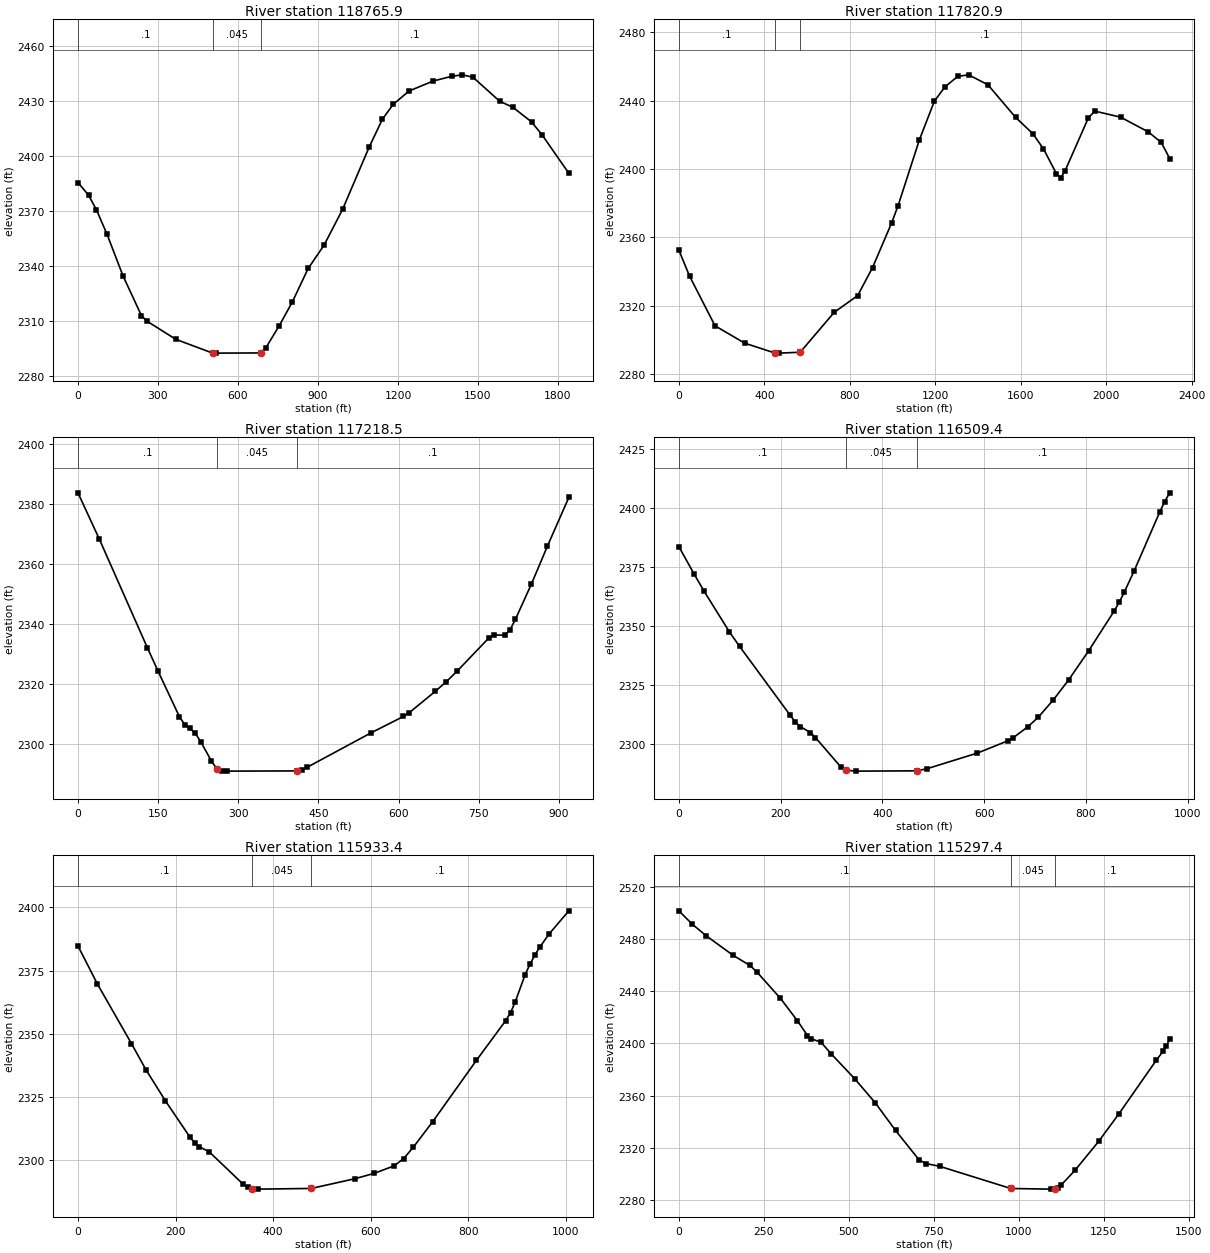
Type RM Length L Ch R = 1 ,118765.9,924.8,945.1,965.3
XS GIS Cut Line= 4
     2021614.766      381457.294     2021866.983      380973.039
     2022105.235      380515.594     2022498.208      379843.029
#Sta/Elev= 30
       0 2385.51    39.7  2378.6    69.5 2370.54   109.2 2357.16   168.8 2334.56
   238.2 2312.75   258.1 2309.83   367.3 2299.82     505 2292.33   516.2 2292.31
   684.9 2292.41   704.7 2295.25   754.3 2307.17   803.9 2320.28   863.4  2338.6
   922.9 2351.29   992.3 2370.84  1091.7 2404.77  1141.7 2420.09  1181.6 2428.13
  1241.5 2435.48  1331.4 2440.91  1401.3 2443.53  1441.3 2444.33  1481.2 2443.02
  1581.1 2429.94    1631 2426.59  1700.9 2418.61  1740.9 2411.42  1840.7 2390.56
#Mann= 3 , 0 , 0
       0      .1       0     505    .045       0   684.9      .1       0
Bank Sta=505,684.9
XS Rating Curve= 0 ,0
Exp/Cntr=0.3,0.1

Type RM Length L Ch R = 1 ,117820.9,586.8,602.4,617.9
XS GIS Cut Line= 3
      2022113.52      381585.723     2023217.519      381366.435
     2023769.774      380333.213
#Sta/Elev= 30
       0 2352.52    49.8 2337.41   169.3 2308.26   308.8  2298.1   450.5 2292.35
   468.2 2292.31   567.8 2292.83   727.1 2316.19   836.7 2325.94   906.4 2342.33
   996.1 2368.57    1026 2378.56  1125.6 2417.02  1195.7 2439.61  1245.7 2448.07
  1305.8 2454.12  1355.9 2455.01    1446 2449.22  1576.2 2430.08  1656.3 2420.61
  1706.3 2411.72  1766.4 2397.31  1786.4 2394.84  1806.5 2398.67  1916.6 2429.92
  1946.6 2433.79  2066.8 2430.27    2197 2421.64  2257.1 2415.51  2297.1 2406.08
#Mann= 3 , 0 , 0
       0      .1       0   450.5    .045       0   567.8      .1       0
Bank Sta=450.5,567.8
XS Rating Curve= 0 ,0
Exp/Cntr=0.3,0.1

Type RM Length L Ch R = 1 ,117218.5,710.5,709.1,707.7
XS GIS Cut Line= 2
       2022026.9      381839.995     2022837.219      382273.096
#Sta/Elev= 30
       0 2383.73      40 2368.27   129.8 2332.06   149.8 2324.24   189.8 2309.02
   199.7 2306.37   209.7 2305.06   219.7  2303.4   229.7 2300.68   249.7  2294.2
   259.7 2291.67   269.6 2290.82   279.6 2290.81   409.5 2290.88   419.4 2291.28
   429.4 2292.14   549.3 2303.66   609.2 2309.06   619.2 2310.19   669.1 2317.49
   689.1 2320.61   709.1 2324.08     769 2335.26     779 2336.32     799 2336.17
   808.9 2338.03   818.9 2341.53   848.9 2353.34   878.8 2365.96   918.8 2382.19
#Mann= 3 , 0 , 0
       0      .1       0   259.7    .045       0   409.5      .1       0
Bank Sta=259.7,409.5
XS Rating Curve= 0 ,0
Exp/Cntr=0.3,0.1

Type RM Length L Ch R = 1 ,116509.4,581.1,576,570.9
XS GIS Cut Line= 2
     2021613.358      382449.131     2022490.236      382851.048
#Sta/Elev= 30
       0  2383.6    29.8 2372.05    49.7 2364.68    99.4 2347.46   119.3 2341.35
   218.8 2312.16   228.7 2309.33   238.7 2307.36   258.6 2304.86   268.5  2302.7
   318.2  2290.3   328.2 2288.94     348 2288.51   467.4 2288.63   487.3 2289.51
   586.7 2296.16   646.4 2301.33   656.3 2302.51   686.2 2307.38     706 2311.28
   735.9  2318.7   765.7 2327.06   805.5 2339.54   855.2 2356.25   865.2 2359.97
   875.1 2364.21     895 2373.48   944.7 2398.12   954.6 2402.65   964.6 2406.38
#Mann= 3 , 0 , 0
       0      .1       0   328.2    .045       0   467.4      .1       0
Bank Sta=328.2,467.4
XS Rating Curve= 0 ,0
Exp/Cntr=0.3,0.1

Type RM Length L Ch R = 1 ,115933.4,641.8,636,630.2
XS GIS Cut Line= 2
     2021398.205      383077.826     2022384.558      383276.214
#Sta/Elev= 30
       0 2384.74    39.8 2369.69   109.6 2346.12   139.5  2335.7   179.3 2323.42
   229.1 2309.22   239.1 2306.81     249 2305.26     269 2303.28   338.7 2290.43
   348.6 2289.16   357.3 2288.69   368.6 2288.51   478.2 2288.78   567.8 2292.64
   607.6 2294.78   647.5 2297.68   667.4 2300.55   687.3 2305.09   727.2 2315.23
   816.8  2339.5   876.6 2355.16   886.6  2358.3   896.5 2362.74   916.4 2373.31
   926.4 2377.54   936.4 2381.09   946.3 2384.21   966.3 2389.62  1006.1 2398.63
#Mann= 3 , 0 , 0
       0      .1       0   357.3    .045       0   478.2      .1       0
Bank Sta=357.3,478.2
XS Rating Curve= 0 ,0
Exp/Cntr=0.3,0.1

Type RM Length L Ch R = 1 ,115297.4,1332.4,1311.6,1290.7
XS GIS Cut Line= 2
     2020858.917      383840.836     2022300.732      383762.405
#Sta/Elev= 30
       0 2501.41    39.8 2491.11    79.7 2482.46   159.3 2467.42   209.1 2459.61
     229 2454.79   298.8 2434.46   348.5 2417.42   378.4 2405.98   388.4 2403.64
   418.2 2400.84   448.1 2391.98   517.8 2372.77   577.6 2354.58   637.3 2333.43
     707 2310.77     727 2308.04   766.8 2305.98   976.4 2288.98  1093.6 2288.49
  1105.4 2288.59  1115.3 2289.53  1125.3 2291.81  1165.1 2302.81  1234.8 2324.98
  1294.6 2346.15  1404.1 2386.96    1424 2393.81    1434 2398.15    1444 2403.47
#Mann= 3 , 0 , 0
       0      .1       0   976.4    .045       0  1105.4      .1       0
Bank Sta=976.4,1105.4
XS Rating Curve= 0 ,0
Exp/Cntr=0.3,0.1

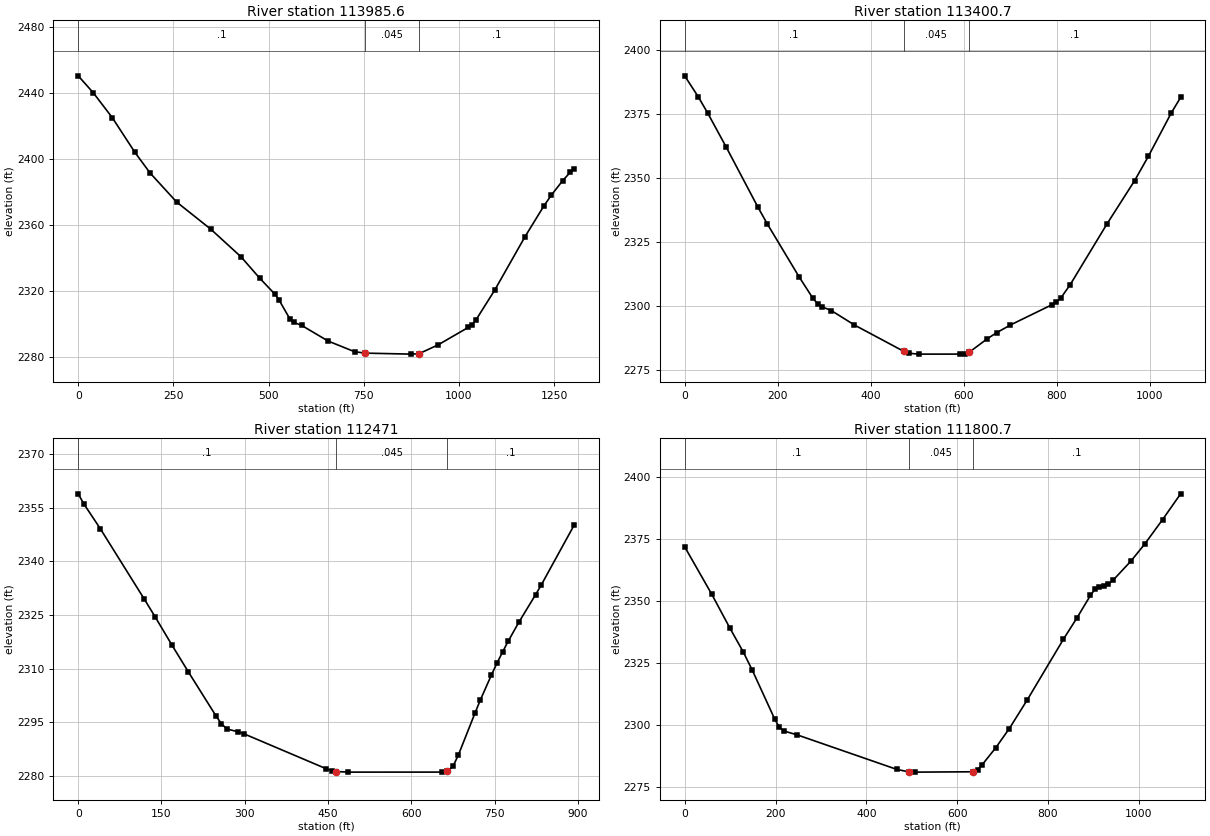
Type RM Length L Ch R = 1 ,113985.6,583.6,584.9,586.4
XS GIS Cut Line= 2
     2022195.503      385273.296     2022909.868       384184.33
#Sta/Elev= 30
       0 2450.28    39.8 2439.97    89.5 2424.97   149.1 2403.91   188.9 2391.45
   258.5 2373.92     348 2357.53   427.5  2340.8   477.2 2327.72     517 2318.08
   526.9 2314.87   556.7 2302.88   566.7 2301.08   586.6 2299.32   656.2 2289.84
   725.8 2283.38   753.7 2282.52   874.9 2281.92   894.8 2282.16   944.5 2287.45
    1024 2298.04  1033.9 2299.74  1043.9 2302.38  1093.6 2320.57  1173.1 2352.86
  1222.8 2371.53  1242.7 2378.17  1272.5 2386.93  1292.4    2392  1302.4 2393.93
#Mann= 3 , 0 , 0
       0      .1       0   753.7    .045       0   894.8      .1       0
Bank Sta=753.7,894.8
XS Rating Curve= 0 ,0
Exp/Cntr=0.3,0.1

Type RM Length L Ch R = 1 ,113400.7,932.5,929.7,926.7
XS GIS Cut Line= 3
     2022826.042       385321.57      2023130.61      384896.851
       2023463.4      384466.606
#Sta/Elev= 30
       0 2390.05    29.6 2381.72    49.3 2375.54    88.8 2362.33   157.8 2338.54
   177.5 2332.14   246.5 2311.23   276.1 2302.89     286 2300.82   295.8 2299.61
   315.6 2298.14   364.9 2292.53   471.2  2282.2   483.2 2281.44   502.9 2281.11
   591.9 2281.12   601.8 2281.23   611.6  2281.8   651.2 2287.18     671  2289.5
   700.6 2292.52   789.7 2300.43   799.6 2301.53   809.4 2303.19   829.2 2308.32
   908.3  2332.1   967.7 2349.03   997.3 2358.57  1046.8 2375.62  1066.6  2381.6
#Mann= 3 , 0 , 0
       0      .1       0   471.2    .045       0   611.6      .1       0
Bank Sta=471.2,611.6
XS Rating Curve= 0 ,0
Exp/Cntr=0.3,0.1

Type RM Length L Ch R = 1 ,112471  ,671.3,670.3,669.4
XS GIS Cut Line= 2
     2023703.055      385717.625     2024150.493      384944.352
#Sta/Elev= 30
       0 2358.82     9.9 2356.06    39.7 2349.11   119.1  2329.4     139 2324.36
   168.8  2316.6   198.5 2309.08   248.2  2296.8   258.1 2294.59     268 2293.16
   287.9 2292.37   297.8 2291.86   446.7 2282.06   456.6 2281.54   464.5 2281.28
   486.4 2281.11   655.2 2281.12   665.1 2281.37     675 2282.69   684.9 2285.91
   714.7 2297.57   724.6 2301.32   744.5 2308.29   754.4 2311.56   764.4 2314.64
   774.3 2317.59   794.1 2323.05   823.9 2330.65   833.8 2333.28   893.4 2350.09
#Mann= 3 , 0 , 0
       0      .1       0   464.5    .045       0   665.1      .1       0
Bank Sta=464.5,665.1
XS Rating Curve= 0 ,0
Exp/Cntr=0.3,0.1

Type RM Length L Ch R = 1 ,111800.7,754.2,757.1,760
XS GIS Cut Line= 3
     2024350.363      385963.258     2024604.661      385480.092
     2024858.959      384996.927
#Sta/Elev= 30
       0 2371.84    59.6 2352.74    99.3 2339.19     129 2329.49   148.9 2322.15
   198.6 2302.32   208.5 2299.14   218.4 2297.68   248.2 2296.08   466.6 2282.24
   494.5 2281.16   506.3 2281.11   635.4 2281.25   645.3 2282.13   655.2 2284.12
     685 2290.94   714.8 2298.65   754.5 2310.25   833.9 2334.61   863.7  2343.2
   893.4 2352.24   903.4 2354.75   913.3 2355.76   923.2 2356.11   933.2 2356.88
   943.1 2358.35   982.8 2366.14  1012.6 2372.86  1052.3  2382.8    1092 2393.17
#Mann= 3 , 0 , 0
       0      .1       0   494.5    .045       0   635.4      .1       0
Bank Sta=494.5,635.4
XS Rating Curve= 0 ,0
Exp/Cntr=0.3,0.1