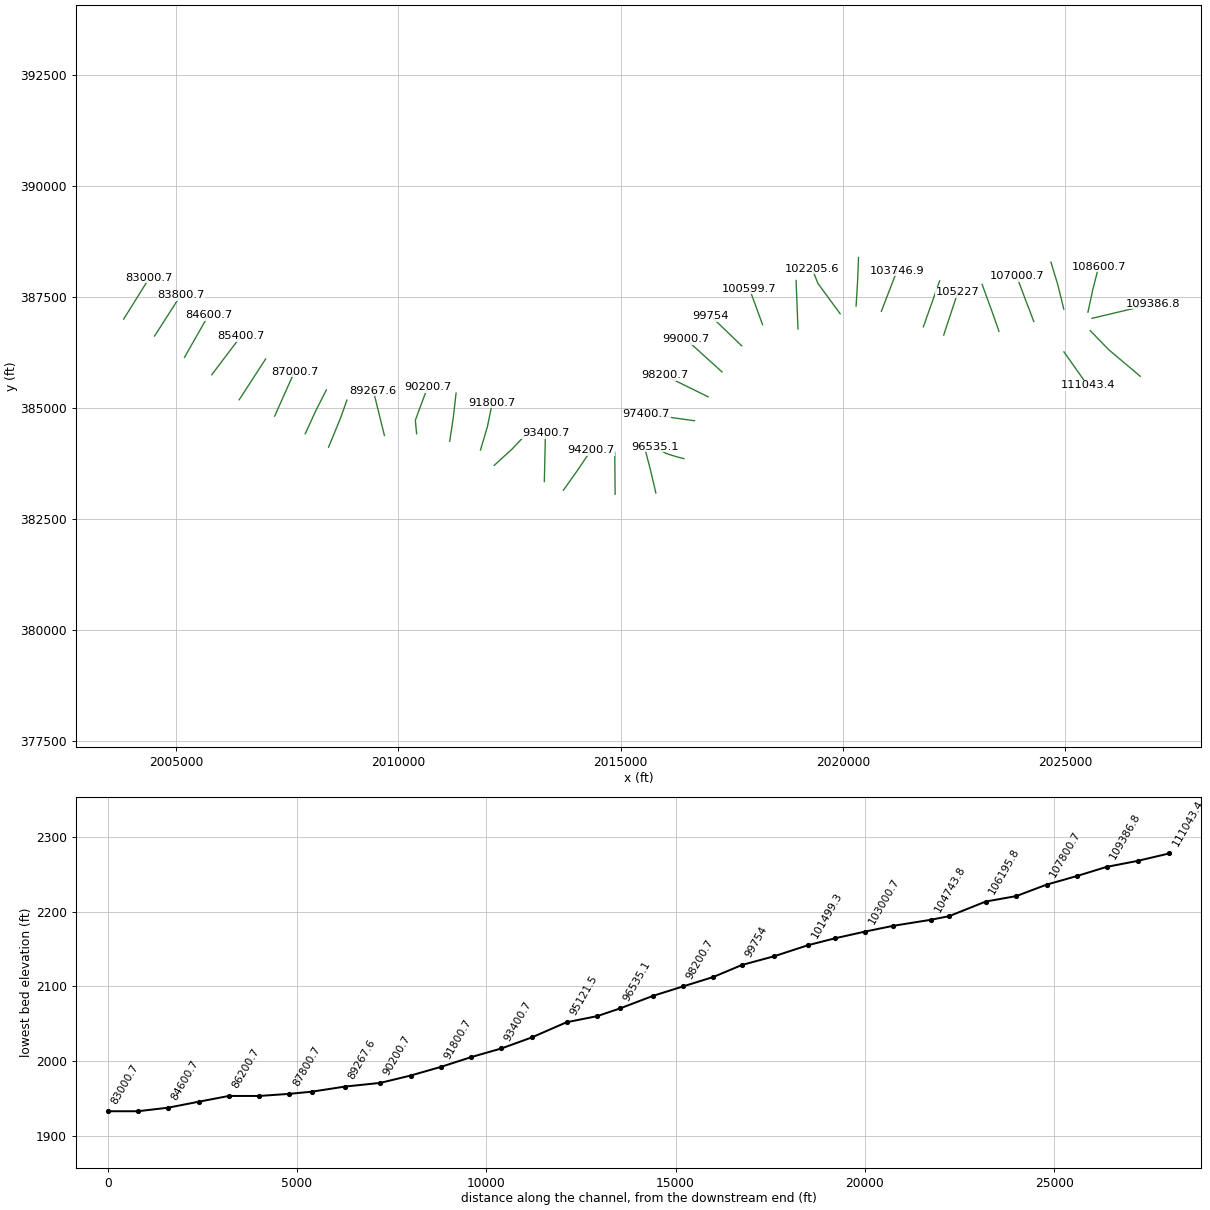
HEC-RAS study MeadowRvr.prj: MeadowRvr

--- MeadowRvr.g01 (geometry) --- (continued)

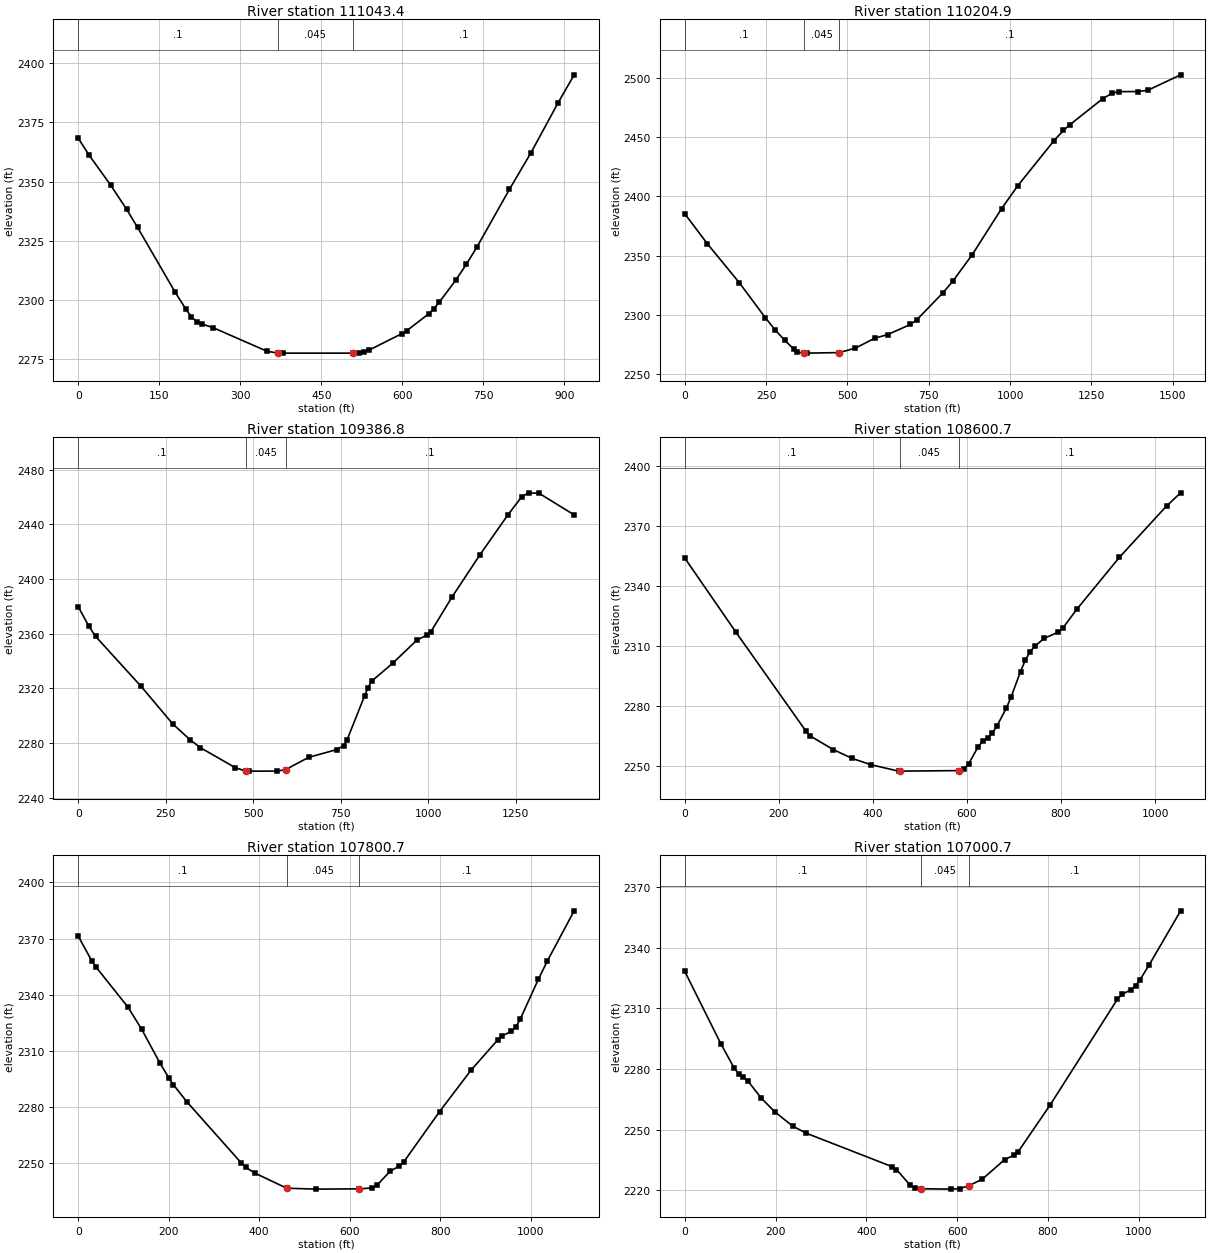
Type RM Length L Ch R = 1 ,111043.4,835,838.7,842.4
XS GIS Cut Line= 2
     2024969.194      386260.421     2025498.826      385510.703
#Sta/Elev= 30
       0 2368.36      20 2361.25    59.9  2348.6    89.8 2338.26   109.8  2330.7
   179.6 2303.26   199.6 2296.06   209.5 2292.92   219.5 2290.88   229.5 2289.86
   249.4 2288.39   349.2 2278.43   369.2 2277.64   379.1 2277.61   508.8 2277.61
   518.8 2277.64   528.8 2278.09   538.8 2278.94   598.6 2285.79   608.6 2287.16
   648.5 2294.17   658.5 2296.44   668.5 2299.18   698.4  2308.3   718.4 2315.12
   738.3 2322.52   798.2  2346.8   838.1 2362.27     888 2383.24   917.9 2395.12
#Mann= 3 , 0 , 0
       0      .1       0   369.2    .045       0   508.8      .1       0
Bank Sta=369.2,508.8
XS Rating Curve= 0 ,0
Exp/Cntr=0.3,0.1

Type RM Length L Ch R = 1 ,110204.9,794.7,818.1,841.4
XS GIS Cut Line= 3
     2025560.643      386739.574     2025973.174      386312.483
     2026684.629      385713.185
#Sta/Elev= 30
       0 2385.36    69.3 2360.06   168.2 2326.94   247.4 2297.66   277.1  2287.5
   306.8 2278.56   336.5 2270.76   346.4 2268.65   365.8 2267.63   376.1 2267.61
     475 2268.07   524.5 2271.84   583.9 2280.16   623.8 2283.27   693.8  2291.8
   713.8 2295.94   793.8 2318.56   823.8 2328.28   883.9 2350.82   973.9 2389.61
  1023.9 2409.02  1133.9  2446.6  1163.9 2455.64  1183.9 2460.46    1284 2482.25
    1314 2487.07    1334 2488.33    1394  2488.4    1424 2489.57    1524 2502.52
#Mann= 3 , 0 , 0
       0      .1       0   365.8    .045       0     475      .1       0
Bank Sta=365.8,475
XS Rating Curve= 0 ,0
Exp/Cntr=0.3,0.1

Type RM Length L Ch R = 1 ,109386.8,760.7,786.1,810.7
XS GIS Cut Line= 2
      2025599.47      387016.212     2026977.889      387343.031
#Sta/Elev= 30
       0  2379.8    29.9 2365.73    49.9 2358.01   179.6 2321.55   269.4 2294.26
   319.2 2282.59   349.2 2276.73   448.9 2262.08   478.9 2259.65   488.8  2259.6
   568.6 2259.62   592.7 2260.74   658.4 2269.69   738.2 2275.32   758.2 2278.24
   768.2 2282.63   818.1 2314.68     828 2320.69     838 2325.31   897.9 2338.37
   967.7 2355.41   997.6 2359.23  1007.6 2361.58  1067.5 2386.76  1147.3 2417.67
  1227.1 2446.78    1267  2460.2  1286.9 2463.01  1316.9 2462.61  1416.6 2446.89
#Mann= 3 , 0 , 0
       0      .1       0   478.9    .045       0   592.7      .1       0
Bank Sta=478.9,592.7
XS Rating Curve= 0 ,0
Exp/Cntr=0.3,0.1

Type RM Length L Ch R = 1 ,108600.7,789.8,800,812.3
XS GIS Cut Line= 3
     2025508.475      387154.566     2025616.371      387656.956
     2025750.334      388180.623
#Sta/Elev= 30
       0 2354.14   108.7 2317.03   256.9 2267.71   266.8    2265   316.2 2258.12
   355.7 2253.77   395.3 2250.62   454.6 2247.37   456.8 2247.37   583.9 2247.64
   593.9  2248.5   603.9 2251.08     624 2259.65     634 2262.39     644 2263.89
     654 2266.36     664 2270.03     684 2278.97     694 2284.51     714 2297.24
     724 2302.81   734.1 2307.02   744.1 2309.86   764.1 2313.85   794.1 2316.93
   804.1 2319.07   834.2 2328.58   924.2 2354.42  1024.4 2380.12  1054.4 2386.74
#Mann= 3 , 0 , 0
       0      .1       0   456.8    .045       0   583.9      .1       0
Bank Sta=456.8,583.9
XS Rating Curve= 0 ,0
Exp/Cntr=0.3,0.1

Type RM Length L Ch R = 1 ,107800.7,797.2,800,801.5
XS GIS Cut Line= 3
     2024965.167      387223.521     2024834.175      387758.489
     2024676.623      388280.384
#Sta/Elev= 30
       0 2371.32      30 2358.03    40.1 2354.52   110.2 2333.21   140.2 2321.45
   180.2 2303.53   200.3 2295.34   210.3 2291.78   240.3 2282.58   360.5 2249.86
   370.5  2247.5   390.6 2244.45   460.6  2236.4   525.7  2235.9   620.2 2236.05
   649.9 2236.54   659.8 2237.87   689.5 2245.56   709.4 2248.17   719.3 2250.44
   798.6 2277.42     868 2299.55   927.4 2315.86   937.3 2318.01   957.2 2320.27
   967.1 2322.67     977    2327  1016.6 2348.09  1036.5 2357.92  1095.9 2384.83
#Mann= 3 , 0 , 0
       0      .1       0   460.6    .045       0   620.2      .1       0
Bank Sta=460.6,620.2
XS Rating Curve= 0 ,0
Exp/Cntr=0.3,0.1

Type RM Length L Ch R = 1 ,107000.7,805.2,804.9,804.7
XS GIS Cut Line= 3
     2024290.347      386945.251     2024096.195      387455.301
     2023903.611       387966.48
#Sta/Elev= 30
       0 2328.33    79.4 2292.56   109.2 2280.37   119.1 2277.58     129 2276.24
   138.9 2274.14   168.7 2265.59   198.5  2258.8   238.2 2251.71   267.9 2248.24
   456.4 2231.75   466.4  2230.3   496.1 2222.68   506.1 2221.26   520.7 2220.82
   585.5 2220.62   605.3 2220.89   625.2 2222.25     655 2225.49   704.7 2235.25
   724.5 2237.33   734.5 2239.17     804 2261.97     953 2314.53   962.9 2316.86
   982.8 2319.19   992.7 2321.13  1002.6 2324.12  1022.5 2331.34    1092 2358.17
#Mann= 3 , 0 , 0
       0      .1       0   520.7    .045       0   625.2      .1       0
Bank Sta=520.7,625.2
XS Rating Curve= 0 ,0
Exp/Cntr=0.3,0.1

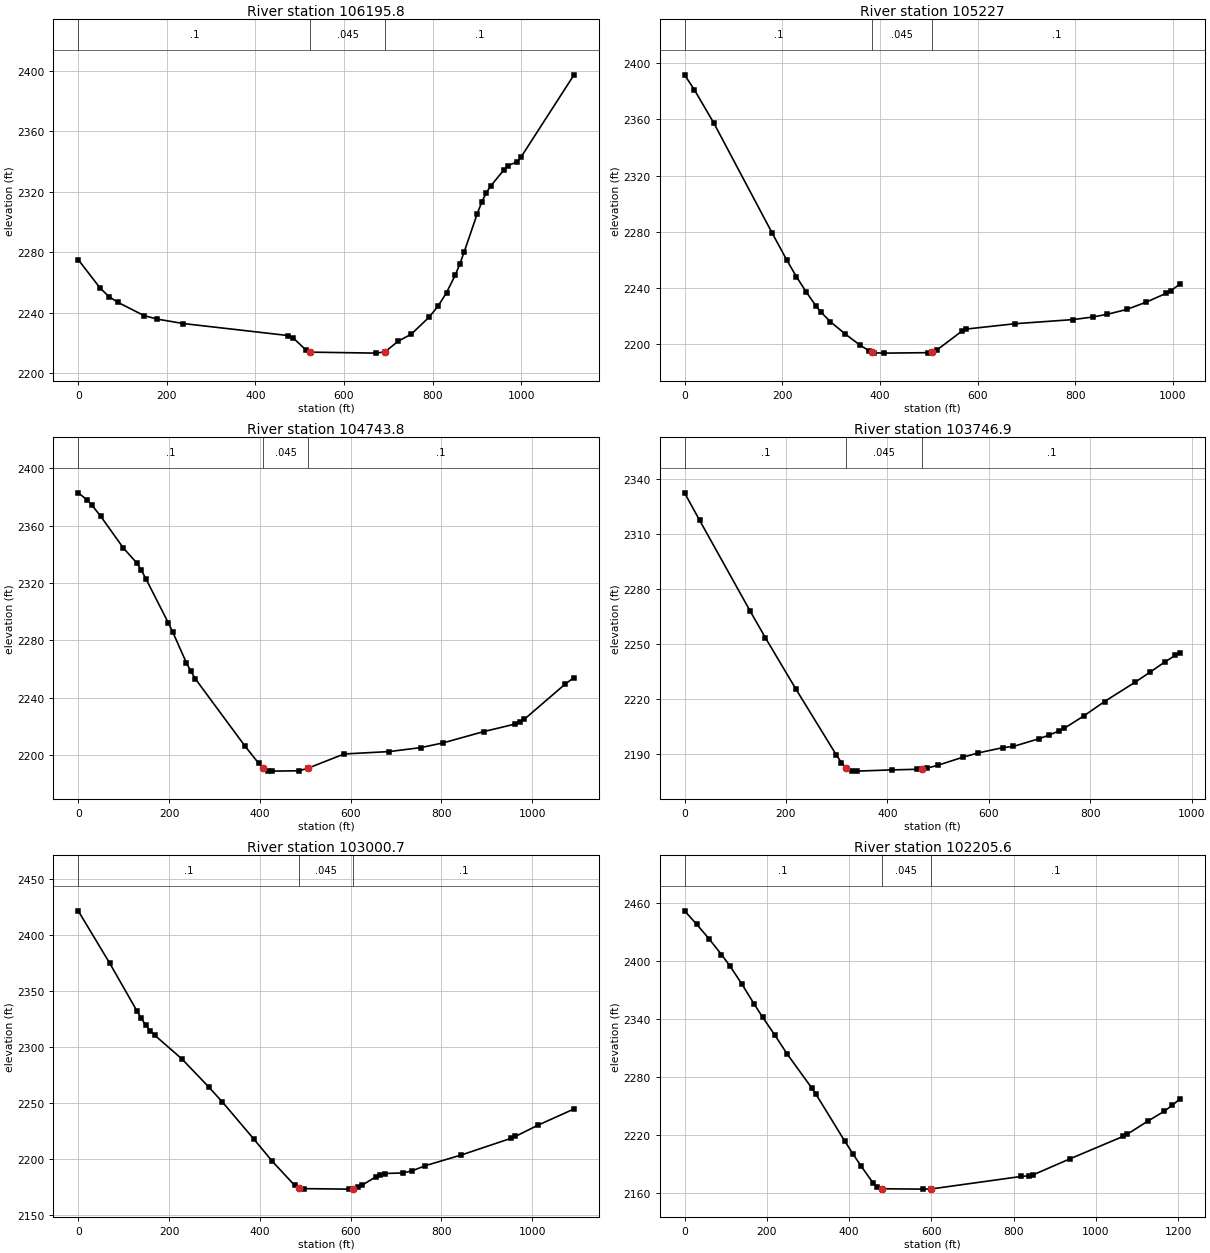
Type RM Length L Ch R = 1 ,106195.8,983.8,968.7,953.6
XS GIS Cut Line= 3
     2023507.696      386725.014     2023342.683      387190.931
     2023128.498      387778.116
#Sta/Elev= 30
       0 2275.23    49.4 2256.44    69.2 2250.78      89 2247.07   148.3 2238.23
   177.9  2235.9   237.2 2232.94   474.5 2224.98   484.4 2223.63   514.1  2215.5
     524 2214.02   672.8 2213.37   692.7 2214.27   722.5 2221.28   752.2 2225.97
   791.9 2237.13   811.8 2244.22   831.6 2253.45   851.4 2265.14   861.4 2272.27
   871.3 2280.34     901 2305.73     911  2313.3   920.9 2319.34   930.8 2323.77
   960.6 2334.53   970.5 2337.45   990.3 2339.86  1000.2 2343.33  1119.3 2397.49
#Mann= 3 , 0 , 0
       0      .1       0     524    .045       0   692.7      .1       0
Bank Sta=524,692.7
XS Rating Curve= 0 ,0
Exp/Cntr=0.3,0.1

Type RM Length L Ch R = 1 ,105227  ,483.8,483.3,482.8
XS GIS Cut Line= 2
     2022264.407      386640.433     2022582.391      387604.461
#Sta/Elev= 30
       0 2391.59    19.9 2381.08    59.7 2357.45   179.1 2279.32     209 2260.15
   228.9 2248.21   248.8 2237.42   268.7 2227.51   278.7 2223.19   298.6 2216.12
   328.4 2207.56   358.3 2199.72   378.2  2195.3   384.3 2194.52   388.1 2194.04
     408 2193.81   497.6 2194.14   507.6 2194.69   517.5 2196.26   567.3  2209.3
   577.2 2210.93   676.8 2214.71   796.2 2217.67     836  2219.5   865.8 2221.44
   905.6 2224.87   945.4 2230.08   985.3  2236.2   995.2 2238.13  1015.1 2243.04
#Mann= 3 , 0 , 0
       0      .1       0   384.3    .045       0   507.6      .1       0
Bank Sta=384.3,507.6
XS Rating Curve= 0 ,0
Exp/Cntr=0.3,0.1

Type RM Length L Ch R = 1 ,104743.8,997.4,996.8,996.2
XS GIS Cut Line= 3
     2021807.509      386827.688      2021989.91       387342.32
     2022172.311      387856.951
#Sta/Elev= 30
       0 2382.86    19.8 2377.93    29.8 2374.46    49.6 2366.52    99.3 2344.47
     129 2334.01     139 2328.97   148.9 2323.09   198.6  2292.2   208.5 2285.69
   238.2 2264.52   248.2 2258.46   258.1 2253.23   367.3 2206.46   397.1 2194.58
     407 2191.16     417 2189.36   426.9    2189   486.4 2189.24   506.3 2191.08
   585.7 2200.95     685 2202.62   754.5 2205.38   804.1 2208.71   893.4 2216.57
     963 2221.84   972.9 2223.05   982.8  2225.2  1072.2 2249.54    1092 2254.15
#Mann= 3 , 0 , 0
       0      .1       0     407    .045       0   506.3      .1       0
Bank Sta=407,506.3
XS Rating Curve= 0 ,0
Exp/Cntr=0.3,0.1

Type RM Length L Ch R = 1 ,103746.9,739.3,746.2,753.6
XS GIS Cut Line= 2
     2020861.718      387174.125      2021212.89      388086.729
#Sta/Elev= 30
       0 2332.67    29.9 2317.59   129.7 2268.03   159.6 2253.56   219.5  2225.7
   299.3 2189.75   309.3 2185.58   319.3 2182.43   329.3 2180.97   339.2 2180.91
   409.1 2181.58     459 2181.92     469 2182.13   478.9 2182.59   498.9 2184.05
   548.8 2188.49   578.7 2190.81   628.6 2193.77   648.6 2194.38   698.5 2198.54
   718.4  2200.5   738.4  2202.8   748.4  2204.2   788.3 2211.17   828.2 2218.85
     888  2229.3     918 2234.87   947.9 2240.59   967.9 2244.04   977.8 2245.58
#Mann= 3 , 0 , 0
       0      .1       0   319.3    .045       0     469      .1       0
Bank Sta=319.3,469
XS Rating Curve= 0 ,0
Exp/Cntr=0.3,0.1

Type RM Length L Ch R = 1 ,103000.7,779.5,795.1,810.3
XS GIS Cut Line= 3
     2020293.697      387292.898     2020326.645      387838.034
     2020348.762      388383.563
#Sta/Elev= 30
       0 2421.22    69.5 2374.46   129.1 2332.17     139 2325.32   148.9 2319.09
   158.9 2314.12   168.8 2310.23   228.4 2289.21     288    2264   317.8 2250.72
   387.3 2217.56     427 2198.18   476.6 2176.58   486.6 2173.93   496.5 2173.59
   595.8 2173.16   605.7 2173.47   615.6 2174.72   625.6 2176.78   655.3 2184.04
   665.2 2186.11   675.2 2187.06   714.9 2187.62   734.7 2189.34   764.5 2194.05
   843.9  2203.6   953.1 2218.42   963.1 2220.15  1012.7 2230.17  1092.1 2244.61
#Mann= 3 , 0 , 0
       0      .1       0   486.6    .045       0   605.7      .1       0
Bank Sta=486.6,605.7
XS Rating Curve= 0 ,0
Exp/Cntr=0.3,0.1

Type RM Length L Ch R = 1 ,102205.6,719.7,706.3,692.9
XS GIS Cut Line= 3
     2019935.283      387118.889     2019433.881       387802.82
     2019302.554       388135.33
#Sta/Elev= 30
       0 2452.09    29.9 2437.98    59.9 2422.92    89.8 2406.87   109.8 2395.41
   139.7 2376.13   169.6 2355.44   189.6 2342.17   219.5 2323.55   249.4 2304.04
   309.3 2268.81   319.3 2262.52   389.1 2214.13     409  2200.9     429 2188.14
   458.9 2170.27   468.9 2166.15   478.9 2164.56   578.7 2164.19   598.6 2164.31
   818.1 2177.29   838.1 2178.04     848 2179.07   937.4  2195.6  1066.5 2218.77
  1076.4    2221  1126.1 2234.48  1165.8 2244.63  1185.7 2250.88  1205.5 2257.87
#Mann= 3 , 0 , 0
       0      .1       0   478.9    .045       0   598.6      .1       0
Bank Sta=478.9,598.6
XS Rating Curve= 0 ,0
Exp/Cntr=0.3,0.1

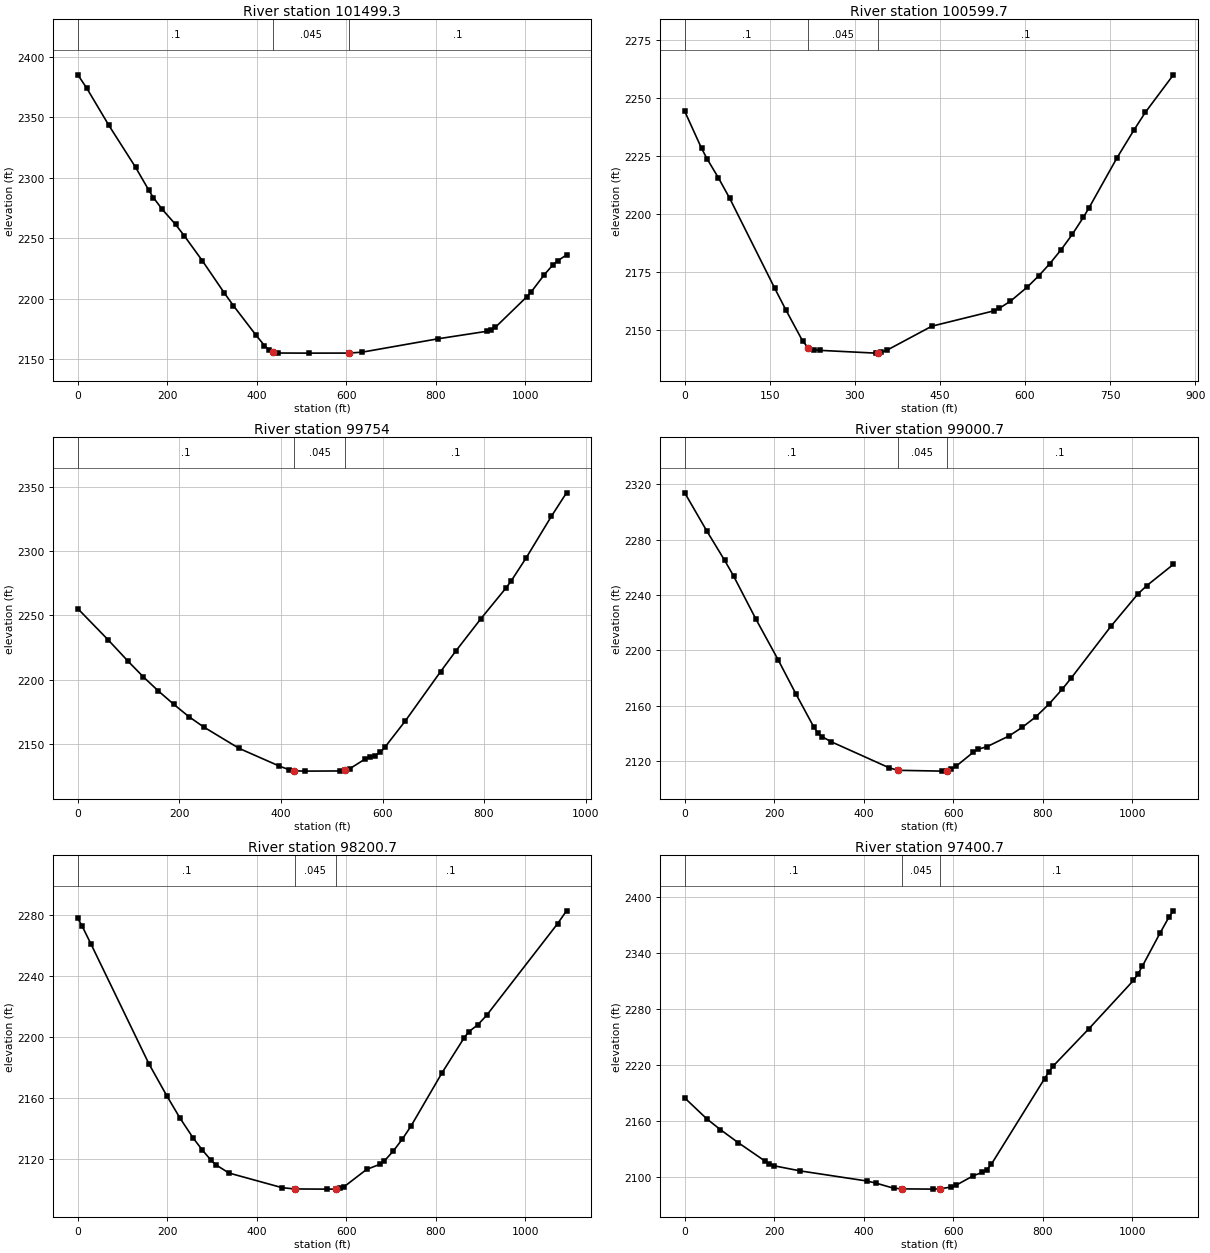
Type RM Length L Ch R = 1 ,101499.3,892.6,899.6,906.6
XS GIS Cut Line= 3
     2018986.563        386777.7     2018965.169       387323.28
     2018943.774      387868.861
#Sta/Elev= 30
       0 2385.16    19.8 2374.18    69.5 2343.26     129  2308.7   158.8  2289.6
   168.8 2283.64   188.6 2273.93   218.4 2261.42   238.2 2251.87     278 2231.54
   327.6 2204.63   347.4  2194.4   397.1 2170.38     417 2161.29   426.9 2157.78
   436.8 2155.77   446.7 2155.13   516.2 2155.04   605.6 2155.08   635.4 2155.84
   804.1 2166.85   913.3 2173.06   923.2 2174.01   933.2 2176.47  1002.6 2201.38
  1012.6 2205.42  1042.4 2219.92  1062.2 2228.22  1072.2  2231.4    1092 2236.23
#Mann= 3 , 0 , 0
       0      .1       0   436.8    .045       0   605.6      .1       0
Bank Sta=436.8,605.6
XS Rating Curve= 0 ,0
Exp/Cntr=0.3,0.1

Type RM Length L Ch R = 1 ,100599.7,835.5,845.7,856
XS GIS Cut Line= 2
     2018190.462      386872.351       2017894.6      387681.535
#Sta/Elev= 30
       0 2244.15    29.7 2228.22    39.6 2223.64    59.4 2215.55    79.2 2206.81
   158.4 2168.24   178.3  2158.8     208 2145.37   217.9 2142.42   227.8 2141.65
   237.7 2141.41   336.7 2140.21   340.6 2140.34   346.6 2140.54   356.5 2141.46
   435.7 2151.79   544.7 2158.35   554.6 2159.47   574.4 2162.55   604.1 2168.62
   623.9 2173.36   643.7 2178.66   663.5 2184.61   683.3 2191.24   703.1 2198.67
     713 2202.73   762.5 2224.29   792.2 2236.14   812.1 2243.69   861.6 2259.83
#Mann= 3 , 0 , 0
       0      .1       0   217.9    .045       0   340.6      .1       0
Bank Sta=217.9,340.6
XS Rating Curve= 0 ,0
Exp/Cntr=0.3,0.1

Type RM Length L Ch R = 1 ,99754   ,752.6,753.3,754
XS GIS Cut Line= 2
     2017721.036      386397.337     2017028.074      387065.151
#Sta/Elev= 30
       0 2255.27    59.5 2231.04    99.2 2214.21     129 2202.11   158.7 2191.09
   188.5 2180.86   218.3 2171.22     248 2163.02   317.5  2146.4   396.9 2132.57
   416.7 2129.66   426.6 2128.91   446.5 2128.65   515.9 2128.79   526.4 2129.36
   535.8  2130.6   565.5 2138.03   575.4 2139.83   585.4 2140.83   595.3  2143.2
   605.2 2147.53   644.9 2167.76   714.3 2206.17   744.1 2222.12   793.7 2247.44
   843.3 2271.46   853.2 2276.77     883 2294.93   932.6 2327.29   962.4  2345.6
#Mann= 3 , 0 , 0
       0      .1       0   426.6    .045       0   526.4      .1       0
Bank Sta=426.6,526.4
XS Rating Curve= 0 ,0
Exp/Cntr=0.3,0.1

Type RM Length L Ch R = 1 ,99000.7 ,793.7,800,806.3
XS GIS Cut Line= 3
     2017276.831      385811.961     2016872.134       386178.48
     2016467.437      386544.999
#Sta/Elev= 30
       0 2313.84    49.6  2286.1    89.4 2264.93   109.2 2253.71   158.8 2222.72
   208.5 2193.29   248.2 2168.62   287.9 2144.87   297.8 2140.12   307.8  2137.4
   327.6 2133.86   456.6 2115.11   476.5 2113.25   575.8 2112.66   585.7 2112.82
   595.6 2113.85   605.6 2116.01   645.3 2126.42   655.2 2128.44     675 2130.27
   724.7 2138.08   754.5 2144.38   784.2  2151.8     814 2161.11   843.8 2171.97
   863.7 2179.95     953  2217.6  1012.6 2240.68  1032.4 2246.71    1092  2262.1
#Mann= 3 , 0 , 0
       0      .1       0   476.5    .045       0   585.7      .1       0
Bank Sta=476.5,585.7
XS Rating Curve= 0 ,0
Exp/Cntr=0.3,0.1

Type RM Length L Ch R = 1 ,98200.7 ,792.8,800,807.3
XS GIS Cut Line= 3
     2016965.417      385250.914      2016475.41      385491.765
     2015985.403      385732.616
#Sta/Elev= 30
       0  2277.6     9.9 2272.36    29.8 2260.52   158.8 2182.25   198.6 2161.36
   228.3 2146.62   258.1 2133.42     278 2125.76   297.8 2118.94   307.8 2116.14
   337.5 2110.64   456.6 2100.99     485 2100.17   555.9 2100.06   575.8 2100.07
   585.7 2100.48   595.6 2101.78   645.3 2112.98     675 2116.34     685 2118.56
   704.8 2125.02   724.7 2132.66   744.6 2141.45     814 2176.42   863.7 2199.49
   873.6 2203.27   893.4 2207.74   913.3 2213.96  1072.2  2274.2    1092 2282.57
#Mann= 3 , 0 , 0
       0      .1       0     485    .045       0   575.8      .1       0
Bank Sta=485,575.8
XS Rating Curve= 0 ,0
Exp/Cntr=0.3,0.1

Type RM Length L Ch R = 1 ,97400.7 ,869.4,865.5,861.5
XS GIS Cut Line= 3
     2016658.238      384713.133       2016117.3      384787.346
     2015576.091      384859.507
#Sta/Elev= 30
       0 2184.95    49.6 2162.45    79.4 2151.16   119.1 2137.22   178.7 2117.61
   188.6 2114.57   198.6 2112.41   258.1 2106.84     407 2096.04   426.9 2093.85
   466.6 2088.34   486.4 2087.61   555.9 2087.34     571 2087.73   595.6  2089.6
   605.6 2091.31   645.3 2101.78   665.1 2105.22   675.1 2108.02     685 2113.79
   804.1 2205.56     814 2212.94     824  2219.4   903.4 2259.12  1002.7 2310.67
  1012.6 2317.45  1022.5 2325.83  1062.2 2361.43  1082.1 2378.48    1092 2385.22
#Mann= 3 , 0 , 0
       0      .1       0   486.4    .045       0     571      .1       0
Bank Sta=486.4,571
XS Rating Curve= 0 ,0
Exp/Cntr=0.3,0.1

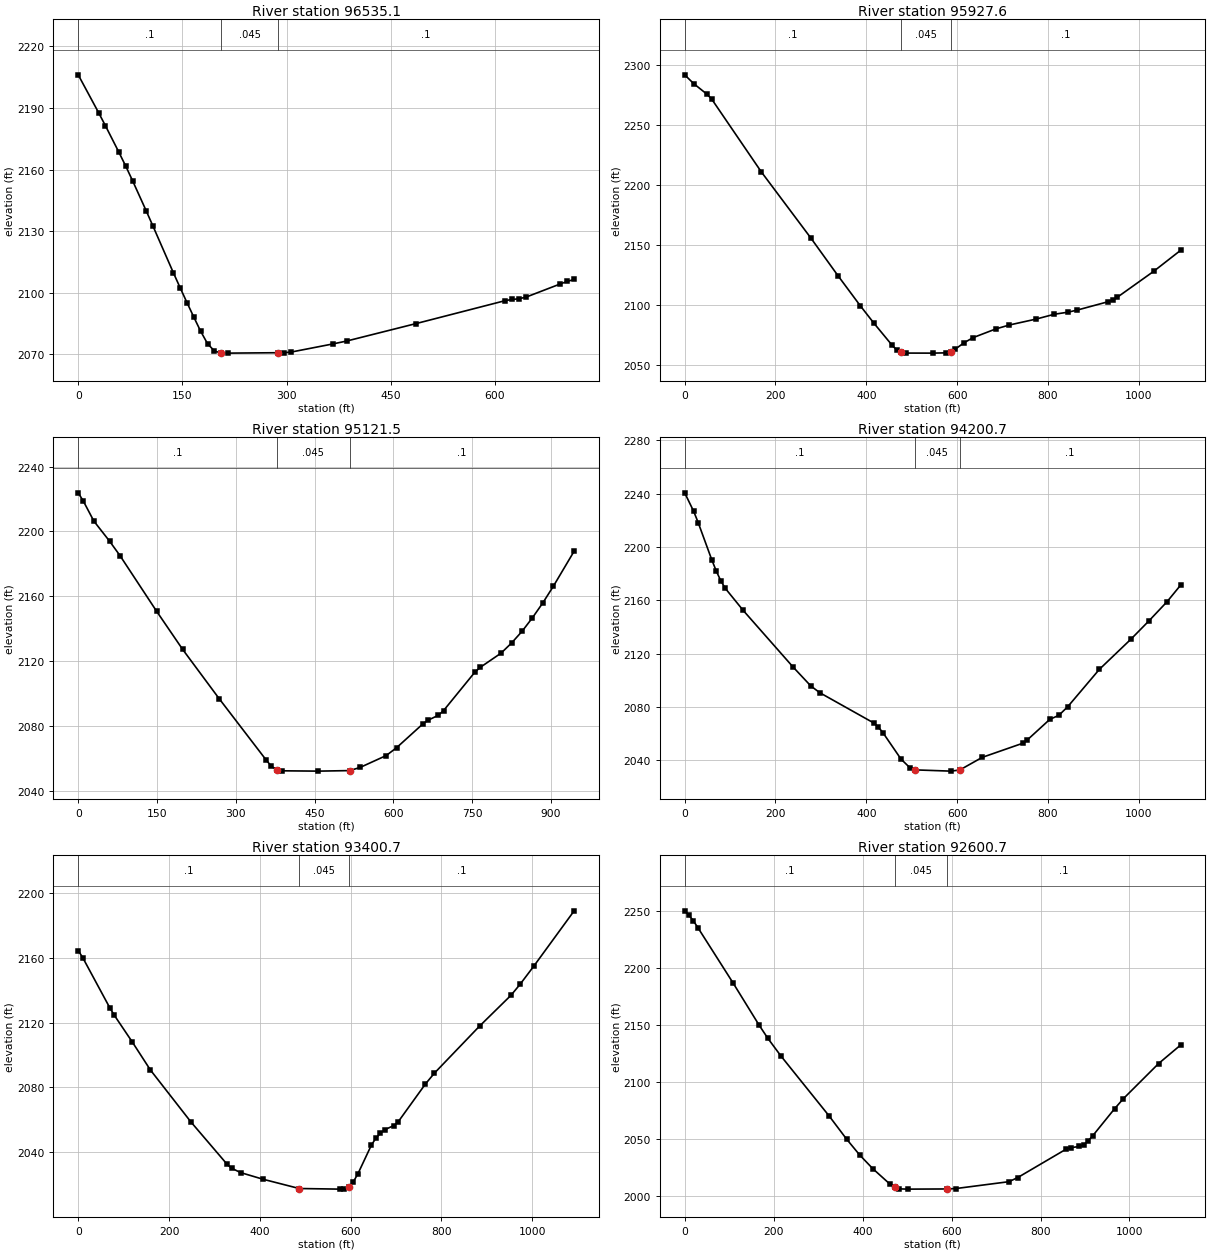
Type RM Length L Ch R = 1 ,96535.1 ,630.9,607.5,584.5
XS GIS Cut Line= 4
     2016418.938      383860.202     2016248.492       383904.91
     2016009.987      383980.436     2015765.095       384131.24
#Sta/Elev= 30
       0 2206.14    29.4 2187.69    39.2 2181.35    58.7 2168.37    68.5 2161.63
    78.3 2154.57    97.9 2139.92   107.7 2132.44     137 2109.79   146.8 2102.44
   156.6 2095.25   166.4 2088.22   176.2 2081.36   186.2 2075.25   196.2 2071.66
   206.2 2070.67   216.2 2070.66   287.5 2070.86   296.3 2070.88   306.3 2071.16
   366.4 2075.12   386.4 2076.54   485.9    2085   614.8 2096.22   624.7 2096.78
   634.6 2097.13   644.6 2097.91   694.2 2104.36   704.1 2105.57     714 2106.53
#Mann= 3 , 0 , 0
       0      .1       0   206.2    .045       0   287.5      .1       0
Bank Sta=206.2,287.5
XS Rating Curve= 0 ,0
Exp/Cntr=0.3,0.1

Type RM Length L Ch R = 1 ,95927.6 ,811.1,806.1,800.8
XS GIS Cut Line= 3
      2015789.71      383089.185     2015664.662      383620.638
     2015526.822       384149.15
#Sta/Elev= 30
       0 2292.04    19.8 2284.74    49.6 2275.73    59.6 2271.76   168.8 2211.21
     278 2156.08   337.5 2124.83   387.1 2099.57   416.9 2085.15   456.6 2066.97
   466.6 2063.06   476.5 2060.94   486.4 2060.35     546  2060.3   575.8 2060.54
   585.7 2061.49   595.6 2063.53   615.5 2068.99   635.3 2073.22     685 2080.43
   714.8  2083.7   774.4 2088.69   814.1 2092.68   843.9 2094.38   863.8 2096.08
   933.3 2103.19   943.2  2104.7   953.1 2106.92  1032.6 2128.34  1092.2  2145.9
#Mann= 3 , 0 , 0
       0      .1       0   476.5    .045       0   585.7      .1       0
Bank Sta=476.5,585.7
XS Rating Curve= 0 ,0
Exp/Cntr=0.3,0.1

Type RM Length L Ch R = 1 ,95121.5 ,935,920.8,907.2
XS GIS Cut Line= 2
     2014873.745      383061.061     2014865.362      384005.501
#Sta/Elev= 30
       0 2223.84     9.9 2218.64    29.8 2206.41    59.6 2194.08    79.5 2185.14
   149.1  2150.9   198.8 2127.31   268.4  2096.9   357.9 2059.08   367.8 2055.22
   377.8    2053   387.7  2052.4   457.3  2052.2     517 2052.53   536.9 2054.48
   586.6 2061.81   606.4 2066.66   656.2 2081.27   666.1 2083.59     686 2086.65
   695.9 2089.58   755.6  2113.3   765.5 2116.17   805.3 2124.97   825.2 2131.18
   845.1 2138.36   864.9 2146.71   884.8 2155.94   904.7 2166.12   944.5 2187.86
#Mann= 3 , 0 , 0
       0      .1       0   377.8    .045       0     517      .1       0
Bank Sta=377.8,517
XS Rating Curve= 0 ,0
Exp/Cntr=0.3,0.1

Type RM Length L Ch R = 1 ,94200.7 ,786.6,800,812.8
XS GIS Cut Line= 3
     2013710.087      383150.434     2014026.309      383595.489
     2014330.696      384049.056
#Sta/Elev= 30
       0 2240.53    19.8 2226.68    29.8 2218.16    59.6 2190.38    69.5 2181.95
    79.4 2174.67    89.3 2168.96     129 2152.31   238.2 2110.11   277.9 2095.68
   297.8  2090.6   416.9 2067.86   426.8 2064.79   436.8 2060.58   476.5 2040.84
   496.3  2034.3   506.2  2032.8   585.7 2031.85   605.6 2032.66   655.2 2042.16
   744.6 2052.76   754.5 2055.22   804.2 2070.68     824 2073.69   843.9 2080.27
   913.4 2108.22     983 2130.87  1022.7 2144.61  1062.4 2158.92  1092.2 2171.31
#Mann= 3 , 0 , 0
       0      .1       0   506.2    .045       0   605.6      .1       0
Bank Sta=506.2,605.6
XS Rating Curve= 0 ,0
Exp/Cntr=0.3,0.1

Type RM Length L Ch R = 1 ,93400.7 ,818.2,800,783.3
XS GIS Cut Line= 3
     2013280.999      383344.193     2013294.147      383890.301
     2013306.622      384436.112
#Sta/Elev= 30
       0 2164.49     9.9 2160.11    69.5 2129.16    79.5 2124.51   119.2 2107.98
   158.9 2090.78   248.3 2058.64   327.8 2032.56   337.7 2030.12   357.6 2027.41
   407.2 2023.29   486.7 2017.58     576  2017.2     586 2017.22   595.9 2018.43
   605.8 2021.69   615.8 2026.56   645.5 2044.29   655.5 2048.64   665.4 2051.67
   675.3  2053.9   695.2 2056.45   705.1 2058.92   764.6 2082.07   784.5 2088.81
   883.8  2117.8   953.2 2136.88   973.1 2143.62  1002.9 2154.67  1092.2 2188.98
#Mann= 3 , 0 , 0
       0      .1       0   486.7    .045       0   595.9      .1       0
Bank Sta=486.7,595.9
XS Rating Curve= 0 ,0
Exp/Cntr=0.3,0.1

Type RM Length L Ch R = 1 ,92600.7 ,787.7,800,812.7
XS GIS Cut Line= 3
     2012153.357      383707.804     2012552.384      384073.226
     2012948.123      384488.918
#Sta/Elev= 30
       0 2250.36     9.8 2246.37    19.7 2241.46    29.5 2235.68   108.2  2187.3
   167.2 2149.92   186.9 2138.28   216.4 2122.71   324.6 2070.04     364 2049.61
   393.5 2035.62     423 2023.58   462.4 2009.71   472.2 2007.11     482 2005.85
   501.7 2005.62   590.6 2005.77   610.3 2006.16   729.1 2012.17   748.9 2015.82
   857.7  2040.8   867.6 2042.04   887.4 2043.15   897.3 2044.73   907.2 2048.07
   917.1 2052.41   966.6 2076.35   986.4 2085.21  1065.5 2116.06    1115 2132.33
#Mann= 3 , 0 , 0
       0      .1       0   472.2    .045       0   590.6      .1       0
Bank Sta=472.2,590.6
XS Rating Curve= 0 ,0
Exp/Cntr=0.3,0.1

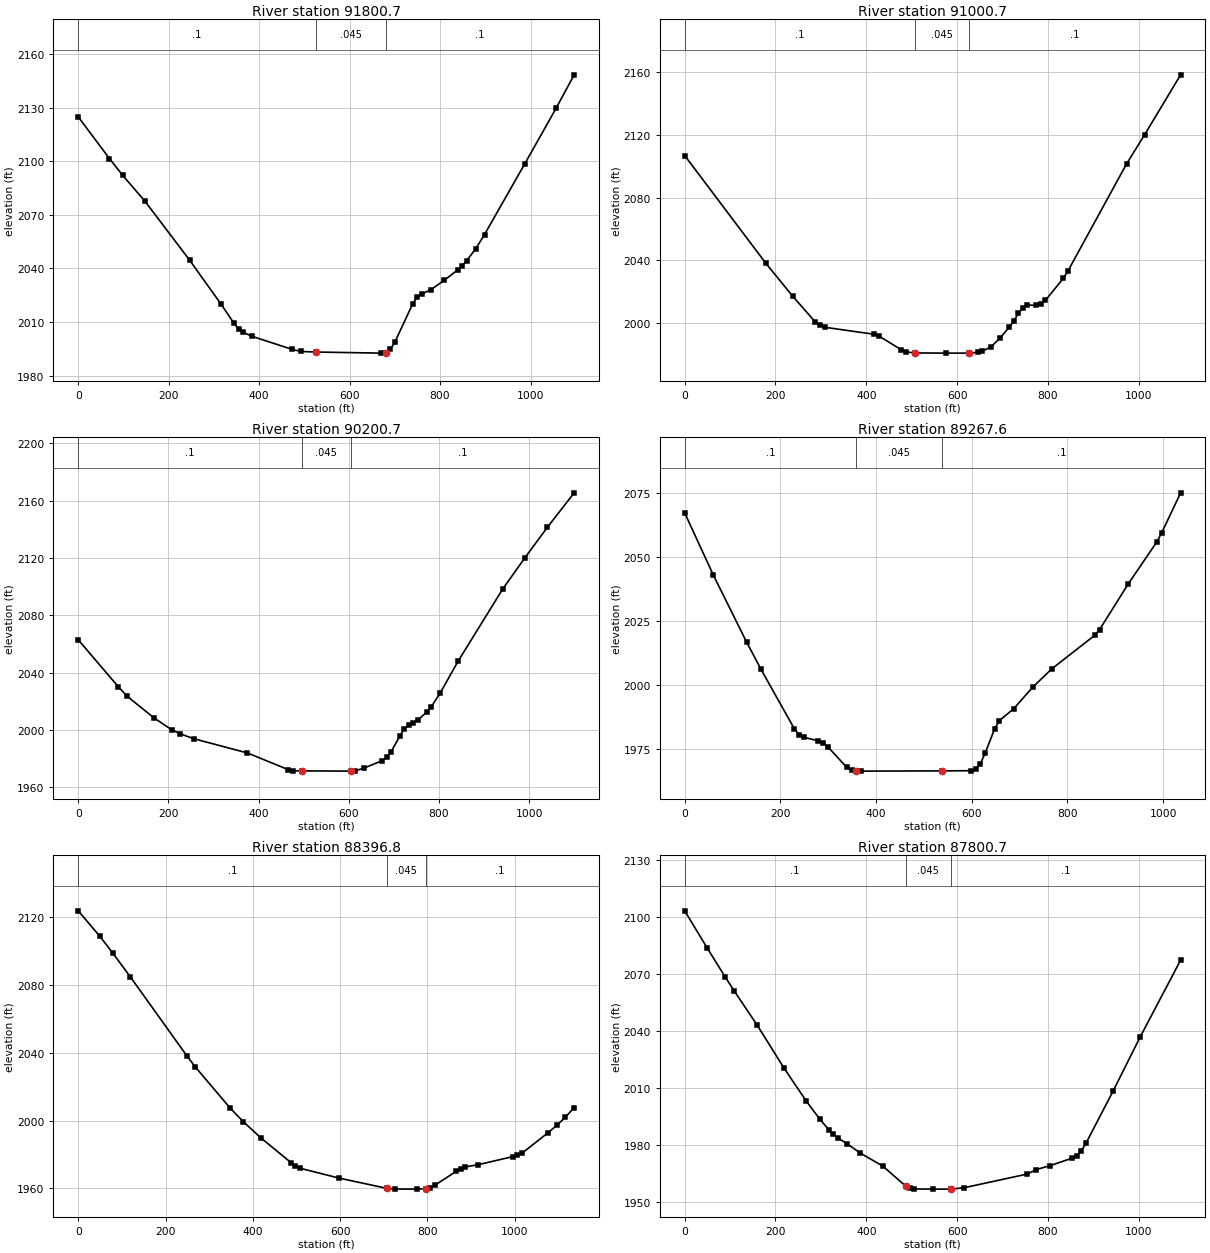
Type RM Length L Ch R = 1 ,91800.7 ,796.9,800,802
XS GIS Cut Line= 3
     2011845.596      384055.341     2012002.004       384584.12
     2012110.991      385118.154
#Sta/Elev= 30
       0 2124.89    68.9 2101.53    98.5 2092.05   147.7 2077.56   246.2 2044.65
   315.1 2020.22   344.6 2009.18   354.5 2006.06   364.3 2004.22     384 2001.98
   472.6 1994.67   492.3 1993.46   526.3 1993.15   670.3 1992.54   680.2 1992.85
   690.2 1994.73   700.1 1998.71   739.7 2020.24   749.6    2024   759.5 2025.66
   779.4 2028.02   809.1 2033.28   838.8 2039.11   848.7 2041.41   858.6 2044.28
   878.4 2050.81   898.3 2058.95   987.5 2098.63  1056.8 2129.77  1096.5 2148.39
#Mann= 3 , 0 , 0
       0      .1       0   526.3    .045       0   680.2      .1       0
Bank Sta=526.3,680.2
XS Rating Curve= 0 ,0
Exp/Cntr=0.3,0.1

Type RM Length L Ch R = 1 ,91000.7 ,804.6,800,794.4
XS GIS Cut Line= 3
     2011153.503      384252.161     2011234.504      384792.555
     2011295.915      385335.014
#Sta/Elev= 30
       0 2106.83   178.8 2038.21   238.4 2017.08   288.1 2000.72     298 1998.61
     308 1997.49   417.3 1993.01   427.2 1992.03   476.9 1983.14   486.8 1981.79
   506.7 1981.12   576.2    1981   625.8 1981.01   645.7 1981.49   655.6 1982.19
   675.5 1985.22   695.3  1990.8   715.2 1997.62   725.1 2001.57     735 2006.24
     745 2010.04   754.9 2011.66   774.7 2011.36   784.6  2012.2   794.6  2014.6
   834.3 2028.74   844.2 2033.29   973.2 2101.45    1013 2120.04  1092.4 2158.22
#Mann= 3 , 0 , 0
       0      .1       0   506.7    .045       0   625.8      .1       0
Bank Sta=506.7,625.8
XS Rating Curve= 0 ,0
Exp/Cntr=0.3,0.1

Type RM Length L Ch R = 1 ,90200.7 ,919.8,933.1,946.7
XS GIS Cut Line= 4
     2010408.629      384419.695     2010380.198       384723.88
     2010465.616      384958.628     2010657.703      385468.402
#Sta/Elev= 30
       0 2062.92    88.7  2030.2   108.4  2023.5   167.5 2008.52     207 2000.17
   226.7 1997.22   256.2 1993.84   375.5 1983.89   465.4 1972.32   475.4 1971.51
   495.4 1971.39   604.8 1971.22   614.8 1971.48   634.6 1973.41   674.2 1978.55
   684.1 1980.78     694 1984.71   713.8 1995.93   723.7 2000.93   733.6 2003.64
   743.5 2004.86   753.4 2006.91   773.2 2012.43   783.1  2016.1   802.9 2025.71
   842.6 2047.91   941.6  2098.3   991.1 2120.24  1040.6 2141.33  1100.1 2165.45
#Mann= 3 , 0 , 0
       0      .1       0   495.4    .045       0   604.8      .1       0
Bank Sta=495.4,604.8
XS Rating Curve= 0 ,0
Exp/Cntr=0.3,0.1

Type RM Length L Ch R = 1 ,89267.6 ,884.4,870.7,857.3
XS GIS Cut Line= 2
     2009684.913      384379.924     2009435.354      385385.973
#Sta/Elev= 30
       0 2067.08    59.8 2042.84   129.6 2016.58   159.5 2006.03   229.2  1982.8
   239.2 1980.48   249.2 1979.47   279.1 1978.14     289 1977.31     299 1975.83
   338.9 1967.72   348.8 1966.62   358.8 1966.31   368.8 1966.29   538.2 1966.38
     598 1966.46     608 1966.95   617.9  1969.1   627.9 1973.28   647.8 1982.79
   657.8    1986   687.7 1990.66   727.6 1999.09   767.4 2006.22   857.1  2019.3
   867.1 2021.51   926.9 2039.31   986.7 2055.72   996.7 2059.19  1036.5 2074.89
#Mann= 3 , 0 , 0
       0      .1       0   358.8    .045       0   538.2      .1       0
Bank Sta=358.8,538.2
XS Rating Curve= 0 ,0
Exp/Cntr=0.3,0.1

Type RM Length L Ch R = 1 ,88396.8 ,597.6,596.1,593.4
XS GIS Cut Line= 3
     2008428.481       384118.79     2008700.893       384781.24
     2008841.011       385176.81
#Sta/Elev= 30
       0 2123.73    49.7 2108.66    79.6 2098.64   119.4 2084.77   248.7 2038.22
   268.6 2031.49   348.2 2007.28     378 1999.39   417.8 1989.88   487.5 1975.17
   497.4 1973.29   507.4  1971.9   596.9 1966.06   706.8    1960   726.3 1959.59
   776.2 1959.53   796.2 1959.75   806.2 1960.42   816.2 1961.72   866.2 1970.07
   876.1 1971.58   886.1  1972.6   916.1 1973.95     996 1978.75    1006 1979.46
    1016 1980.64    1076 1992.79    1096 1997.11  1115.9 2002.03  1135.9  2007.6
#Mann= 3 , 0 , 0
       0      .1       0   706.8    .045       0   796.2      .1       0
Bank Sta=706.8,796.2
XS Rating Curve= 0 ,0
Exp/Cntr=0.3,0.1

Type RM Length L Ch R = 1 ,87800.7 ,799.8,800,801.1
XS GIS Cut Line= 3
     2007904.349      384421.792     2008131.516      384918.194
     2008378.123      385405.894
#Sta/Elev= 30
       0    2103    49.6 2083.46    89.3 2068.19   109.2 2060.82   158.8 2043.18
   218.4 2020.41     268 2002.83   297.8 1993.35   317.6 1987.82   327.6 1985.34
   337.5 1983.49   357.3 1980.52   387.1 1975.51   436.7 1968.65   486.4 1958.24
   496.3 1957.03   506.2 1956.67   545.9 1956.58   585.7 1956.59   615.5 1957.31
   754.6 1964.52   774.4 1966.87   804.3 1968.89   853.9 1972.91   863.9 1974.14
   873.8 1976.78   883.8 1980.68   943.4 2008.04    1003 2036.49  1092.4 2077.06
#Mann= 3 , 0 , 0
       0      .1       0   486.4    .045       0   585.7      .1       0
Bank Sta=486.4,585.7
XS Rating Curve= 0 ,0
Exp/Cntr=0.3,0.1

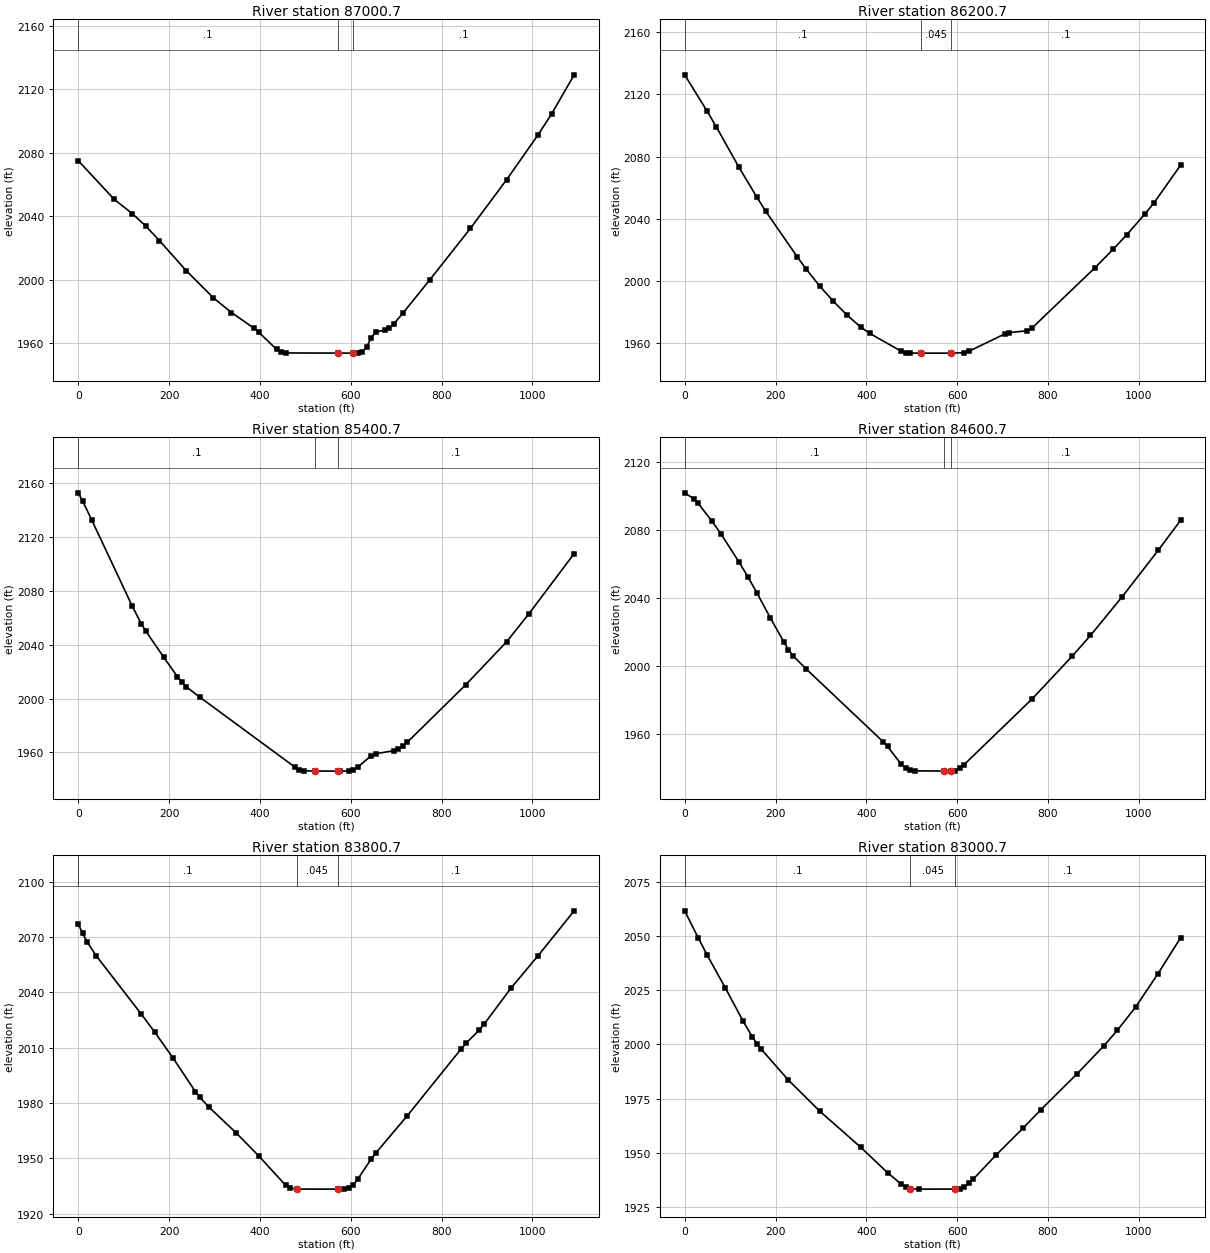
Type RM Length L Ch R = 1 ,87000.7 ,803.5,800,796.5
XS GIS Cut Line= 3
     2007215.761      384816.829     2007438.496      385315.332
     2007661.231      385813.835
#Sta/Elev= 30
       0 2074.96    79.4 2050.56   119.1  2041.6   148.9 2033.75   178.7 2024.66
   238.2 2005.59   297.8 1988.58   337.5 1979.32   387.2 1969.44   397.1 1967.04
   436.8 1956.12   446.7 1954.44   456.6 1953.89     571  1953.8   605.6  1953.8
   615.5 1953.78   625.4 1954.43   635.4  1957.8   645.3 1963.55   655.2 1967.06
     675 1968.25     685 1969.63   694.9 1972.22   714.8 1978.89   774.3 1999.99
   863.7 2032.37   943.1 2062.88  1012.6 2091.23  1042.4 2104.39    1092 2128.99
#Mann= 3 , 0 , 0
       0      .1       0     571    .045       0   605.6      .1       0
Bank Sta=571,605.6
XS Rating Curve= 0 ,0
Exp/Cntr=0.3,0.1

Type RM Length L Ch R = 1 ,86200.7 ,801.6,800,798.4
XS GIS Cut Line= 3
     2006418.392      385184.992     2006715.275      385643.224
     2007012.158      386101.456
#Sta/Elev= 30
       0 2132.63    49.6  2109.2    69.5 2099.27   119.1 2073.44   158.8 2054.05
   178.7 2044.87   248.2 2015.51     268 2007.62   297.8 1996.71   327.6 1987.05
   357.4 1978.25   387.2 1970.65     407 1966.53   476.5 1955.08   486.4 1954.17
   496.4 1953.82     521  1953.8   585.7 1953.79   615.5 1954.07   625.4 1954.92
   704.8 1966.13   714.8 1966.96   754.5  1968.2   764.4 1969.81   903.4 2008.67
   943.1 2020.41   972.9  2029.7  1012.6 2042.96  1032.4 2049.96    1092 2074.57
#Mann= 3 , 0 , 0
       0      .1       0     521    .045       0   585.7      .1       0
Bank Sta=521,585.7
XS Rating Curve= 0 ,0
Exp/Cntr=0.3,0.1

Type RM Length L Ch R = 1 ,85400.7 ,797.1,800,802.9
XS GIS Cut Line= 3
     2005801.383      385747.933     2006130.767       386183.39
     2006460.151      386618.846
#Sta/Elev= 30
       0 2152.83     9.9 2146.66    29.8 2132.62   119.1 2068.56     139  2055.4
   148.9 2050.07   188.6 2030.49   218.4 2016.26   228.3 2012.01   238.2  2008.6
     268 2000.94   476.5  1949.2   486.4 1947.09   496.4 1946.29     521 1946.13
     571 1946.05   575.8 1946.04   595.6 1946.15   605.6 1946.88   615.5 1948.99
   645.3 1957.57   655.2    1959   694.9 1961.21   704.8 1962.61   714.8  1964.7
   724.7 1967.53   853.8 2010.37   943.1 2042.09   992.7  2063.1    1092 2107.67
#Mann= 3 , 0 , 0
       0      .1       0     521    .045       0     571      .1       0
Bank Sta=521,571
XS Rating Curve= 0 ,0
Exp/Cntr=0.3,0.1

Type RM Length L Ch R = 1 ,84600.7 ,801.2,800,798.8
XS GIS Cut Line= 3
     2005188.161      386139.391     2005458.172      386613.954
     2005728.183      387088.517
#Sta/Elev= 30
       0 2101.84    19.8  2098.4    29.8  2095.6    59.6 2085.34    79.4 2077.89
   119.1 2061.36     139 2052.55   158.8  2043.1   188.6 2028.28   218.4 2014.09
   228.3 2009.67   238.2 2006.05     268 1998.11   436.8 1955.47   446.7 1952.63
   476.5 1942.32   486.4 1939.77   496.4 1938.54   506.3 1938.32     571 1938.16
   585.7 1938.14   595.6 1938.44   605.6 1939.74   615.5 1942.02   764.4 1980.44
   853.8  2005.9   893.4 2017.92     963  2040.6  1042.4 2067.94    1092 2085.69
#Mann= 3 , 0 , 0
       0      .1       0     571    .045       0   585.7      .1       0
Bank Sta=571,585.7
XS Rating Curve= 0 ,0
Exp/Cntr=0.3,0.1

Type RM Length L Ch R = 1 ,83800.7 ,799.7,800,800.3
XS GIS Cut Line= 3
     2004515.465      386618.363     2004809.788      387078.243
     2005104.111      387538.124
#Sta/Elev= 30
       0 2077.13     9.9 2071.97    19.8 2067.29    39.7 2059.85     139 2028.22
   168.8 2018.38   208.5 2004.58   258.1 1986.21     268  1983.1   287.9 1977.85
   347.4 1963.97   397.1 1951.49   456.6 1935.51   466.6 1933.95   482.1 1933.41
     571 1933.39   585.7 1933.44   595.6 1933.91   605.6 1935.57   615.5 1938.82
   645.3 1949.74   655.2 1952.94   724.7  1973.2   843.8 2009.58   853.8 2012.38
   883.5 2019.74   893.4  2022.7     953 2042.37  1012.6  2059.9    1092 2084.23
#Mann= 3 , 0 , 0
       0      .1       0   482.1    .045       0     571      .1       0
Bank Sta=482.1,571
XS Rating Curve= 0 ,0
Exp/Cntr=0.3,0.1

Type RM Length L Ch R = 1 ,83000.7 ,810.8,800,789.2
XS GIS Cut Line= 3
      2003820.28      386999.129     2004109.118      387462.473
     2004397.957      387925.818
#Sta/Elev= 30
       0 2061.54    29.8 2049.09    49.6 2041.16    89.4 2026.06     129 2010.62
   148.9 2003.53   158.8 2000.44   168.8 1997.78   228.3 1983.61   297.8 1969.22
   387.2 1952.75   446.7 1940.96   476.5 1935.77   486.4 1934.44   496.4 1933.59
   516.2 1933.39   595.6 1933.41   605.6 1933.63   615.5 1934.45   625.4 1936.03
   635.4 1937.98     685 1948.97   744.6 1961.39   784.2 1969.93   863.7 1986.43
   923.2 1999.41     953 2006.61   992.7 2017.17  1042.4 2032.66    1092 2049.15
#Mann= 3 , 0 , 0
       0      .1       0   496.4    .045       0   595.6      .1       0
Bank Sta=496.4,595.6
XS Rating Curve= 0 ,0
Exp/Cntr=0.3,0.1