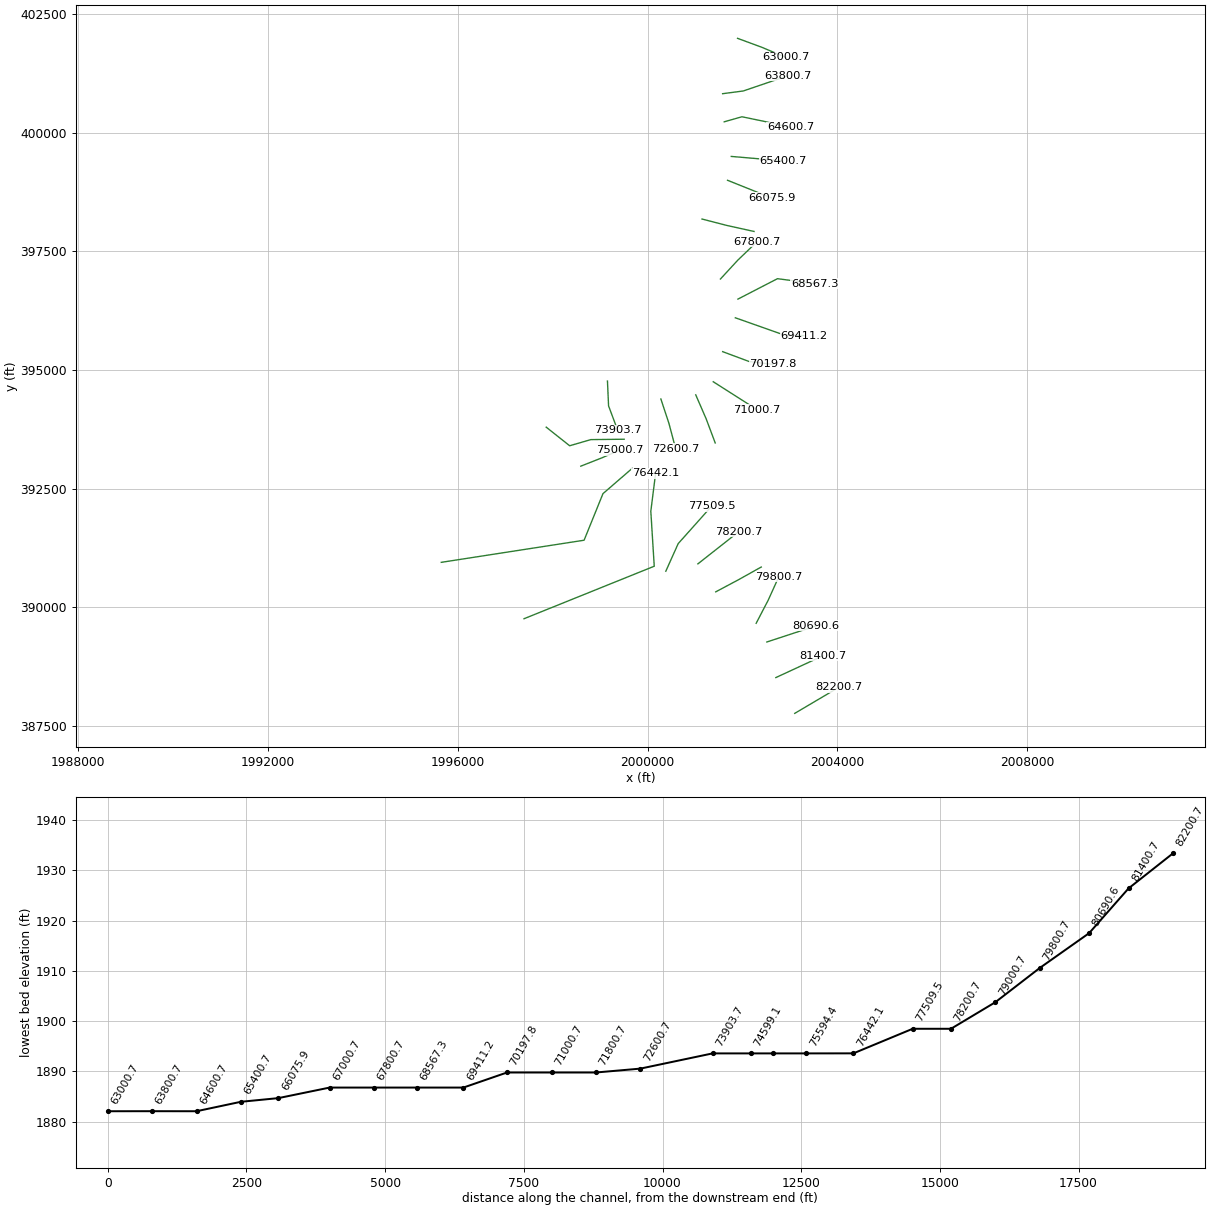
HEC-RAS study MeadowRvr.prj: MeadowRvr

--- MeadowRvr.g01 (geometry) --- (continued)

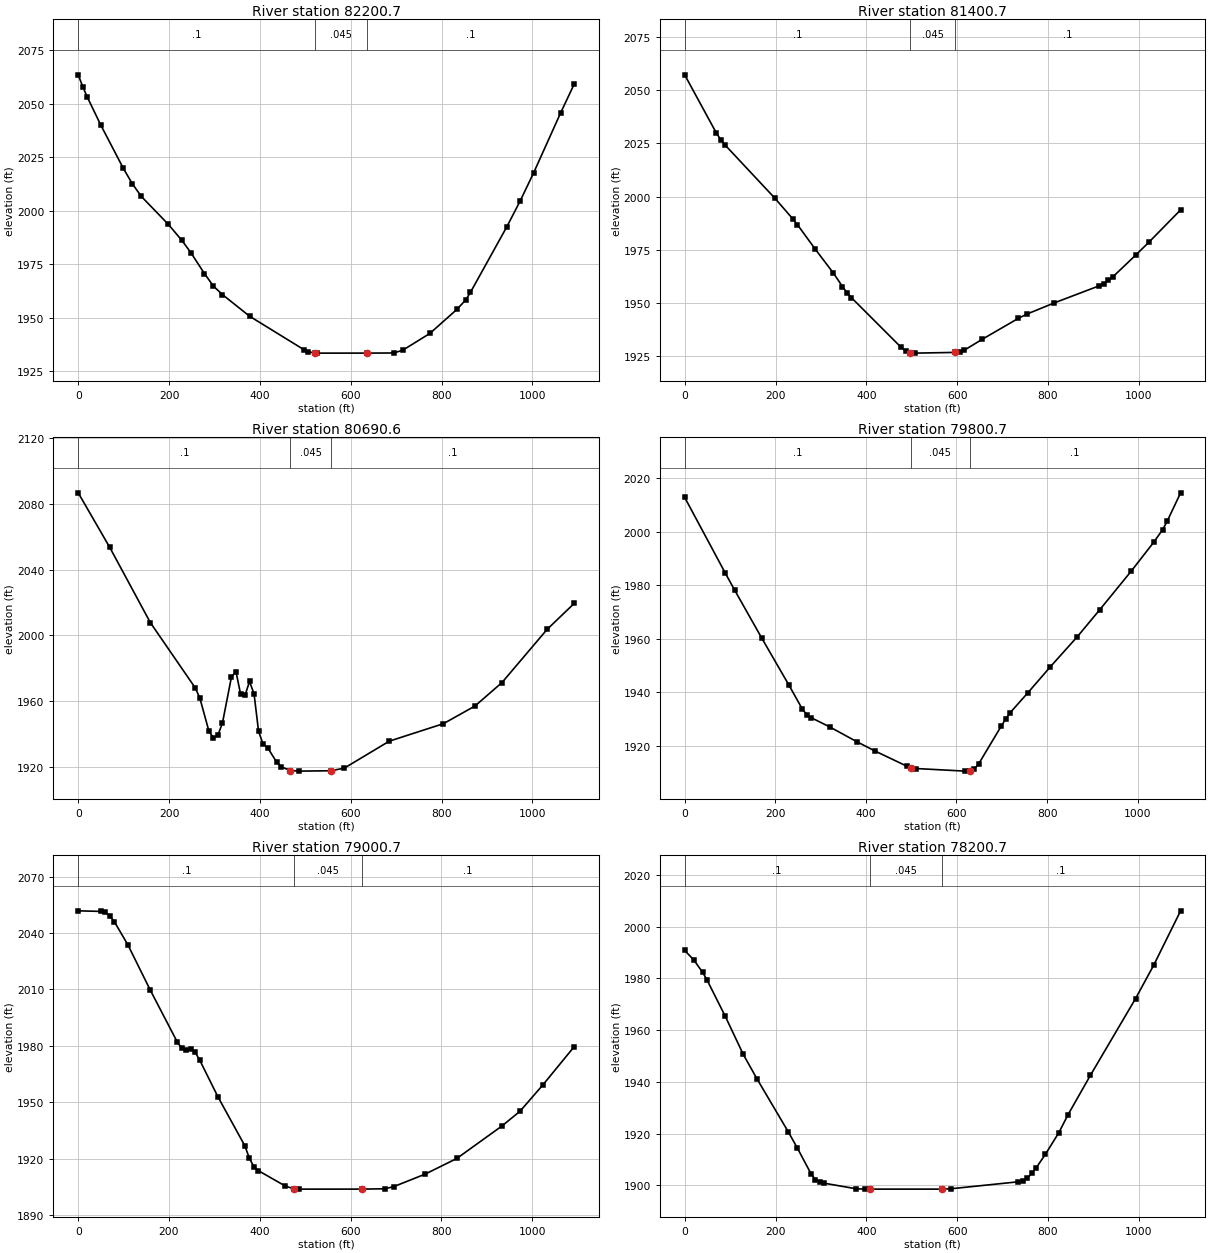
Type RM Length L Ch R = 1 ,82200.7 ,802.2,800,797.8
XS GIS Cut Line= 3
     2003100.372      387768.721     2003570.591      388046.228
      2004040.81      388323.734
#Sta/Elev= 30
       0 2063.54     9.9 2058.05    19.8  2053.2    49.6 2040.08    99.3 2019.82
   119.1 2012.61     139 2006.67   198.6 1993.57   228.3 1986.11   248.2 1980.33
     278 1970.58   297.8 1964.71   317.7 1960.75   377.2 1950.67   496.4 1935.08
   506.3 1934.05     521 1933.45   526.2 1933.39   635.4  1933.4   694.9 1933.46
   714.8 1934.78   774.3  1942.6   833.9 1953.86   853.8 1958.41   863.7 1961.83
   943.1 1992.23   972.9 2004.45  1002.6 2017.63  1062.2 2045.73    1092 2059.16
#Mann= 3 , 0 , 0
       0      .1       0     521    .045       0   635.4      .1       0
Bank Sta=521,635.4
XS Rating Curve= 0 ,0
Exp/Cntr=0.3,0.1

Type RM Length L Ch R = 1 ,81400.7 ,712.7,710,707.4
XS GIS Cut Line= 3
     2002702.325      388522.368     2003197.802      388751.755
     2003693.279      388981.142
#Sta/Elev= 30
       0 2057.27    69.5    2030    79.4 2026.79    89.4 2024.17   198.6 1999.25
   238.2  1989.5   248.2 1986.84   287.9 1975.18   327.6 1964.02   347.4 1957.74
   357.4 1954.84   367.3 1952.47   476.5 1929.16   486.4  1927.4   496.4  1926.5
   506.3 1926.42   595.6 1926.76   605.6    1927   615.5 1927.78   655.2 1932.93
   734.6 1942.76   754.5 1944.86     814 1950.05   913.3 1958.12   923.2 1959.15
   933.2 1960.57   943.1 1962.34   992.7 1972.43  1022.5 1978.64    1092 1993.77
#Mann= 3 , 0 , 0
       0      .1       0   496.4    .045       0   595.6      .1       0
Bank Sta=496.4,595.6
XS Rating Curve= 0 ,0
Exp/Cntr=0.3,0.1

Type RM Length L Ch R = 1 ,80690.6 ,872.5,890,908.7
XS GIS Cut Line= 3
     2002512.379      389271.781     2003031.205      389441.887
      2003550.03      389611.994
#Sta/Elev= 30
       0  2086.7    69.5  2053.5   158.8 2007.82   258.1 1967.96     268 1961.76
   287.9  1941.7   297.8 1937.68   307.8 1939.53   317.7 1946.89   337.5 1974.92
   347.4 1977.93   357.4 1964.55   367.3 1963.56   377.2 1972.01   387.2 1964.46
   397.1 1941.72     407 1934.02     417 1931.81   436.8 1923.03   446.7 1920.18
     467 1917.89   486.4 1917.52   555.9 1917.75   585.7 1919.31     685 1935.74
   804.1 1946.36   873.6 1957.09   933.2 1971.39  1032.4 2003.67    1092 2019.46
#Mann= 3 , 0 , 0
       0      .1       0     467    .045       0   555.9      .1       0
Bank Sta=467,555.9
XS Rating Curve= 0 ,0
Exp/Cntr=0.3,0.1

Type RM Length L Ch R = 1 ,79800.7 ,813.6,800,785.6
XS GIS Cut Line= 3
     2002287.445      389665.651     2002541.548      390153.267
     2002766.465      390649.669
#Sta/Elev= 30
       0 2012.89      90 1984.49     110 1978.33     170 1960.35   229.9 1942.81
   259.9 1933.72   269.9 1931.64   279.9  1930.5   319.9 1927.14   379.9  1921.6
   419.9 1918.13   489.9 1912.48   499.9 1911.87   509.9 1911.57   619.2 1910.59
   629.1 1910.67     639 1911.29   648.9 1913.28   698.5 1927.32   708.4    1930
   718.3 1932.39   757.9 1939.93   807.5 1949.64   866.9 1960.86   916.5 1970.95
   985.8 1985.34  1035.4 1996.13  1055.2 2000.86  1065.1 2003.99  1094.8  2014.6
#Mann= 3 , 0 , 0
       0      .1       0   499.9    .045       0   629.1      .1       0
Bank Sta=499.9,629.1
XS Rating Curve= 0 ,0
Exp/Cntr=0.3,0.1

Type RM Length L Ch R = 1 ,79000.7 ,796,800,803.6
XS GIS Cut Line= 3
      2001435.57      390327.999     2001917.403      390584.459
     2002395.054      390850.902
#Sta/Elev= 30
       0  2051.8    49.6 2051.49    59.6 2050.93    69.5 2049.09    79.4 2046.09
   109.2 2033.82   158.8 2009.63   218.3 1982.02   228.3 1978.63   238.2 1977.91
   248.1 1978.18     258 1976.46     268 1972.27   307.6    1953   367.2 1926.81
   377.1 1920.27     387  1915.7     397  1913.6   456.5 1905.39   476.4 1903.87
   486.3 1903.78   625.4 1903.79   675.1 1903.96     695 1905.08   764.6 1911.77
   834.2 1920.09   933.7 1937.36   973.4 1945.17  1023.2 1959.01  1092.8 1979.52
#Mann= 3 , 0 , 0
       0      .1       0   476.4    .045       0   625.4      .1       0
Bank Sta=476.4,625.4
XS Rating Curve= 0 ,0
Exp/Cntr=0.3,0.1

Type RM Length L Ch R = 1 ,78200.7 ,687.2,691.1,695.1
XS GIS Cut Line= 3
      2001059.43      390917.127     2001488.592      391254.671
     2001917.755      391592.214
#Sta/Elev= 30
       0 1990.82    19.8 1987.24    39.7 1982.33    49.6 1979.28    89.4 1965.35
     129 1950.62   158.8 1941.28   228.3  1920.6   248.2 1914.35     278  1904.5
   287.9 1902.13   297.8 1901.21   307.8 1900.76   377.2 1898.64   397.1 1898.49
     407 1898.49   565.8 1898.49   585.7 1898.62   734.6 1901.33   744.6 1901.74
   754.5 1902.69   764.4 1904.66   774.3  1906.8   794.2 1911.96     824 1920.37
   843.8  1927.2   893.4 1942.54   992.7 1972.19  1032.4 1985.02    1092 2006.17
#Mann= 3 , 0 , 0
       0      .1       0     407    .045       0   565.8      .1       0
Bank Sta=407,565.8
XS Rating Curve= 0 ,0
Exp/Cntr=0.3,0.1

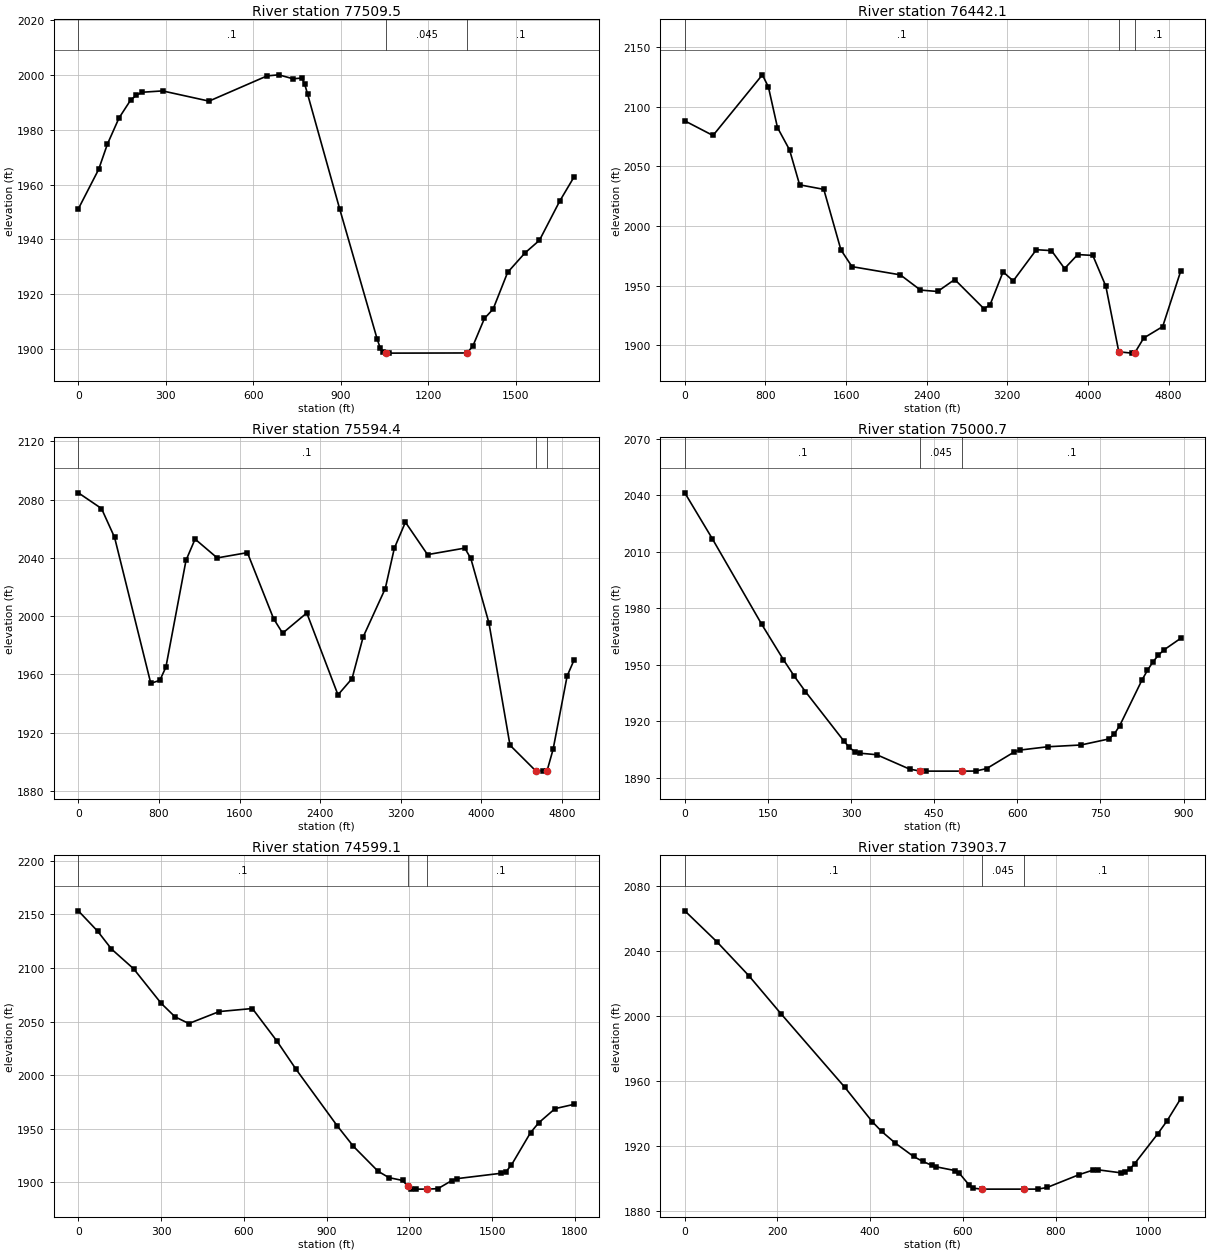
Type RM Length L Ch R = 1 ,77509.5 ,1053.8,1067.4,1081
XS GIS Cut Line= 4
     2000383.264      390762.331      2000644.54      391343.879
     2000989.252      391729.629     2001353.069      392136.757
#Sta/Elev= 30
       0 1951.16    69.7 1965.57    99.6 1974.76   139.5 1984.33   179.3 1990.86
   199.2 1992.65   219.2 1993.74   288.9 1994.23   448.3  1990.5   647.5 1999.71
   687.3  2000.1     737 1998.65   766.9 1998.93   776.8  1996.6   786.8 1992.93
   896.2 1951.27  1025.5 1903.49  1035.5  1900.4  1045.4  1898.8  1055.4  1898.5
  1065.3 1898.49  1333.6 1898.55  1353.4 1901.08  1393.1 1911.15  1422.9 1914.57
  1472.6 1927.96  1532.1 1935.06  1581.8 1939.68  1651.2 1953.96  1700.9 1962.88
#Mann= 3 , 0 , 0
       0      .1       0  1055.4    .045       0  1333.6      .1       0
Bank Sta=1055.4,1333.6
XS Rating Curve= 0 ,0
Exp/Cntr=0.3,0.1

Type RM Length L Ch R = 1 ,76442.1 ,864.3,847.8,831.3
XS GIS Cut Line= 4
     1997395.619      389762.062     2000139.778      390867.623
     2000067.627      392025.656     2000168.157      392820.763
#Sta/Elev= 30
       0 2088.23   279.9 2075.98   769.6 2126.82   829.6 2116.67   919.5 2082.64
  1039.5 2063.94  1139.4 2034.64  1379.3 2030.84  1549.2 1980.13  1659.2 1966.08
  2138.9 1959.19  2338.8 1946.44  2508.7 1945.25  2678.6  1955.3  2968.5 1930.84
  3028.5 1933.95  3158.5 1961.74  3258.6  1954.1  3488.6 1980.27  3638.7  1979.5
  3768.7 1964.48  3898.7 1976.19  4048.8 1975.48  4178.1 1949.66  4306.8  1894.7
  4435.4  1893.6  4465.1  1893.8  4554.1 1906.25  4742.1 1915.84  4920.2 1962.11
#Mann= 3 , 0 , 0
       0      .1       0  4306.8    .045       0  4465.1      .1       0
Bank Sta=4306.8,4465.1
XS Rating Curve= 0 ,0
Exp/Cntr=0.3,0.1

Type RM Length L Ch R = 1 ,75594.4 ,601.3,593.7,586.8
XS GIS Cut Line= 4
      1995651.76      390949.559     1998661.413      391415.136
     1999059.209      392396.002     1999676.226      392929.303
#Sta/Elev= 30
       0  2084.7   229.7 2073.93   359.5 2054.12   718.9 1953.86   808.8 1955.96
   868.7 1964.96  1068.4 2038.34  1158.3 2052.94  1377.9    2040  1677.5 2043.63
  1937.1 1998.31    2027 1988.32  2266.6  2002.2  2576.2 1945.96  2715.9 1957.16
  2825.8 1985.72  3045.4 2018.96  3135.3 2046.66  3245.2 2064.54  3464.8 2042.27
  3834.3 2046.74  3894.2 2039.64    4074 1995.34  4282.9  1911.4    4541  1893.6
    4614 1893.59  4650.9 1893.88  4710.6 1908.56  4849.8 1958.89  4919.5 1970.05
#Mann= 3 , 0 , 0
       0      .1       0    4541    .045       0  4650.9      .1       0
Bank Sta=4541,4650.9
XS Rating Curve= 0 ,0
Exp/Cntr=0.3,0.1

Type RM Length L Ch R = 1 ,75000.7 ,409.8,401.6,392.6
XS GIS Cut Line= 3
     1998591.934      392974.887     1999033.788      393148.862
     1999419.018      393315.779
#Sta/Elev= 30
       0 2041.34    49.5 2017.04   138.5 1971.68   178.1 1952.69   197.9 1943.85
   217.6 1935.84   286.9 1909.64   296.8  1906.2   306.7 1903.91   316.6 1903.09
   346.3 1902.31   405.6 1894.67   424.5 1893.62   435.3 1893.59     500 1893.59
   524.8 1893.62   544.8 1894.96   594.8 1903.83   604.8 1904.77   654.8 1906.52
   714.8 1907.47   764.8 1910.64   774.8 1913.21   784.8 1917.74   824.7 1941.79
   834.7 1947.05   844.7 1951.54   854.7  1955.2   864.7 1957.96   894.7 1964.07
#Mann= 3 , 0 , 0
       0      .1       0   424.5    .045       0     500      .1       0
Bank Sta=424.5,500
XS Rating Curve= 0 ,0
Exp/Cntr=0.3,0.1

Type RM Length L Ch R = 1 ,74599.1 ,723,695.4,667.9
XS GIS Cut Line= 4
     1997862.838      393796.278      1998357.46      393404.593
     1998804.379      393534.199     1999505.638       393542.11
#Sta/Elev= 30
       0 2153.41    70.1 2134.37   120.2 2117.73   200.3 2099.34   300.4 2067.04
   350.5 2054.47   400.6 2048.18   510.8 2059.37   630.9  2062.2     720 2031.81
   789.3 2005.47   937.8 1952.96   997.2 1933.57  1086.4 1910.34  1125.9 1904.33
  1175.3 1901.71  1194.1 1896.49  1204.9  1894.1  1224.7 1893.59  1263.7 1893.59
  1303.7 1894.02  1353.1 1901.46  1372.8 1903.38  1530.9 1908.34  1550.6 1909.95
  1570.4  1916.2  1639.5 1946.35  1669.2 1955.53  1728.4 1968.75  1797.6 1972.78
#Mann= 3 , 0 , 0
       0      .1       0  1194.1    .045       0  1263.7      .1       0
Bank Sta=1194.1,1263.7
XS Rating Curve= 0 ,0
Exp/Cntr=0.3,0.1

Type RM Length L Ch R = 1 ,73903.7 ,1304.1,1303,1300.5
XS GIS Cut Line= 3
     1999153.817      394766.938     1999177.188      394244.262
     1999368.722      393732.115
#Sta/Elev= 30
       0 2064.53    69.1 2045.56   138.2 2024.68   207.3  2001.4   345.5 1956.08
   404.7 1934.97   424.5 1929.12   454.1  1921.9   493.6 1913.66   513.3 1910.65
   533.1 1908.21   543.1 1907.26   582.8    1905   592.8  1903.2   612.7 1896.42
   622.6 1894.16   641.6 1893.59     732 1893.59   761.8  1893.6   781.7 1894.59
   851.3 1902.52   881.1  1905.3     891 1905.48   940.8 1903.61   950.7 1904.06
   960.6 1906.01   970.6 1909.18  1020.3 1927.45  1040.2 1935.32    1070 1949.08
#Mann= 3 , 0 , 0
       0      .1       0   641.6    .045       0     732      .1       0
Bank Sta=641.6,732
XS Rating Curve= 0 ,0
Exp/Cntr=0.3,0.1

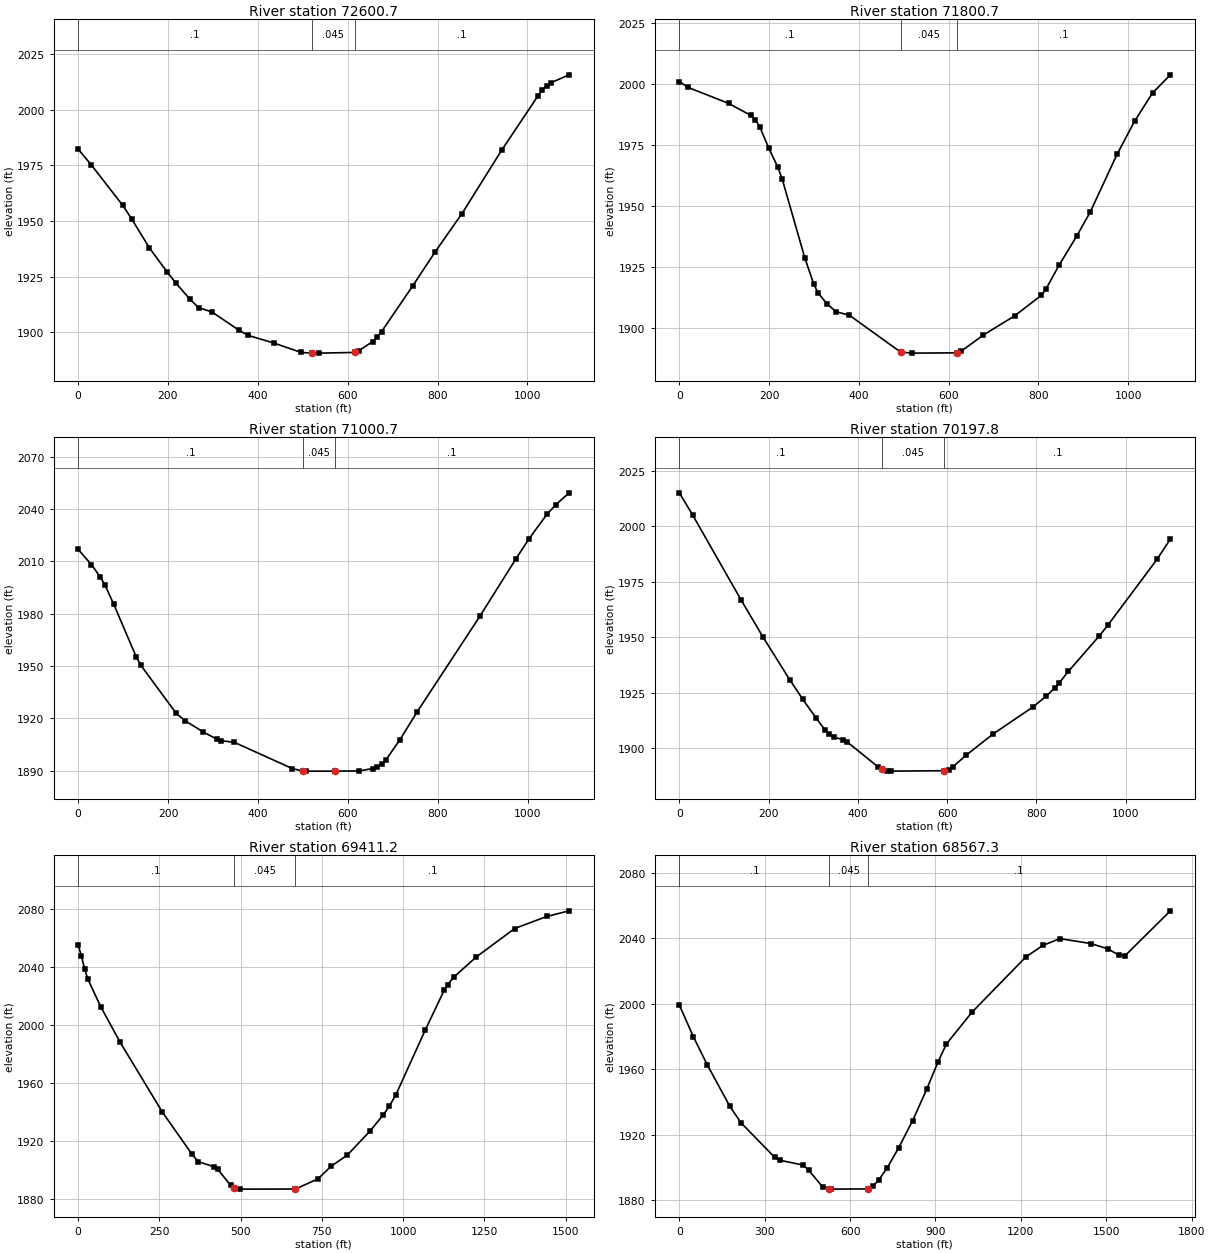
Type RM Length L Ch R = 1 ,72600.7 ,797.9,799.9,802.2
XS GIS Cut Line= 3
     2000279.475      394390.179      2000450.53      393871.724
     2000590.826      393343.189
#Sta/Elev= 30
       0 1982.35    29.8 1975.15    99.3 1957.07   119.1 1951.02   158.8 1937.87
   198.5 1926.95   218.4 1921.91   248.2 1914.99     268 1911.04   297.8 1909.09
   357.4 1900.96   377.2 1898.62   436.8 1895.03   496.3 1890.87   520.9 1890.57
     536 1890.56   615.5 1890.87   625.5 1891.74   655.3 1895.73   665.2 1897.61
   675.2  1900.2   744.8 1920.85   794.5  1936.1   854.2 1953.32   943.6 1982.18
  1023.2 2006.25  1033.1 2008.97  1043.1 2010.98    1053  2012.3  1092.8 2015.79
#Mann= 3 , 0 , 0
       0      .1       0   520.9    .045       0   615.5      .1       0
Bank Sta=520.9,615.5
XS Rating Curve= 0 ,0
Exp/Cntr=0.3,0.1

Type RM Length L Ch R = 1 ,71800.7 ,786.5,800,814.6
XS GIS Cut Line= 3
     2001014.182      394477.325     2001232.767      393973.892
     2001424.917      393463.362
#Sta/Elev= 30
       0 2000.89      20 1998.48   109.8 1991.96   159.7 1987.03   169.6  1985.3
   179.6 1982.22   199.6 1973.57   219.5 1965.91   229.5 1960.85   279.4 1928.91
   299.4 1918.11   309.4 1914.37   329.3 1909.91   349.3 1906.75   379.2 1905.27
   492.9 1890.24   518.9 1889.79   618.3 1889.91   628.2 1890.57   677.8 1897.21
   747.2 1905.03   806.7 1913.44   816.6 1915.84   846.4 1925.81     886 1937.81
   915.8 1947.55   975.3 1971.06    1015 1984.83  1054.7 1996.26  1094.3 2003.65
#Mann= 3 , 0 , 0
       0      .1       0   492.9    .045       0   618.3      .1       0
Bank Sta=492.9,618.3
XS Rating Curve= 0 ,0
Exp/Cntr=0.3,0.1

Type RM Length L Ch R = 1 ,71000.7 ,798.5,802.8,807.1
XS GIS Cut Line= 3
     2001383.523      394752.477     2001844.162      394459.342
     2002304.801      394166.208
#Sta/Elev= 30
       0 2016.84    29.8 2008.08    49.6 2000.88    59.6  1996.5    79.4 1985.34
     129 1955.43     139 1950.61   218.4 1922.84   238.2 1918.63     278 1912.28
   307.8 1908.18   317.7 1907.24   347.4 1906.29   476.5 1891.24   499.1 1889.84
   506.3 1889.79     571 1889.79   625.4 1889.91   655.2 1891.27   665.1 1892.09
     675 1893.67     685 1896.41   714.8 1907.46   754.5 1923.94   893.4 1978.49
   972.9 2011.15  1002.6 2022.83  1042.4 2036.89  1062.2 2042.41    1092 2049.25
#Mann= 3 , 0 , 0
       0      .1       0   499.1    .045       0     571      .1       0
Bank Sta=499.1,571
XS Rating Curve= 0 ,0
Exp/Cntr=0.3,0.1

Type RM Length L Ch R = 1 ,70197.8 ,785.8,786.6,787.4
XS GIS Cut Line= 3
      2001581.73      395386.283     2002137.776      395179.512
     2002640.732      395118.039
#Sta/Elev= 30
       0 2015.02    29.7  2005.1   138.4 1966.81   187.9 1949.98   247.2 1930.96
   276.8 1922.03   306.5 1913.65   326.3 1908.34   336.2 1906.28   346.1 1905.07
   365.8 1904.01   375.7 1902.98   444.9 1891.74   454.3 1890.55   464.7 1889.91
   474.6 1889.79   593.2 1889.97   603.2 1890.51   613.1 1891.79   642.9 1897.02
   702.5 1906.44     792 1918.64   821.8 1923.51   841.6 1927.35   851.6 1929.62
   871.4 1934.64     941 1950.68   960.8 1955.69  1070.1 1985.09    1100 1994.25
#Mann= 3 , 0 , 0
       0      .1       0   454.3    .045       0   593.2      .1       0
Bank Sta=454.3,593.2
XS Rating Curve= 0 ,0
Exp/Cntr=0.3,0.1

Type RM Length L Ch R = 1 ,69411.2 ,825.5,843.9,862.4
XS GIS Cut Line= 3
     2001848.879      396099.655     2002855.775      395744.155
     2003298.538      395723.039
#Sta/Elev= 30
       0 2055.14      10 2047.58      20 2038.61    29.9 2031.55    69.9 2012.39
   129.7 1987.86   259.5 1939.82   349.3 1911.21   369.2 1905.75   419.1 1902.15
   429.1 1900.63     469 1889.56     479  1887.5     499 1886.79   668.6 1886.86
   738.5 1893.89   778.4 1902.54   828.3  1910.2   898.2 1926.76   938.1 1937.73
     958 1944.03     978 1951.89  1067.8 1996.18  1126.9 2024.02  1136.8 2027.71
  1156.5 2032.97  1225.4  2046.8  1343.6  2066.4  1442.1 2074.69  1511.1 2078.58
#Mann= 3 , 0 , 0
       0      .1       0     479    .045       0   668.6      .1       0
Bank Sta=479,668.6
XS Rating Curve= 0 ,0
Exp/Cntr=0.3,0.1

Type RM Length L Ch R = 1 ,68567.3 ,758.8,766.6,773.1
XS GIS Cut Line= 4
     2001903.063      396492.786     2002411.607      396755.441
     2002737.172      396923.232     2003516.937      396819.886
#Sta/Elev= 30
       0 1999.27    49.3 1979.89    98.7 1962.53   177.6 1937.33   217.1 1927.23
   335.5 1906.14   355.3 1904.37   434.2  1901.5     454 1898.45   503.3 1888.18
   526.9 1886.81   532.9 1886.79   661.5 1886.92   681.3 1888.73     701  1892.5
   730.8 1899.92   770.4 1911.96   819.8 1928.63   869.3 1947.84   908.9 1964.52
   938.6  1975.5  1028.2 1994.83  1217.4 2028.57  1277.2  2035.6  1336.9 2039.78
  1446.4 2036.74  1506.2  2033.5    1546 2029.47  1565.9 2029.34  1725.2 2056.75
#Mann= 3 , 0 , 0
       0      .1       0   526.9    .045       0   661.5      .1       0
Bank Sta=526.9,661.5
XS Rating Curve= 0 ,0
Exp/Cntr=0.3,0.1

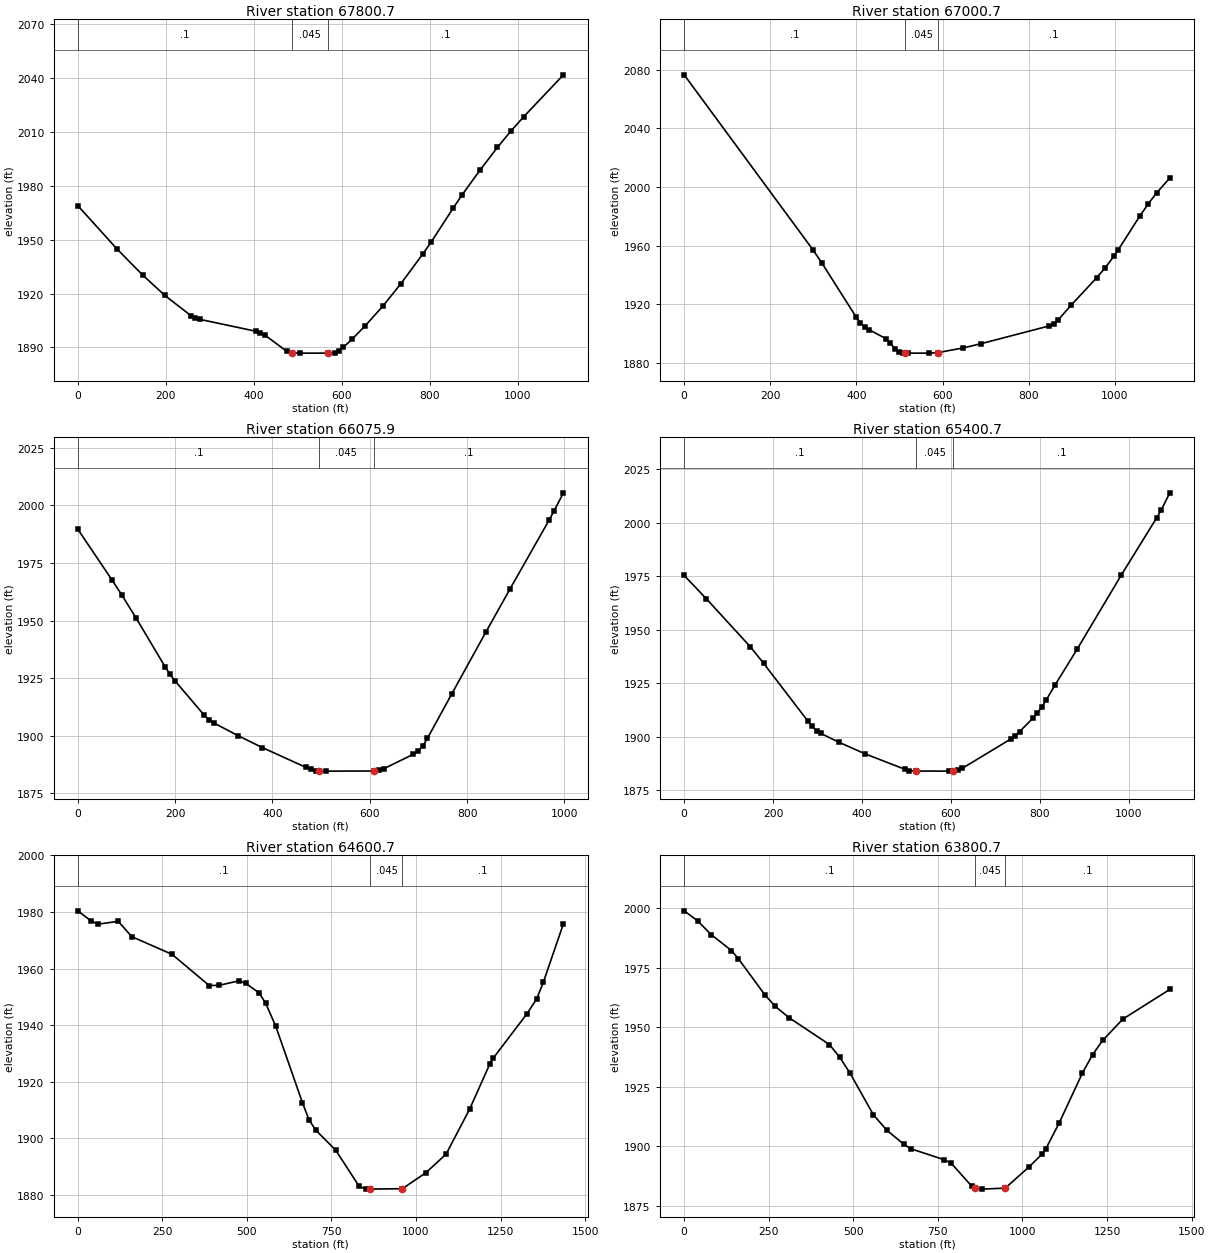
Type RM Length L Ch R = 1 ,67800.7 ,824.4,800,777.8
XS GIS Cut Line= 3
     2001534.614      396916.095     2001902.931      397315.651
     2002307.867      397702.467
#Sta/Elev= 30
       0 1968.94    88.9 1944.83   148.2 1930.08   197.6 1918.94   256.9 1907.68
   266.8 1906.43   276.6 1905.64   405.1 1898.94     415 1898.16   424.8 1896.87
   474.2  1887.9   487.6 1886.95   503.9 1886.79   568.4 1886.79   583.4 1887.02
   593.4 1888.15   603.4 1890.05   623.4 1894.62   653.4 1902.15   693.4 1913.08
   733.4 1925.28   783.4 1941.87   803.4  1948.9   853.4 1967.79   873.4 1975.06
   913.4  1988.6   953.4 2001.41   983.4 2010.32  1013.4 2018.56  1103.4 2041.82
#Mann= 3 , 0 , 0
       0      .1       0   487.6    .045       0   568.4      .1       0
Bank Sta=487.6,568.4
XS Rating Curve= 0 ,0
Exp/Cntr=0.3,0.1

Type RM Length L Ch R = 1 ,67000.7 ,927.7,924.8,921.1
XS GIS Cut Line= 3
     2001146.513      398179.559     2001667.777      398044.749
      2002242.93      397917.844
#Sta/Elev= 30
       0 2076.56   299.1 1957.18   319.1 1948.54   398.8 1911.59   408.8 1907.56
   418.8 1904.74   428.7 1902.85   468.6  1896.6   478.6 1893.61   488.6 1889.86
   498.5 1887.38   508.5 1886.82   513.4 1886.81   518.5 1886.79   568.4 1886.79
   588.3 1887.12   648.2 1890.35   688.2 1893.16   847.9 1905.38   857.9  1906.6
   867.8 1909.26   897.8 1919.32   957.7 1938.24   977.7 1945.07   997.6  1952.9
  1007.6 1957.19  1057.5 1980.14  1077.5 1988.67  1097.4 1996.25  1127.4 2006.23
#Mann= 3 , 0 , 0
       0      .1       0   513.4    .045       0   588.3      .1       0
Bank Sta=513.4,588.3
XS Rating Curve= 0 ,0
Exp/Cntr=0.3,0.1

Type RM Length L Ch R = 1 ,66075.9 ,668.5,675.2,681.9
XS GIS Cut Line= 2
     2001683.528      398995.728     2002609.996      398624.762
#Sta/Elev= 30
       0 1989.64    69.9 1967.75    89.8 1961.33   119.8  1951.1   179.6 1929.88
   189.6 1926.64   199.6 1923.89   259.5 1909.02   269.4 1907.02   279.4  1905.6
   329.3 1900.08   379.2 1894.91     469  1886.3     479 1885.44     489  1884.9
   495.1 1884.79     509 1884.69   608.8 1884.74   618.8 1885.03   628.7 1885.73
   688.6 1891.92   698.6 1893.23   708.6  1895.5   718.5 1898.93   768.4 1918.19
   838.3 1944.94   888.2 1963.75     968 1993.46     978 1997.36     998 2005.46
#Mann= 3 , 0 , 0
       0      .1       0   495.1    .045       0   608.8      .1       0
Bank Sta=495.1,608.8
XS Rating Curve= 0 ,0
Exp/Cntr=0.3,0.1

Type RM Length L Ch R = 1 ,65400.7 ,802.7,800,796.8
XS GIS Cut Line= 3
      2001762.46      399497.885     2002306.476      399451.388
     2002850.493       399404.89
#Sta/Elev= 30
       0 1975.32    49.6 1964.49   148.9 1941.98   178.7 1934.29     278 1907.35
   287.9 1904.81   297.8  1902.8   307.8 1901.54   347.4 1897.49     407 1892.02
   496.4 1884.81   506.3 1884.25     521    1884   595.6 1883.96   605.6    1884
   615.5 1884.37   625.4 1885.28   734.6 1898.98   744.6 1900.53   754.5 1902.45
   784.2  1908.7   794.2 1911.09   804.1  1913.9     814 1917.16   833.9 1924.13
   883.5 1940.84   982.8 1975.45  1062.2 2002.13  1072.2 2005.66    1092 2013.89
#Mann= 3 , 0 , 0
       0      .1       0     521    .045       0   605.6      .1       0
Bank Sta=521,605.6
XS Rating Curve= 0 ,0
Exp/Cntr=0.3,0.1

Type RM Length L Ch R = 1 ,64600.7 ,788,800,812.6
XS GIS Cut Line= 4
     2001614.442      400226.905      2001988.04      400333.162
     2002479.625      400231.295     2003011.058      400107.382
#Sta/Elev= 30
       0  1980.4    39.8 1976.77    59.8 1975.69   119.5  1976.7   159.4 1971.29
   278.9 1965.01   388.4 1954.01     418 1954.09     477 1955.68   496.7 1954.76
   536.1 1951.41   555.8 1947.67   585.3 1939.64     664 1912.68   683.7 1906.56
   703.4 1902.96   762.5 1895.85   831.4 1883.17   851.1 1882.08   865.4 1882.09
   959.9 1882.23  1029.4 1887.89  1088.9 1894.43  1158.3 1910.25  1217.9 1926.19
  1227.8 1928.26    1327 1943.85  1356.8 1949.25  1376.6 1955.16  1436.1 1975.89
#Mann= 3 , 0 , 0
       0      .1       0   865.4    .045       0   959.9      .1       0
Bank Sta=865.4,959.9
XS Rating Curve= 0 ,0
Exp/Cntr=0.3,0.1

Type RM Length L Ch R = 1 ,63800.7 ,815.4,800,783.6
XS GIS Cut Line= 4
     2001580.469      400819.008     2002016.055      400876.257
     2002442.077      401021.285     2002958.948      401197.241
#Sta/Elev= 30
       0 1998.98    39.9 1994.76    79.9 1988.98   139.8 1982.31   159.8 1978.95
   239.6  1963.5   269.6 1958.82   309.5 1954.15   429.4  1942.8   459.3 1937.55
   489.3 1931.04   559.3 1913.31   599.3 1906.78   649.4 1900.92   669.4 1899.08
   769.4 1894.39   789.4 1892.95   849.4 1883.41   859.4 1882.42   879.4 1882.09
   948.9 1882.51  1018.4  1891.3  1058.1 1896.84    1068 1898.76  1107.8  1909.7
  1177.2 1930.89    1207 1938.53  1236.8 1944.53  1296.4 1953.48  1435.4 1965.97
#Mann= 3 , 0 , 0
       0      .1       0   859.4    .045       0   948.9      .1       0
Bank Sta=859.4,948.9
XS Rating Curve= 0 ,0
Exp/Cntr=0.3,0.1

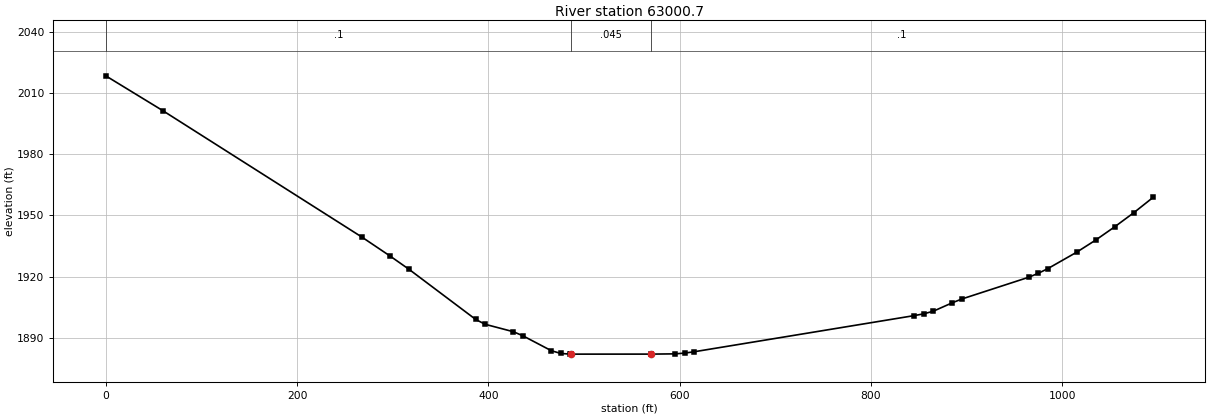
Type RM Length L Ch R = 1 ,63000.7 ,805.8,800,795.2
XS GIS Cut Line= 3
     2001895.569      401984.799     2002407.258      401796.282
     2002914.071       401582.89
#Sta/Elev= 30
       0  2018.4    59.5 2001.38   267.7 1939.45   297.4  1930.1   317.3 1923.56
   386.7 1899.12   396.6 1896.71   426.3 1893.05   436.2 1891.06     466 1883.74
   475.9 1882.41   485.8 1882.08     487 1882.08   570.3 1882.09   595.3 1882.21
   605.3 1882.58   615.3 1883.24   845.3 1900.94   855.3 1901.81   865.3 1903.08
   885.2 1907.22   895.2 1909.08   965.2 1919.74   975.2 1921.68   985.2 1923.97
  1015.2 1931.97  1035.2 1937.94  1055.2 1944.48  1075.2  1951.4  1095.2 1958.84
#Mann= 3 , 0 , 0
       0      .1       0     487    .045       0   570.3      .1       0
Bank Sta=487,570.3
XS Rating Curve= 0 ,0
Exp/Cntr=0.3,0.1