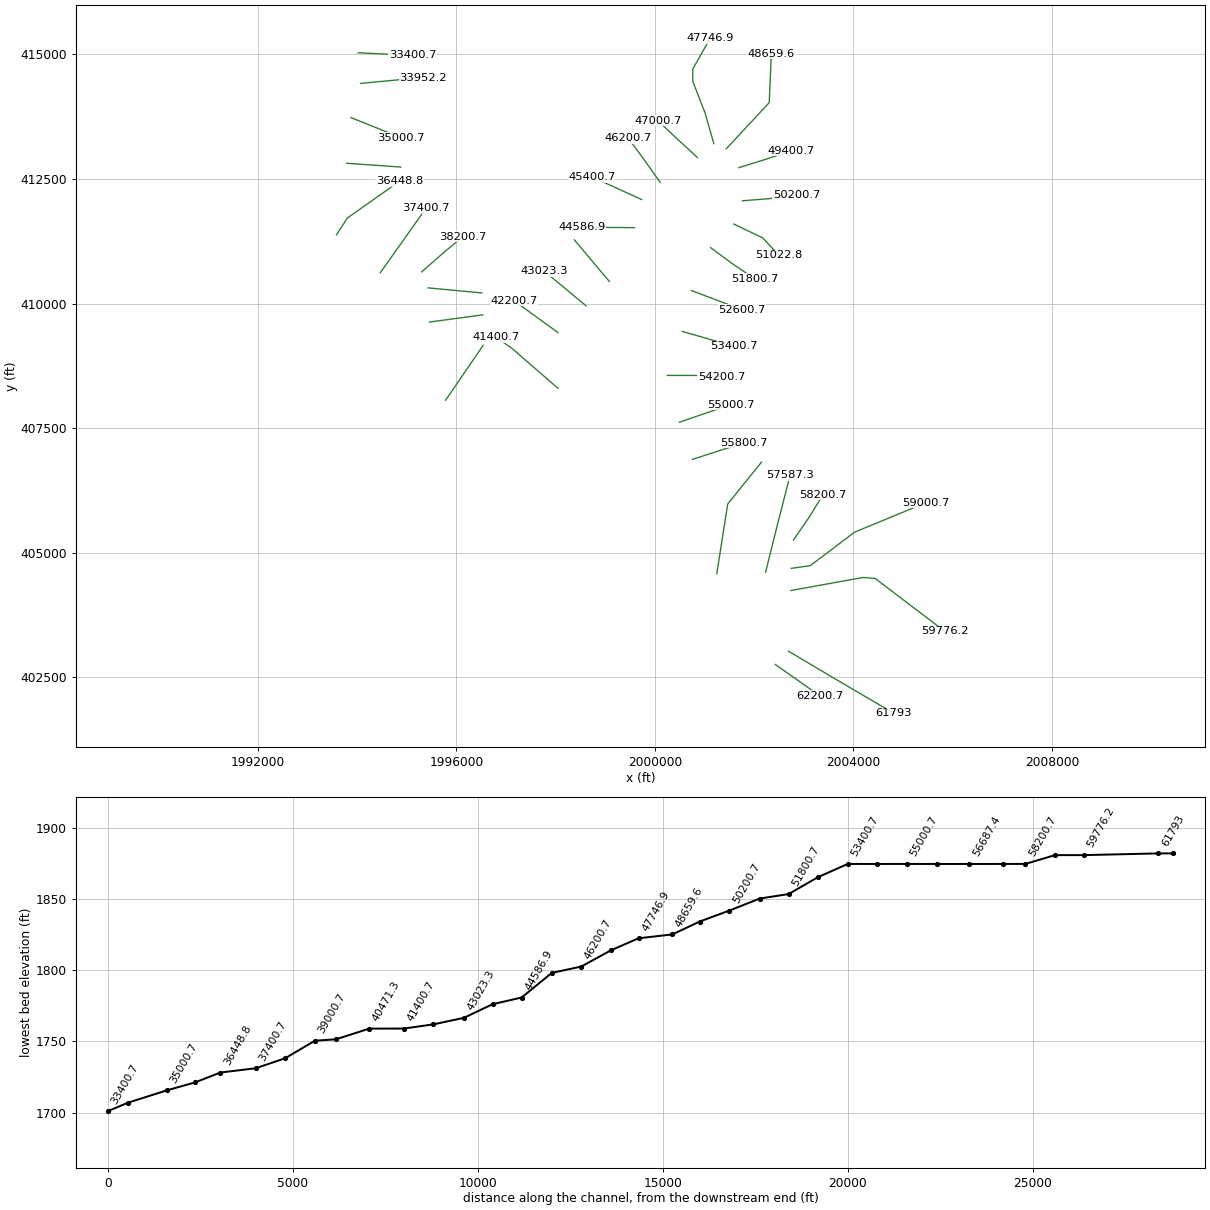
HEC-RAS study MeadowRvr.prj: MeadowRvr

--- MeadowRvr.g01 (geometry) --- (continued)

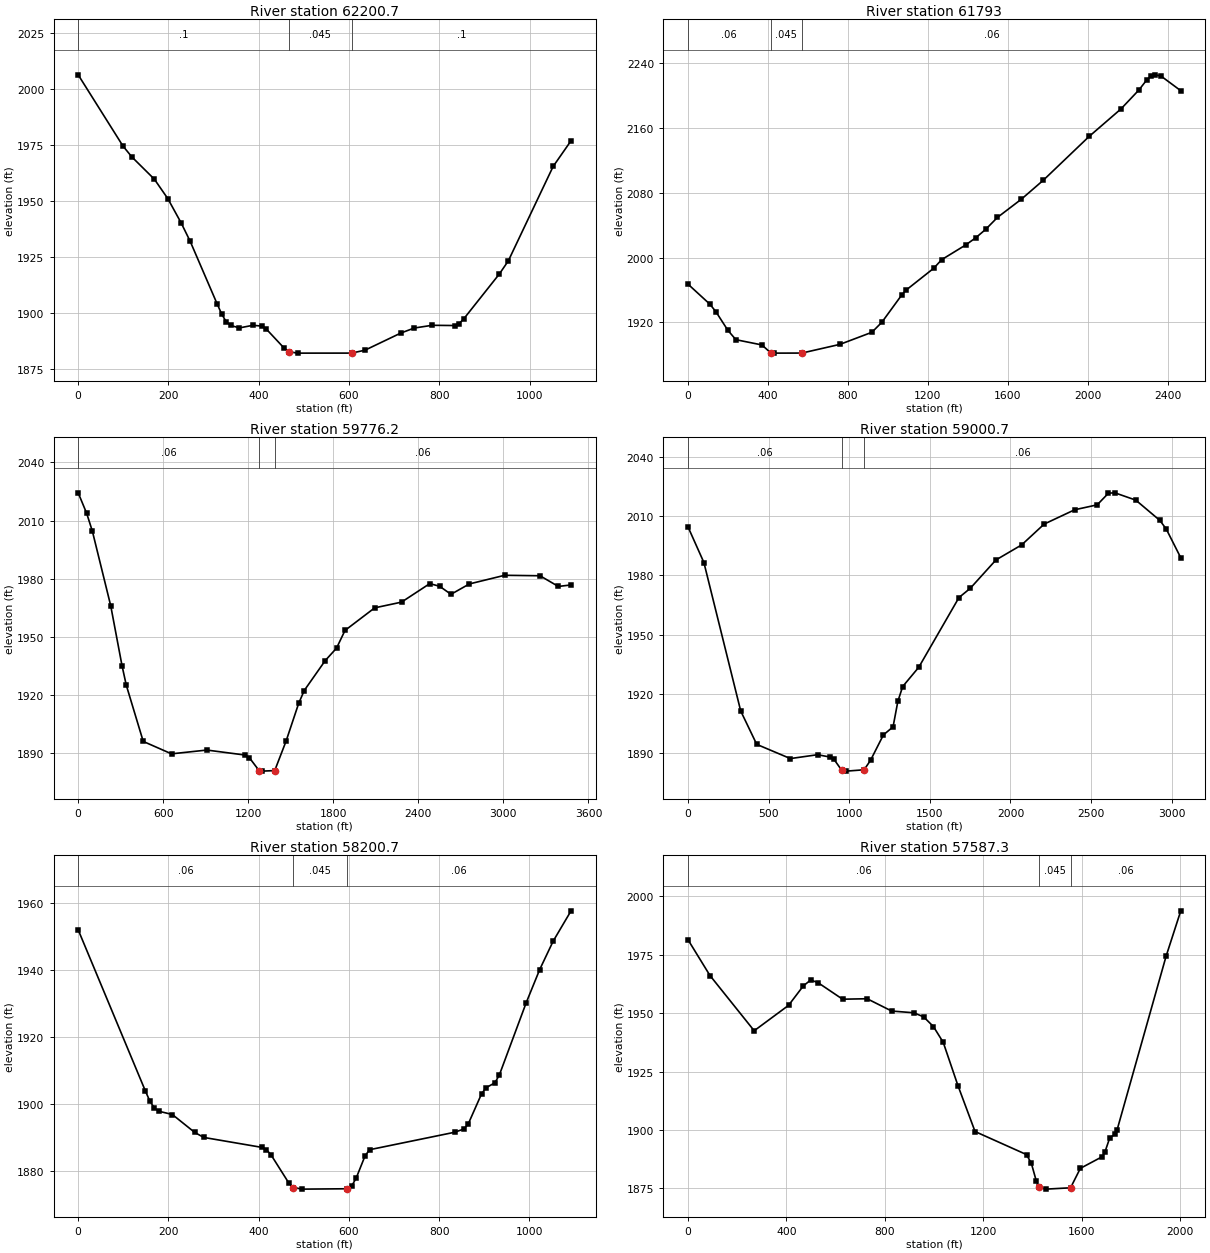
Type RM Length L Ch R = 1 ,62200.7 ,405.9,407.7,409.4
XS GIS Cut Line= 3
     2002423.956      402757.083     2002871.257      402443.973
     2003318.558      402130.862
#Sta/Elev= 30
       0 2006.17    99.3  1974.4   119.1 1969.53   168.8 1959.63   198.6 1950.97
   228.3 1940.08   248.2 1931.91   307.8 1904.06   317.7 1899.63   327.6 1896.17
   337.5 1894.43   357.4 1893.34   387.2  1894.5     407 1894.14     417 1892.78
   456.6 1884.26   467.7 1882.67   486.4 1882.09   605.6  1882.1   635.4  1883.4
   714.8 1891.04   744.6 1893.28   784.2  1894.5   833.9 1894.39   843.8 1895.24
   853.8 1897.25   933.2  1917.4     953 1923.23  1052.3 1965.32    1092 1976.79
#Mann= 3 , 0 , 0
       0      .1       0   467.7    .045       0   605.6      .1       0
Bank Sta=467.7,605.6
XS Rating Curve= 0 ,0
Exp/Cntr=0.3,0.1

Type RM Length L Ch R = 1 ,61793   ,2000.7,2016.8,2032.8
XS GIS Cut Line= 3
     2002691.027      403022.835     2003577.624      402498.937
     2004816.024      401775.588
#Sta/Elev= 30
       0 1967.37     110 1942.48     140 1933.23     200 1910.18     240 1898.68
   369.9  1892.2   413.6 1882.57   429.9 1882.09   569.9 1882.17   759.9 1892.89
   919.8 1907.82   969.8 1920.24  1069.6 1954.06  1089.6 1959.64    1229 1986.89
  1268.8  1997.5  1388.4 2015.58  1438.2 2024.35    1488 2034.74  1547.7 2049.68
  1667.2 2072.15  1776.8 2095.55  2005.8 2149.61  2165.2 2183.62  2254.8    2207
  2294.7 2219.63  2314.6 2224.14  2334.5 2225.69  2364.4 2224.32    2464 2206.08
#Mann= 3 , 0 , 0
       0     .06       0   413.6    .045       0   569.9     .06       0
Bank Sta=413.6,569.9
XS Rating Curve= 0 ,0
Exp/Cntr=0.3,0.1

Type RM Length L Ch R = 1 ,59776.2 ,765.1,775.6,786.1
XS GIS Cut Line= 4
     2002738.529      404241.106     2004191.753      404502.431
     2004437.554      404483.348     2005836.225      403424.306
#Sta/Elev= 30
       0 2024.32    59.9 2013.74    99.8 2004.63   229.5 1966.13   309.3 1935.24
   339.2 1925.22   458.9  1896.2   658.4  1889.8   907.9 1891.75  1177.2 1889.18
  1207.2 1887.86  1275.9  1881.2    1297 1880.89  1386.7 1881.17  1466.6 1896.33
  1555.4 1915.76  1594.9 1922.44    1743 1937.86  1822.8 1944.28  1882.6 1953.41
  2091.9 1965.04  2281.3 1967.99  2480.6 1977.53  2550.4 1976.15  2630.2 1972.02
  2759.8 1977.36    3009 1981.82  3258.2 1981.58  3387.7 1976.07  3477.4 1976.85
#Mann= 3 , 0 , 0
       0     .06       0  1275.9    .045       0  1386.7     .06       0
Bank Sta=1275.9,1386.7
XS Rating Curve= 0 ,0
Exp/Cntr=0.3,0.1

Type RM Length L Ch R = 1 ,59000.7 ,792.7,800,808.2
XS GIS Cut Line= 5
     2002746.911      404685.384     2003130.006      404740.884
      2003654.14      405134.533     2004020.341      405411.217
     2005458.204      406002.137
#Sta/Elev= 30
       0 2004.59    99.2 1986.44   327.5 1911.31   426.8 1894.43   635.4 1887.24
   804.2  1889.2   883.7 1887.97   903.6 1887.11   953.2 1881.39     983 1880.89
  1092.5 1881.57  1132.4 1886.35  1212.2 1899.21  1272.1  1903.3    1302 1916.26
  1331.9  1923.7  1431.7 1933.46  1680.9 1968.73  1750.7 1973.37  1910.1 1987.74
  2069.6 1995.36  2209.1 2005.89  2398.4 2013.13  2537.9 2015.62  2607.7 2021.53
  2647.6  2021.7  2777.1 2018.01  2926.6 2007.73  2966.4 2003.33  3056.1 1988.84
#Mann= 3 , 0 , 0
       0     .06       0   953.2    .045       0  1092.5     .06       0
Bank Sta=953.2,1092.5
XS Rating Curve= 0 ,0
Exp/Cntr=0.3,0.1

Type RM Length L Ch R = 1 ,58200.7 ,605,613.3,620.7
XS GIS Cut Line= 3
     2002790.871      405254.758     2003100.975      405704.884
     2003391.182      406167.247
#Sta/Elev= 30
       0 1952.07   149.1 1903.93     159 1900.91     169 1898.88   178.9 1897.93
   208.7 1896.96   258.4  1891.6   278.3 1890.12   407.5 1887.14   417.4 1886.46
   427.4 1884.93   467.1 1876.47     477 1875.16   496.9 1874.69   596.2  1874.8
   606.2 1875.62   616.1 1877.95   635.9 1884.62   645.9 1886.45   834.4 1891.66
   854.3  1892.6   864.2 1894.02     894 1903.09   903.9 1904.93   923.8 1906.43
   933.7 1908.81   993.2 1930.36    1023 1940.22  1052.8 1948.68  1092.5 1957.74
#Mann= 3 , 0 , 0
       0     .06       0     477    .045       0   596.2     .06       0
Bank Sta=477,596.2
XS Rating Curve= 0 ,0
Exp/Cntr=0.3,0.1

Type RM Length L Ch R = 1 ,57587.3 ,910.3,899.9,889.5
XS GIS Cut Line= 3
     2002229.084      404608.469     2002473.572      405585.708
     2002721.764      406549.117
#Sta/Elev= 30
       0 1981.54    89.8 1966.13   269.3  1942.5   408.9 1953.38   468.8 1961.69
   498.7 1964.23   528.6 1963.09   628.4 1956.01   728.1 1956.21   827.8 1950.94
   917.6  1950.2   957.5 1948.46   997.4  1944.3  1037.2 1937.54  1096.9 1919.05
  1166.5 1899.35  1375.5 1889.48  1395.4 1885.68  1415.2 1878.19  1427.2 1875.49
    1455 1874.69  1554.5 1875.26  1594.3 1883.59  1683.9 1888.62  1693.8  1890.5
  1713.7 1896.64  1733.6 1898.09  1743.6 1900.09  1942.5 1974.39  2002.2 1993.85
#Mann= 3 , 0 , 0
       0     .06       0  1427.2    .045       0  1554.5     .06       0
Bank Sta=1427.2,1554.5
XS Rating Curve= 0 ,0
Exp/Cntr=0.3,0.1

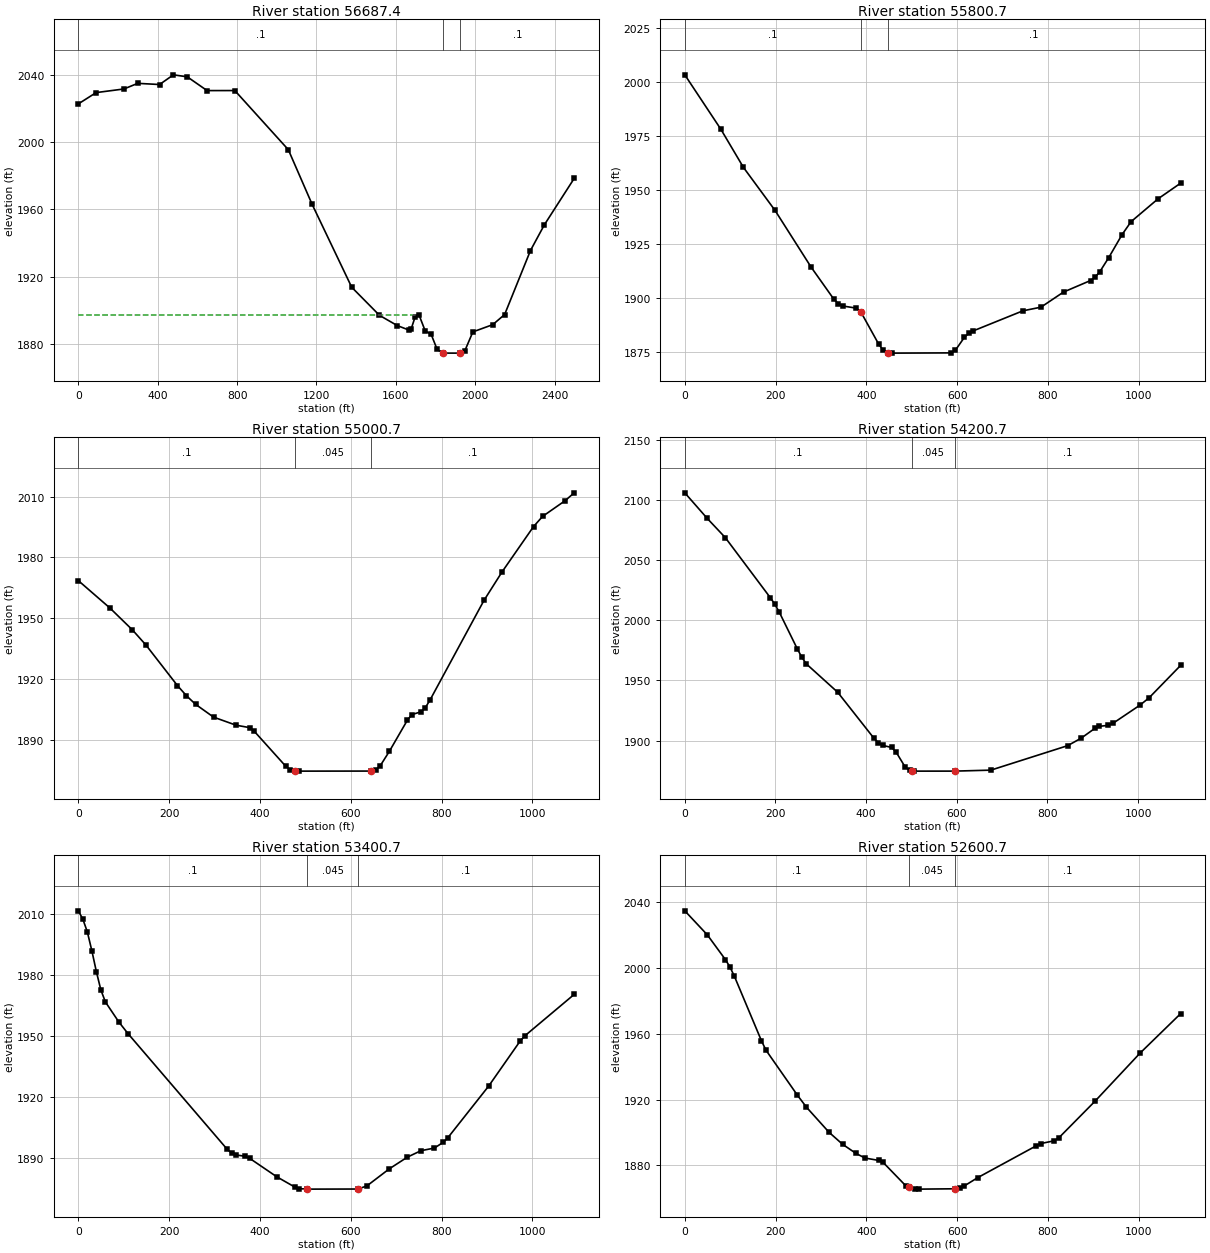
Type RM Length L Ch R = 1 ,56687.4 ,899.5,886.8,873.7
XS GIS Cut Line= 3
     2001245.318      404576.588     2001465.744      405977.032
     2002146.158       406817.36
#Sta/Elev= 30
       0 2022.65    89.8 2029.36   229.6 2031.51   299.5 2034.85   409.3 2034.15
   479.2 2039.91   549.1 2038.72   648.9 2030.55   788.7 2030.57  1058.3 1995.46
  1178.1 1963.06  1377.8 1913.79  1517.8  1897.1  1607.9    1891    1668 1888.29
    1678 1889.22    1698 1896.39    1718 1897.05  1748.1 1887.88  1778.1 1885.85
  1808.1 1876.94  1837.4 1874.69    1926 1874.67  1948.3 1876.16  1988.4 1887.28
  2088.5 1891.57  2148.5 1897.58  2278.7 1935.59  2348.8 1950.87  2498.9 1978.38
#Mann= 3 , 0 , 0
       0      .1       0  1837.4    .045       0    1926      .1       0
#XS Ineff= 2 , 0
         1708.01 1897.43
Permanent Ineff=
       F       F
Bank Sta=1837.4,1926
XS Rating Curve= 0 ,0
Exp/Cntr=0.3,0.1

Type RM Length L Ch R = 1 ,55800.7 ,799.6,800,800.6
XS GIS Cut Line= 3
      2000759.34      406873.187     2001279.081      407041.851
     2001800.302      407203.701
#Sta/Elev= 30
       0 2003.21    79.5 1978.05   129.2 1960.44   198.7 1940.61   278.2  1914.4
   327.8 1899.73   337.8 1897.58   347.7 1896.45   377.5 1895.46   387.5  1893.8
   427.2 1878.79   437.1 1875.99   447.1 1874.82     457 1874.67   586.1 1874.78
     596 1875.99   615.9 1881.97   625.8 1883.88   635.7 1884.97   744.9 1894.22
   784.6  1895.9   834.2 1902.87   893.7  1908.2   903.7 1909.75   913.6 1912.08
   933.4 1918.63   963.2 1929.41     983 1935.38  1042.6 1945.96  1092.2 1953.17
#Mann= 3 , 0 , 0
       0      .1       0   387.5    .045       0   447.1      .1       0
Bank Sta=387.5,447.1
XS Rating Curve= 0 ,0
Exp/Cntr=0.3,0.1

Type RM Length L Ch R = 1 ,55000.7 ,807.4,800,791.3
XS GIS Cut Line= 3
     2000492.987      407618.334     2001009.593      407795.067
     2001526.198      407971.801
#Sta/Elev= 30
       0 1968.56    69.5 1955.08   119.1 1944.28   148.9 1936.83   218.4 1916.81
   238.2 1911.82   258.1 1907.63   297.8  1901.3   347.4 1897.32   377.2 1896.13
   387.2  1894.4   456.6 1877.14   466.6 1875.44   476.5 1874.77   486.4 1874.69
   645.3 1874.72   655.2 1875.36   665.1 1877.41     685 1884.44   724.7  1899.8
   734.6 1902.55   754.5 1903.91   764.4 1906.02   774.3 1909.63   893.4 1958.82
   933.2 1972.86  1002.6 1995.21  1022.5 2000.21  1072.2 2007.96    1092 2011.82
#Mann= 3 , 0 , 0
       0      .1       0   476.5    .045       0   645.3      .1       0
Bank Sta=476.5,645.3
XS Rating Curve= 0 ,0
Exp/Cntr=0.3,0.1

Type RM Length L Ch R = 1 ,54200.7 ,806.3,800,794.9
XS GIS Cut Line= 3
     2000246.275      408557.177      2000791.87      408557.177
     2001339.369      408527.651
#Sta/Elev= 30
       0 2105.74    49.6 2084.46    89.3 2068.58   188.5 2018.77   198.4 2013.38
   208.3 2006.77     248 1976.34   257.9 1969.43   267.8 1963.82   337.3 1940.17
   416.6  1902.3   426.6  1898.3   436.5 1896.04   456.3 1894.34   466.2 1890.48
   486.1 1878.12     496 1875.24   500.3    1875   505.9 1874.68   595.4 1874.69
   675.2  1875.5   844.7 1895.82   874.6 1902.08   904.5 1910.13   914.4 1911.87
   934.4  1912.7   944.4 1914.32  1004.2 1929.47  1024.1 1935.47  1093.9 1962.46
#Mann= 3 , 0 , 0
       0      .1       0   500.3    .045       0   595.4      .1       0
Bank Sta=500.3,595.4
XS Rating Curve= 0 ,0
Exp/Cntr=0.3,0.1

Type RM Length L Ch R = 1 ,53400.7 ,801.8,800,798.2
XS GIS Cut Line= 3
     2000549.385      409441.227     2001073.994      409289.897
     2001598.604      409138.567
#Sta/Elev= 30
       0 2011.47     9.9 2007.41    19.8 2001.12    29.8 1991.84    39.7 1981.59
    49.6  1972.6    59.6 1966.69    89.4 1956.78   109.2 1951.17   327.6 1894.33
   337.5 1892.39   347.4 1891.48   367.3 1890.85   377.2 1889.85   436.8 1880.79
   476.5 1875.74   486.4 1874.93   504.5 1874.69   615.5 1874.74   635.4 1876.25
     685 1884.68   724.7 1890.42   754.5 1893.57   784.2 1894.88   804.1 1897.77
     814    1900   903.4 1925.24   972.9 1947.42   982.8 1949.92    1092 1970.38
#Mann= 3 , 0 , 0
       0      .1       0   504.5    .045       0   615.5      .1       0
Bank Sta=504.5,615.5
XS Rating Curve= 0 ,0
Exp/Cntr=0.3,0.1

Type RM Length L Ch R = 1 ,52600.7 ,806.2,800,794.8
XS GIS Cut Line= 3
     2000731.782      410261.762      2001242.62      410068.992
     2001753.459      409876.223
#Sta/Elev= 30
       0 2034.83    49.6 2020.21    89.4 2005.17    99.3 2000.72   109.2 1995.02
   168.8 1955.76   178.7 1950.07   248.2 1922.56     268 1915.31   317.7 1900.06
   347.4 1892.79   377.2 1887.17   397.1 1884.38   426.9 1882.96   436.8 1881.74
   486.4 1867.59   493.1 1866.51   506.3  1865.5   516.2 1865.48   595.6 1865.69
   605.6 1866.13   615.5 1867.41   645.3  1872.5   774.3 1891.89   784.2 1893.22
     814 1894.92     824 1896.76   903.4 1918.97  1002.6 1948.23    1092 1972.26
#Mann= 3 , 0 , 0
       0      .1       0   493.1    .045       0   595.6      .1       0
Bank Sta=493.1,595.6
XS Rating Curve= 0 ,0
Exp/Cntr=0.3,0.1

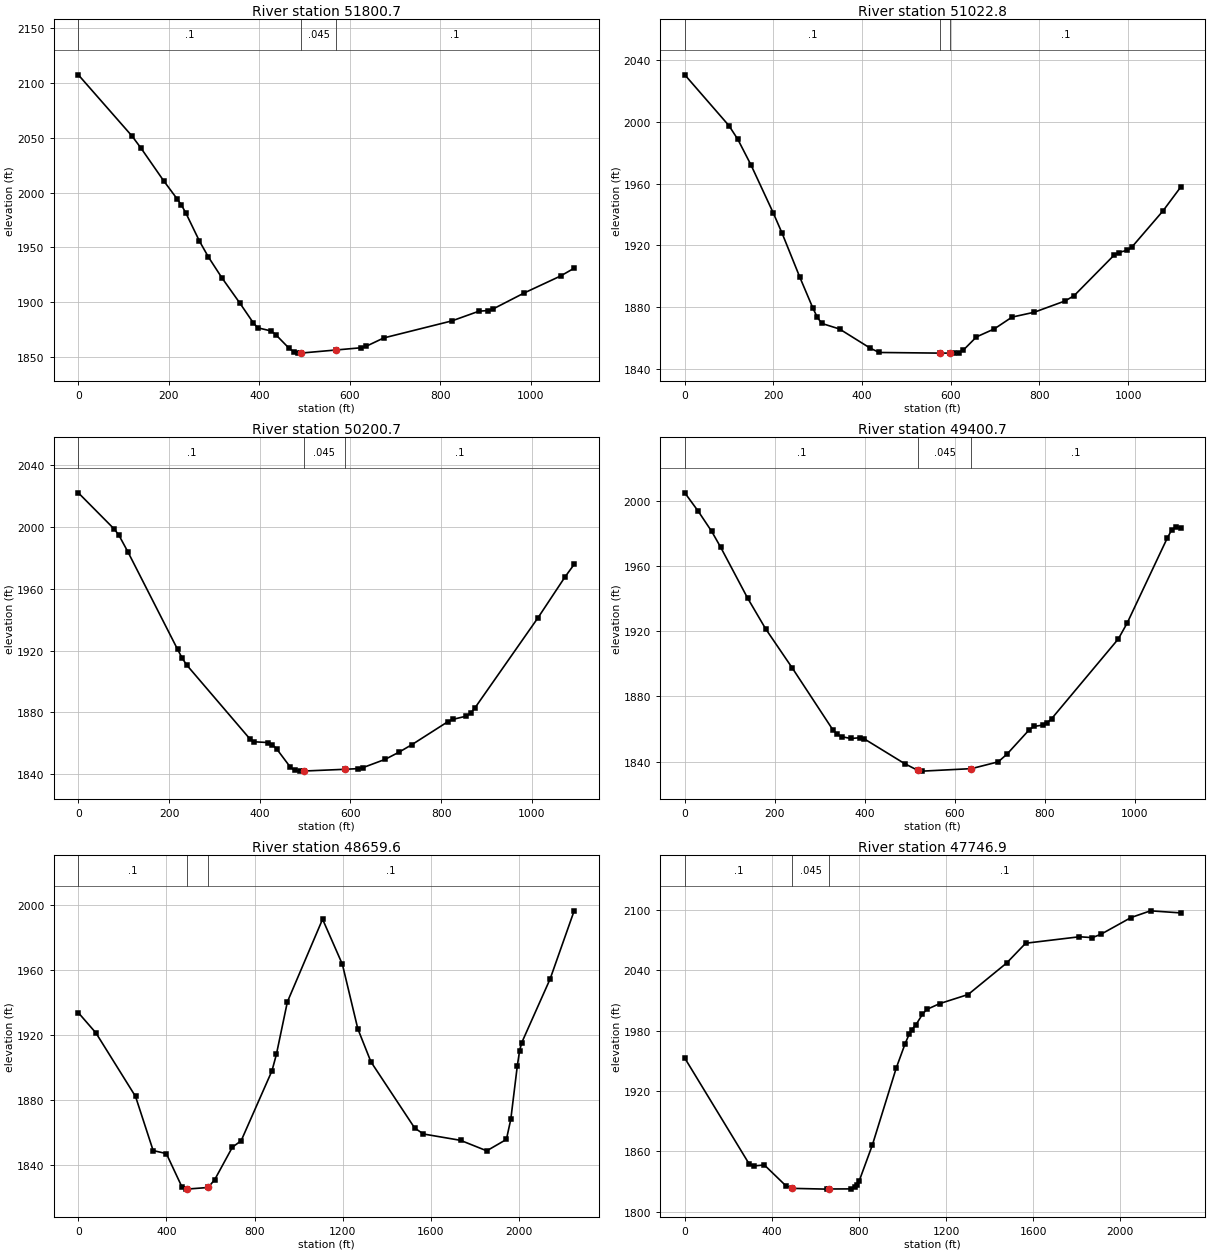
Type RM Length L Ch R = 1 ,51800.7 ,773.5,777.9,781.2
XS GIS Cut Line= 3
     2001119.467      411122.675     2001558.348       410799.29
     2002015.867       410492.63
#Sta/Elev= 30
       0 2107.53   118.9 2051.54   138.8 2040.45   188.3    2011   218.1 1994.41
     228 1988.57   237.9 1981.19   267.6 1955.83   287.4 1941.31   317.2 1922.32
   356.8  1899.3   386.6 1881.24   396.5 1876.65   426.2 1873.74   436.1 1870.49
   465.9  1857.9   475.8 1854.81   485.7 1853.52   492.2 1853.57   570.2 1856.41
   625.3 1858.43   635.3  1859.6   675.3 1867.41   825.6 1882.93   885.6 1891.81
   905.7 1892.37   915.7 1893.62   985.8  1908.5  1065.9 1923.92  1095.9 1931.03
#Mann= 3 , 0 , 0
       0      .1       0   492.2    .045       0   570.2      .1       0
Bank Sta=492.2,570.2
XS Rating Curve= 0 ,0
Exp/Cntr=0.3,0.1

Type RM Length L Ch R = 1 ,51022.8 ,810.3,822.1,835.1
XS GIS Cut Line= 3
     2001587.272      411594.885     2002172.572      411316.704
      2002492.89       410972.12
#Sta/Elev= 30
       0 2030.23    99.7 1997.35   119.6 1988.53   149.6 1971.82   199.4 1941.08
   219.3 1927.99   259.2 1899.63   289.1 1879.36   299.1 1873.47   309.1 1869.56
     349 1865.98   418.7 1853.52   438.7  1850.8   575.7 1850.39   598.2 1850.39
   608.2 1850.38   618.1 1850.73   628.1 1852.27     658 1860.88   698.1 1866.02
   738.1 1873.65   788.2  1876.8   858.2 1884.14   878.3 1887.53   968.4  1913.7
   978.4 1915.38   998.4 1916.87  1008.4 1918.88  1078.5 1942.22  1118.5 1957.62
#Mann= 3 , 0 , 0
       0      .1       0   575.7    .045       0   598.2      .1       0
Bank Sta=575.7,598.2
XS Rating Curve= 0 ,0
Exp/Cntr=0.3,0.1

Type RM Length L Ch R = 1 ,50200.7 ,794.9,799.9,804.5
XS GIS Cut Line= 3
     2001761.235      412061.495     2002306.785      412104.963
     2002848.237      412174.081
#Sta/Elev= 30
       0 2022.23    79.6 1998.62    89.6 1994.69   109.5 1983.85   218.9 1920.75
   228.9 1915.16   238.8 1910.72   378.1 1862.84   388.1 1860.92   417.9 1860.45
   427.9 1859.02   437.8  1856.1   467.7 1844.38   477.6 1842.36   487.6 1841.92
   498.1 1841.99     587  1843.1   616.8 1843.55   626.7 1844.11   676.3 1849.54
   706.1 1854.06   735.8 1859.15   815.2 1874.05   825.2 1875.42   854.9 1877.52
   864.9 1879.54   874.8 1883.07  1013.7 1941.43  1073.3 1967.89  1093.1 1975.87
#Mann= 3 , 0 , 0
       0      .1       0   498.1    .045       0     587      .1       0
Bank Sta=498.1,587
XS Rating Curve= 0 ,0
Exp/Cntr=0.3,0.1

Type RM Length L Ch R = 1 ,49400.7 ,729.3,741.1,752.2
XS GIS Cut Line= 3
     2001690.362      412726.488     2002223.594      412891.289
     2002738.945      413065.069
#Sta/Elev= 30
       0 2004.89    29.9 1993.59    59.8 1981.23    79.7 1971.53   139.5 1940.37
   179.4  1921.6   239.2 1897.33   328.9 1859.61   338.9 1856.77   348.8 1855.34
   368.8 1854.23   388.7 1854.68   398.7 1854.03   488.4 1838.84   518.2 1834.64
   528.2 1834.22   637.2 1835.75   696.6 1839.92   716.3 1844.69   765.8 1859.66
   775.7 1861.62   795.4 1862.44   805.3 1863.74   815.2 1866.35   963.5 1915.28
   983.3 1925.08  1072.3 1977.14  1082.2 1982.14  1092.1 1984.13    1102 1983.04
#Mann= 3 , 0 , 0
       0      .1       0   518.2    .045       0   637.2      .1       0
Bank Sta=518.2,637.2
XS Rating Curve= 0 ,0
Exp/Cntr=0.3,0.1

Type RM Length L Ch R = 1 ,48659.6 ,889.5,912.7,936
XS GIS Cut Line= 3
     2001436.431      413104.313     2002302.589      414030.657
     2002344.464       415011.64
#Sta/Elev= 30
       0 1933.91    79.9 1921.42   259.6 1882.26   339.5 1848.92   399.4 1847.06
   469.3 1826.75   489.3 1825.15   494.5 1825.19   589.2 1826.16   619.1 1831.04
     699 1850.98     739    1855   878.8 1898.11   898.7 1908.14   948.7 1940.58
  1108.4 1991.54  1198.3 1963.73  1268.2 1924.03  1327.7 1903.65  1526.1 1862.86
  1565.7 1859.14  1734.4 1855.23  1853.4 1848.77  1942.6 1855.78  1962.5 1868.15
  1992.2 1901.21  2002.1 1910.06    2012 1915.38    2141  1954.7  2250.1  1996.7
#Mann= 3 , 0 , 0
       0      .1       0   494.5    .045       0   589.2      .1       0
Bank Sta=494.5,589.2
XS Rating Curve= 0 ,0
Exp/Cntr=0.3,0.1

Type RM Length L Ch R = 1 ,47746.9 ,733.8,746.2,758.4
XS GIS Cut Line= 5
     2001186.364      413207.189     2001006.124      413833.599
     2000762.297      414457.588     2000760.908      414701.944
      2001111.72      415321.344
#Sta/Elev= 30
       0 1952.75   296.3 1847.28     316 1845.49   365.4 1846.48   464.2 1825.84
   493.8 1823.21   651.8 1822.45   661.8 1822.59   761.8 1822.68   781.8 1824.34
   791.8 1826.58   801.8 1830.92   861.8 1866.37   971.8 1943.16  1011.8 1966.87
  1031.8 1977.09  1041.8 1980.86  1061.8  1985.9  1091.8 1996.33  1111.8 2001.21
  1171.8 2007.04  1301.8 2016.04  1478.2 2047.28  1566.1 2067.05  1813.3 2073.48
  1872.6 2072.63  1912.2    2076  2050.6 2092.64  2139.6 2099.28    2278 2097.22
#Mann= 3 , 0 , 0
       0      .1       0   493.8    .045       0   661.8      .1       0
Bank Sta=493.8,661.8
XS Rating Curve= 0 ,0
Exp/Cntr=0.3,0.1

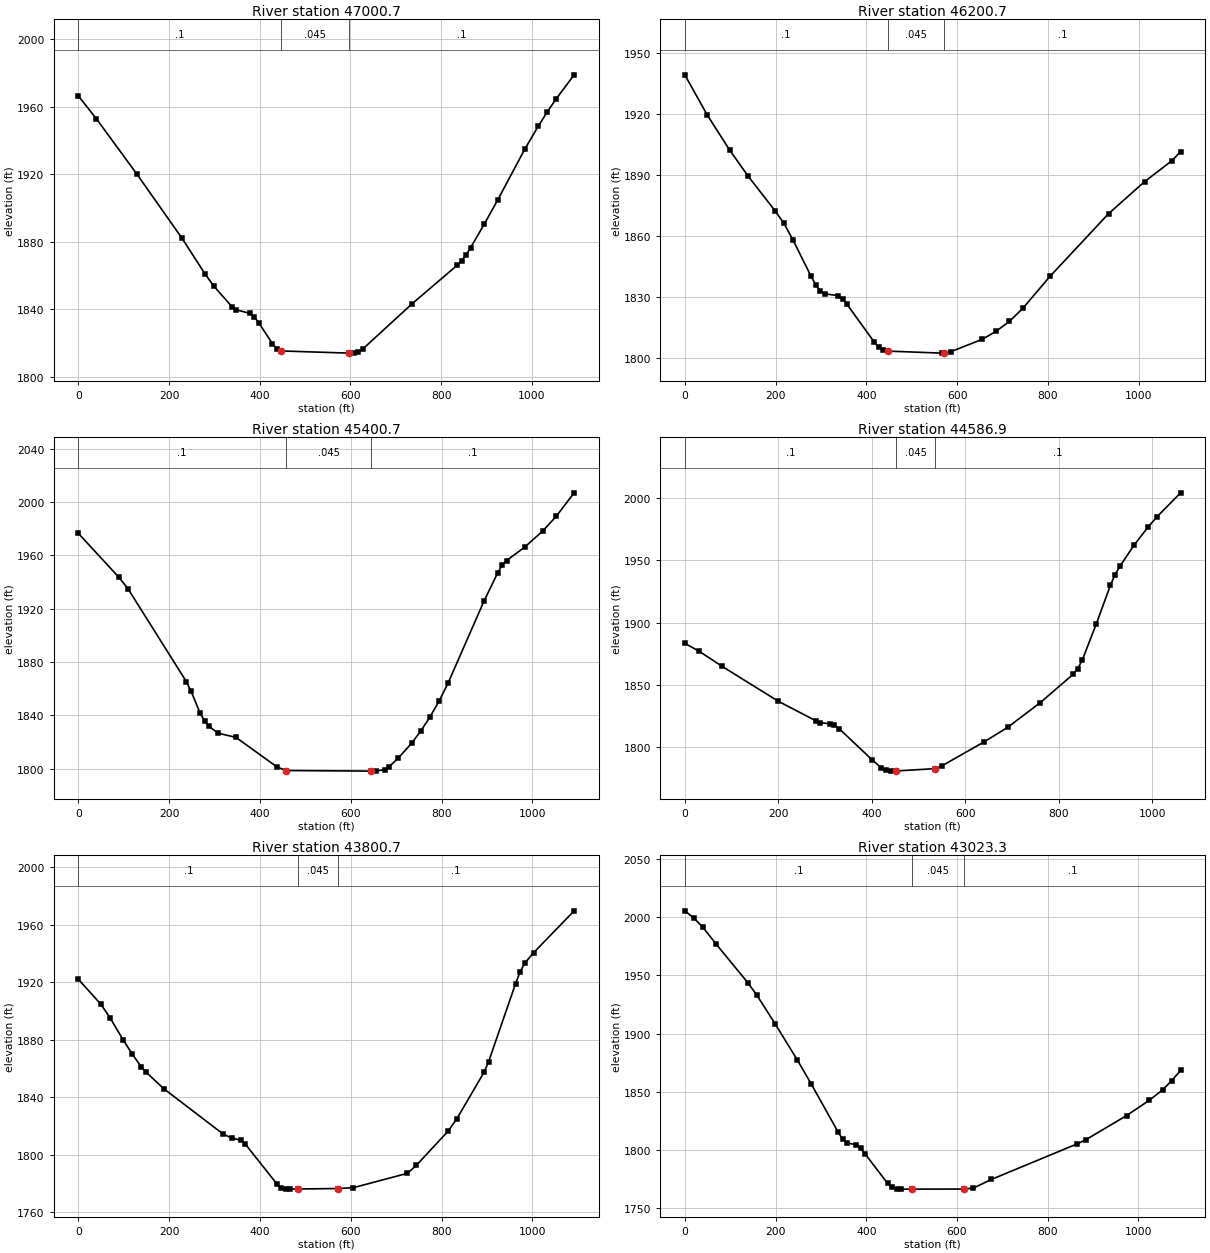
Type RM Length L Ch R = 1 ,47000.7 ,804.7,800,795.8
XS GIS Cut Line= 3
     2000857.301      412928.197      2000453.66      413298.029
     2000055.372      413671.066
#Sta/Elev= 30
       0 1966.39    39.8 1952.82   129.4 1919.93   228.9 1881.94   278.7 1861.16
   298.6 1853.73   338.4 1841.61   348.4 1839.62   378.2 1837.59   388.2 1835.32
   398.2  1831.8     428  1819.6     438 1816.52   447.9 1815.29   597.1    1814
     607 1814.01   616.9 1814.64   626.8 1816.35     736 1843.28   835.2 1866.03
   845.1 1868.71     855 1872.29     865 1876.53   894.7 1890.27   924.5 1904.67
     984 1934.65  1013.8 1948.36  1033.6 1956.78  1053.5 1964.64  1093.2 1978.86
#Mann= 3 , 0 , 0
       0      .1       0   447.9    .045       0   597.1      .1       0
Bank Sta=447.9,597.1
XS Rating Curve= 0 ,0
Exp/Cntr=0.3,0.1

Type RM Length L Ch R = 1 ,46200.7 ,788.2,800,811.6
XS GIS Cut Line= 3
      2000105.51      412432.952     1999787.284      412876.673
     1999464.404      413316.966
#Sta/Elev= 30
       0 1939.28    49.6  1919.5    99.3 1902.15     139 1889.68   198.6 1872.56
   218.4 1866.35   238.3 1858.16     278 1840.38   287.9 1836.27   297.8 1833.25
   307.8 1831.77   337.6 1830.83   347.5 1829.25   357.4 1826.52     417  1808.1
   426.9 1805.47   436.8 1804.06   446.8 1803.61   565.9 1802.61     571 1802.67
   585.8 1803.31   655.2 1809.42     685 1813.25   714.8 1818.15   744.6 1824.65
   804.1 1840.26   933.2 1871.07  1012.6 1886.82  1072.2    1897    1092 1901.54
#Mann= 3 , 0 , 0
       0      .1       0   446.8    .045       0     571      .1       0
Bank Sta=446.8,571
XS Rating Curve= 0 ,0
Exp/Cntr=0.3,0.1

Type RM Length L Ch R = 1 ,45400.7 ,804.3,813.8,823.2
XS GIS Cut Line= 3
     1999734.553       412085.99     1999237.027      412310.899
     1998739.501      412535.807
#Sta/Elev= 30
       0 1976.49    89.4 1943.48   109.2    1935   238.2 1865.06   248.2  1858.1
     268 1841.78     278 1835.76   287.9 1831.62   307.8 1826.58   347.4 1823.36
   436.8 1801.41   456.6 1798.54   645.3 1798.11   655.2 1798.09     675 1799.25
     685 1801.54   704.8 1807.93   734.6 1819.24   754.5 1828.33   774.3 1838.62
   794.2 1850.46     814 1863.91   893.4 1925.63   923.2  1946.6   933.2 1952.41
   943.1 1956.09   982.8 1966.06  1022.5 1978.16  1052.3 1989.17    1092 2006.88
#Mann= 3 , 0 , 0
       0      .1       0   456.6    .045       0   645.3      .1       0
Bank Sta=456.6,645.3
XS Rating Curve= 0 ,0
Exp/Cntr=0.3,0.1

Type RM Length L Ch R = 1 ,44586.9 ,805.7,786.2,766.8
XS GIS Cut Line= 2
     1999589.464      411522.795     1998528.886      411530.024
#Sta/Elev= 30
       0 1883.29      30  1877.1      80 1864.78   200.1 1836.82   280.2 1821.22
   290.2 1819.76   310.2 1818.77   320.2 1817.55   330.2 1814.86   400.2 1790.07
   420.2 1783.45   430.2 1781.45   440.2 1780.82   452.6 1780.96   534.8 1782.81
   550.3 1785.12   640.4 1804.31   690.4 1815.86   760.4 1835.75   830.5 1858.39
   840.5 1862.95   850.5 1870.12   880.5 1899.16   910.5 1929.97   920.5 1938.45
   930.5 1944.96   960.6 1961.82   990.6 1976.38  1010.6 1984.99  1060.6 2003.99
#Mann= 3 , 0 , 0
       0      .1       0   452.6    .045       0   534.8      .1       0
Bank Sta=452.6,534.8
XS Rating Curve= 0 ,0
Exp/Cntr=0.3,0.1

Type RM Length L Ch R = 1 ,43800.7 ,773.3,777.4,781.4
XS GIS Cut Line= 3
     1999081.045      410442.201     1998728.684      410859.283
     1998376.322      411276.365
#Sta/Elev= 30
       0 1921.97    49.6 1904.69    69.5 1895.37    99.3 1879.55   119.1 1869.82
     139    1861   148.9 1857.48   188.6 1845.82   317.7 1814.69   337.5 1811.54
   357.4 1810.24   367.3 1807.59   436.8 1779.91   446.7 1777.14   456.6 1776.15
   466.6 1776.11   484.2  1776.2     571 1776.53   605.6 1777.11   724.7 1787.09
   744.6  1792.7     814  1816.3   833.9 1825.17   893.4  1857.3   903.4 1864.53
     963 1919.01   972.9 1927.12   982.8 1933.06  1002.6 1940.44    1092 1969.59
#Mann= 3 , 0 , 0
       0      .1       0   484.2    .045       0     571      .1       0
Bank Sta=484.2,571
XS Rating Curve= 0 ,0
Exp/Cntr=0.3,0.1

Type RM Length L Ch R = 1 ,43023.3 ,821.2,822.6,824
XS GIS Cut Line= 2
      1998610.61      409955.532     1997766.934        410650.3
#Sta/Elev= 30
       0 2005.36    19.9 1999.19    39.7 1991.35    69.6 1976.53   139.1 1943.61
     159 1932.85   198.7 1908.63   248.4  1877.1   278.2 1857.11   337.8 1815.54
   347.8 1809.32   357.7 1806.21   377.6 1804.47   387.5 1801.43   397.4 1796.74
   447.1 1771.39     457 1767.96     467 1766.64   476.9 1766.49   501.4 1766.49
     616 1766.55   635.9 1767.38   675.6 1774.77   864.4 1805.26   884.3 1808.96
   973.7  1829.6  1023.4  1842.6  1053.2 1851.73  1073.1 1859.58  1092.9 1868.32
#Mann= 3 , 0 , 0
       0      .1       0   501.4    .045       0     616      .1       0
Bank Sta=501.4,616
XS Rating Curve= 0 ,0
Exp/Cntr=0.3,0.1

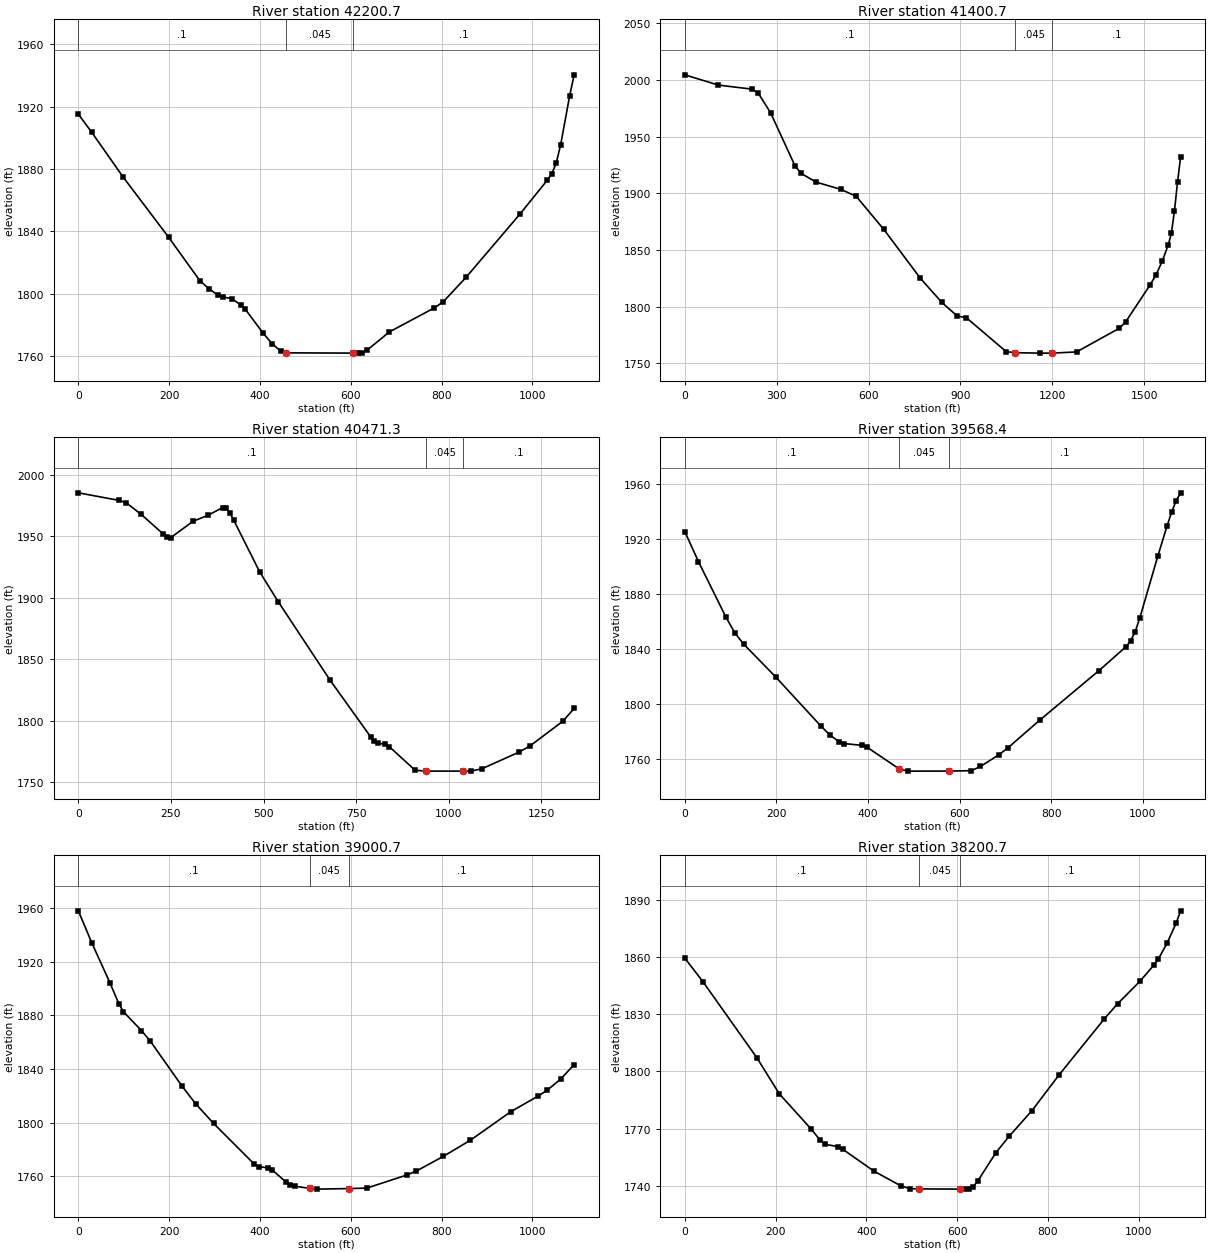
Type RM Length L Ch R = 1 ,42200.7 ,802,800,800.5
XS GIS Cut Line= 3
     1998042.274      409419.172     1997599.643       409738.85
     1997157.012      410058.528
#Sta/Elev= 30
       0 1915.13    29.8 1903.37    99.3 1874.55   198.6 1836.32     268 1808.27
   287.9 1803.14   307.8 1799.06   317.7 1797.89   337.5 1796.96   357.4 1792.87
   367.3 1790.25     407 1774.72   426.9 1767.96   446.7 1763.03   456.6 1762.13
   605.6 1761.96   615.5 1761.95   625.4 1762.34   635.4 1763.73     685 1775.53
   784.2 1790.97   804.1 1794.98   853.8  1810.5   972.9 1851.18  1032.4 1872.64
  1042.4 1876.77  1052.3  1883.6  1062.2 1895.36  1082.1 1926.95    1092 1940.33
#Mann= 3 , 0 , 0
       0      .1       0   456.6    .045       0   605.6      .1       0
Bank Sta=456.6,605.6
XS Rating Curve= 0 ,0
Exp/Cntr=0.3,0.1

Type RM Length L Ch R = 1 ,41400.7 ,962.3,929.3,893.9
XS GIS Cut Line= 3
     1998046.017      408298.795     1997115.859      409102.067
     1996795.263      409323.759
#Sta/Elev= 30
       0 2004.56   109.9  1995.5   219.8 1991.91   239.8 1988.36   279.8 1971.22
   359.7 1924.29   379.7 1917.52   429.6 1909.82   509.6 1903.47   559.5 1897.36
   649.5 1868.23   769.4 1824.94   839.3  1803.7   889.3 1791.77   919.2 1790.24
  1049.2 1760.34  1079.1 1759.36  1159.1 1758.99    1199 1758.99    1279 1760.05
  1418.9 1780.97  1438.9 1786.39  1518.8 1819.01  1538.8 1828.22  1558.8 1840.15
  1578.8 1854.81  1588.8 1865.09  1598.8 1884.74  1608.8  1910.1  1618.8  1932.3
#Mann= 3 , 0 , 0
       0      .1       0  1079.1    .045       0    1199      .1       0
Bank Sta=1079.1,1199
XS Rating Curve= 0 ,0
Exp/Cntr=0.3,0.1

Type RM Length L Ch R = 1 ,40471.3 ,921.8,902.9,884.1
XS GIS Cut Line= 2
     1995780.148      408058.172     1996538.196      409161.695
#Sta/Elev= 30
       0 1985.13   109.9    1979   129.9 1976.93   169.8 1967.59   229.8 1951.51
   239.8  1949.3   249.8 1948.76   309.7 1962.01   349.7  1966.8   389.6 1973.14
   399.6 1972.42   409.6 1968.59   419.6 1962.93   489.6 1920.92   539.5 1896.78
   679.4 1833.04   789.3 1786.85   799.3 1783.34   809.3  1781.6   829.3  1780.8
   839.2 1778.98   909.2 1759.72   939.2 1758.99  1038.3 1758.99    1059 1758.98
    1089  1760.8  1188.9 1774.28  1218.9 1779.27  1308.8 1799.67  1338.8 1809.96
#Mann= 3 , 0 , 0
       0      .1       0   939.2    .045       0  1038.3      .1       0
Bank Sta=939.2,1038.3
XS Rating Curve= 0 ,0
Exp/Cntr=0.3,0.1

Type RM Length L Ch R = 1 ,39568.4 ,572.8,567.7,562.6
XS GIS Cut Line= 2
      1995456.84      409628.327     1996530.163      409772.091
#Sta/Elev= 30
       0  1925.4    29.8 1903.58    89.4 1863.55   109.3 1851.77   129.2 1843.44
   198.7 1819.74     298 1783.89   317.9 1777.37   337.8 1772.66   347.7 1771.47
   387.5 1770.14   397.4 1768.95   468.1 1753.08   486.8 1751.44   576.2 1751.47
   625.9 1751.77   645.8 1754.86   685.5 1763.22   705.4 1768.24   774.9 1788.36
   904.1 1824.29   963.7 1841.81   973.6 1845.91   983.6 1852.67   993.5 1862.37
  1033.2 1907.67  1053.1 1929.28    1063 1939.22    1073 1947.74  1082.9  1953.5
#Mann= 3 , 0 , 0
       0      .1       0   468.1    .045       0   576.2      .1       0
Bank Sta=468.1,576.2
XS Rating Curve= 0 ,0
Exp/Cntr=0.3,0.1

Type RM Length L Ch R = 1 ,39000.7 ,781.6,800,817.7
XS GIS Cut Line= 3
     1995427.033      410314.256     1995970.649      410263.292
     1996514.266      410212.329
#Sta/Elev= 30
       0 1958.09    29.8 1934.09    69.5 1904.46    89.4 1888.64    99.3 1882.81
     139 1868.75   158.8 1860.74   228.3 1827.35   258.1 1814.24   297.8  1799.5
   387.2 1769.21   397.1 1767.26     417 1766.35   426.9 1764.78   456.6 1755.99
   466.6  1753.8   476.5 1752.66   509.3 1751.04   526.2 1750.46   595.6 1750.88
   635.4 1751.22   724.7 1761.15   744.6 1763.98   804.1 1774.93   863.7    1787
     953 1808.35  1012.6 1819.89  1032.4 1824.24  1062.2 1832.51    1092 1843.39
#Mann= 3 , 0 , 0
       0      .1       0   509.3    .045       0   595.6      .1       0
Bank Sta=509.3,595.6
XS Rating Curve= 0 ,0
Exp/Cntr=0.3,0.1

Type RM Length L Ch R = 1 ,38200.7 ,794.7,800,805.9
XS GIS Cut Line= 3
     1995298.679      410634.002     1995709.329      410994.225
     1996129.582      411342.728
#Sta/Elev= 30
       0 1859.49    39.7 1847.22   158.9 1807.12   208.6  1788.1   278.1 1769.81
     298 1763.92   307.9 1761.78   337.7 1760.48   347.6 1759.16   417.1 1747.56
   476.7 1739.82   496.6  1738.4   516.5  1738.3   605.8 1738.19   615.7 1738.18
   625.7 1738.36   635.6 1739.55   645.5  1742.5   685.2 1757.31     715 1766.08
   764.6 1779.37   824.2 1798.09   923.5 1827.44   953.2  1835.5  1002.9 1847.44
  1032.6 1855.66  1042.6 1858.84  1062.4 1867.36  1082.3 1877.89  1092.2 1884.35
#Mann= 3 , 0 , 0
       0      .1       0   516.5    .045       0   605.8      .1       0
Bank Sta=516.5,605.8
XS Rating Curve= 0 ,0
Exp/Cntr=0.3,0.1

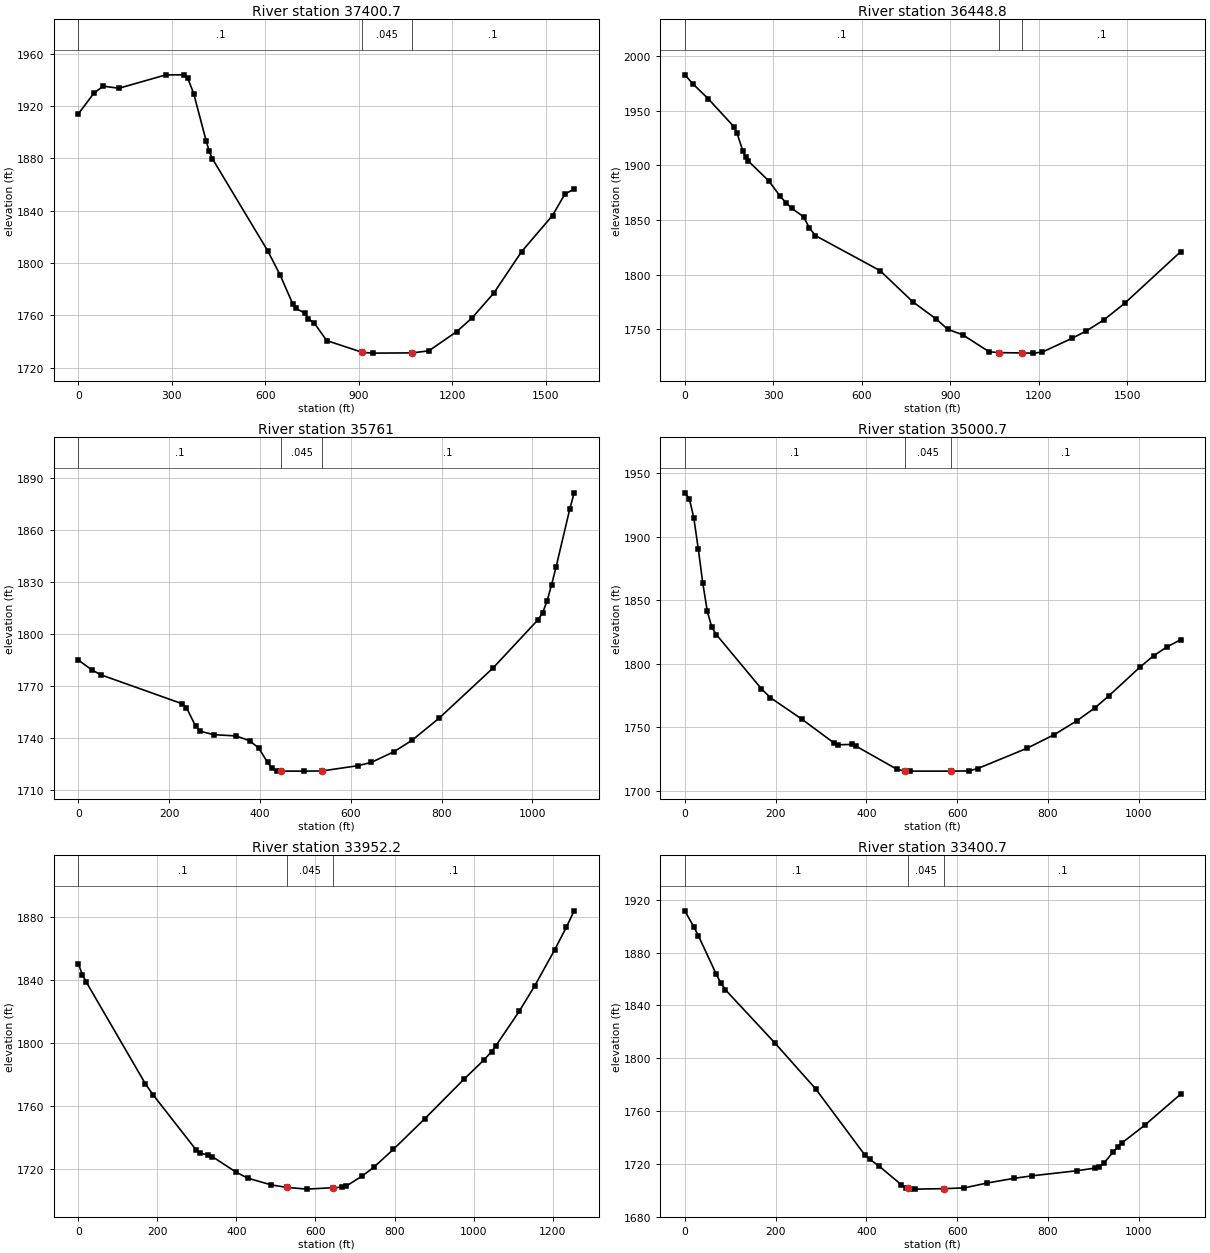
Type RM Length L Ch R = 1 ,37400.7 ,959.6,951.9,944.2
XS GIS Cut Line= 4
     1994465.525      410617.829     1994668.579      410903.334
     1995071.524       411469.42     1995388.166      411914.227
#Sta/Elev= 30
       0  1914.1      50 1929.98    80.1 1935.33   130.1 1933.72   280.3 1943.93
   340.3    1944   350.4 1941.85   370.2  1929.7   409.9 1893.75   419.8 1885.61
   429.8 1879.98   608.4 1809.11   648.1 1790.58   687.8 1768.93   697.8  1765.3
   727.6 1761.65   737.5 1757.51   757.3 1754.02     797 1740.72   911.7 1731.67
   945.9  1731.1  1070.2 1731.28  1124.6 1732.83    1214 1747.51  1263.6 1758.05
  1333.1 1776.97  1422.4 1808.71  1521.7 1836.38  1561.4 1852.77  1591.2 1856.58
#Mann= 3 , 0 , 0
       0      .1       0   911.7    .045       0  1070.2      .1       0
Bank Sta=911.7,1070.2
XS Rating Curve= 0 ,0
Exp/Cntr=0.3,0.1

Type RM Length L Ch R = 1 ,36448.8 ,703.1,687.7,672.4
XS GIS Cut Line= 3
     1993582.224      411379.797     1993802.597      411716.715
      1994849.69      412451.419
#Sta/Elev= 30
       0 1982.66    29.5 1973.83    78.6 1960.99   166.9 1935.14   176.8  1929.6
   196.4 1913.33   206.2  1907.3     216 1903.63   284.8 1885.64     324 1871.44
   343.7 1865.56   363.3 1860.45   402.6 1852.88   422.6 1842.65   442.6 1835.67
   662.4 1803.55   772.3 1775.28   852.3 1759.39   892.3 1749.83   942.2 1744.97
  1032.2 1729.35  1065.5 1728.59  1143.5 1728.28  1182.1 1728.12    1212    1729
    1312  1741.5  1361.9 1748.41  1421.9 1758.62  1491.8 1773.67  1681.7 1820.86
#Mann= 3 , 0 , 0
       0      .1       0  1065.5    .045       0  1143.5      .1       0
Bank Sta=1065.5,1143.5
XS Rating Curve= 0 ,0
Exp/Cntr=0.3,0.1

Type RM Length L Ch R = 1 ,35761   ,767.3,760.3,753.3
XS GIS Cut Line= 3
     1993788.817      412814.613     1994333.493      412776.612
     1994878.169      412738.611
#Sta/Elev= 30
       0 1785.11    29.8 1779.42    49.6 1776.62   228.3 1759.99   238.2  1757.7
   258.1 1747.12     268 1744.18   297.8 1742.15   347.4 1741.42   377.2 1738.64
   397.1 1734.49   416.8 1726.18   426.9 1722.73   436.8 1721.38   446.7 1721.17
   496.4 1721.15   536.1 1721.23   615.5 1724.27   645.3 1726.18   694.9  1732.3
   734.6 1738.84   794.2 1751.56   913.3 1780.51  1012.6 1808.38  1022.5 1812.29
  1032.4 1819.22  1042.4 1828.55  1052.3 1838.85  1082.1 1871.82    1092  1881.4
#Mann= 3 , 0 , 0
       0      .1       0   446.7    .045       0   536.1      .1       0
Bank Sta=446.7,536.1
XS Rating Curve= 0 ,0
Exp/Cntr=0.3,0.1

Type RM Length L Ch R = 1 ,35000.7 ,1037.9,1048.5,1059.1
XS GIS Cut Line= 3
     1993874.384      413730.611     1994381.333      413527.832
     1994888.281      413325.053
#Sta/Elev= 30
       0 1934.72     9.9 1930.23    19.8    1915    29.8 1890.34    39.7 1863.38
    49.6  1841.4    59.6 1828.68    69.5 1823.07   168.8 1780.39   188.6 1773.41
   258.1 1756.42   327.6 1738.01   337.5 1736.34   367.3  1736.6   377.2 1735.25
   466.6 1717.17   484.3 1715.65   496.4 1715.58   585.7 1715.58   625.4 1715.73
   645.3 1717.64   754.5 1733.71     814 1744.38   863.7 1755.25   903.4 1765.46
   933.2 1774.62  1002.6 1797.52  1032.4 1806.42  1062.2 1813.45    1092 1819.04
#Mann= 3 , 0 , 0
       0      .1       0   484.3    .045       0   585.7      .1       0
Bank Sta=484.3,585.7
XS Rating Curve= 0 ,0
Exp/Cntr=0.3,0.1

Type RM Length L Ch R = 1 ,33952.2 ,554.6,551.5,548.4
XS GIS Cut Line= 3
     1994073.711      414417.588     1994668.876      414473.472
     1995322.719      414534.944
#Sta/Elev= 30
       0 1850.14      10 1843.27    19.9 1838.58   169.4 1773.95   189.3  1766.8
   298.9 1731.56   308.8 1729.58   328.8 1728.79   338.7 1727.62   398.5 1717.83
   428.4 1713.92   488.2 1709.62   526.8 1708.05   577.9 1706.93   645.6 1707.85
   667.4 1708.16   677.4 1708.79   717.2 1715.11     747 1720.68   796.8 1732.14
   876.4 1751.62   975.9 1776.81  1025.6 1788.84  1045.6  1794.3  1055.5 1797.66
  1115.2 1819.79    1155 1836.21  1204.8 1858.77  1234.6 1873.25  1254.5 1883.74
#Mann= 3 , 0 , 0
       0      .1       0   526.8    .045       0   645.6      .1       0
Bank Sta=526.8,645.6
XS Rating Curve= 0 ,0
Exp/Cntr=0.3,0.1

Type RM Length L Ch R = 1 ,33400.7 ,805.5,800,792.4
XS GIS Cut Line= 3
     1994020.545      415032.142     1994565.886      415005.321
     1995111.227      414978.501
#Sta/Elev= 30
       0 1911.66    19.8 1899.54    29.8 1892.86    69.5 1863.59    79.4 1856.96
    89.4 1851.88   198.6 1811.51   287.9 1776.97   397.1 1726.51     407 1723.54
   426.9 1718.63   476.5 1704.36   486.4 1702.07     491  1701.6   496.4 1701.04
   506.3 1700.91     571 1701.27   615.5 1701.84   665.1 1705.49   724.7 1709.06
   764.4 1710.98   863.7 1714.84   903.4 1716.84   913.3 1717.96   923.2 1720.56
   943.1 1728.98     953 1732.79     963 1735.97  1012.6  1749.2    1092 1772.82
#Mann= 3 , 0 , 0
       0      .1       0     491    .045       0     571      .1       0
Bank Sta=491,571
XS Rating Curve= 0 ,0
Exp/Cntr=0.3,0.1