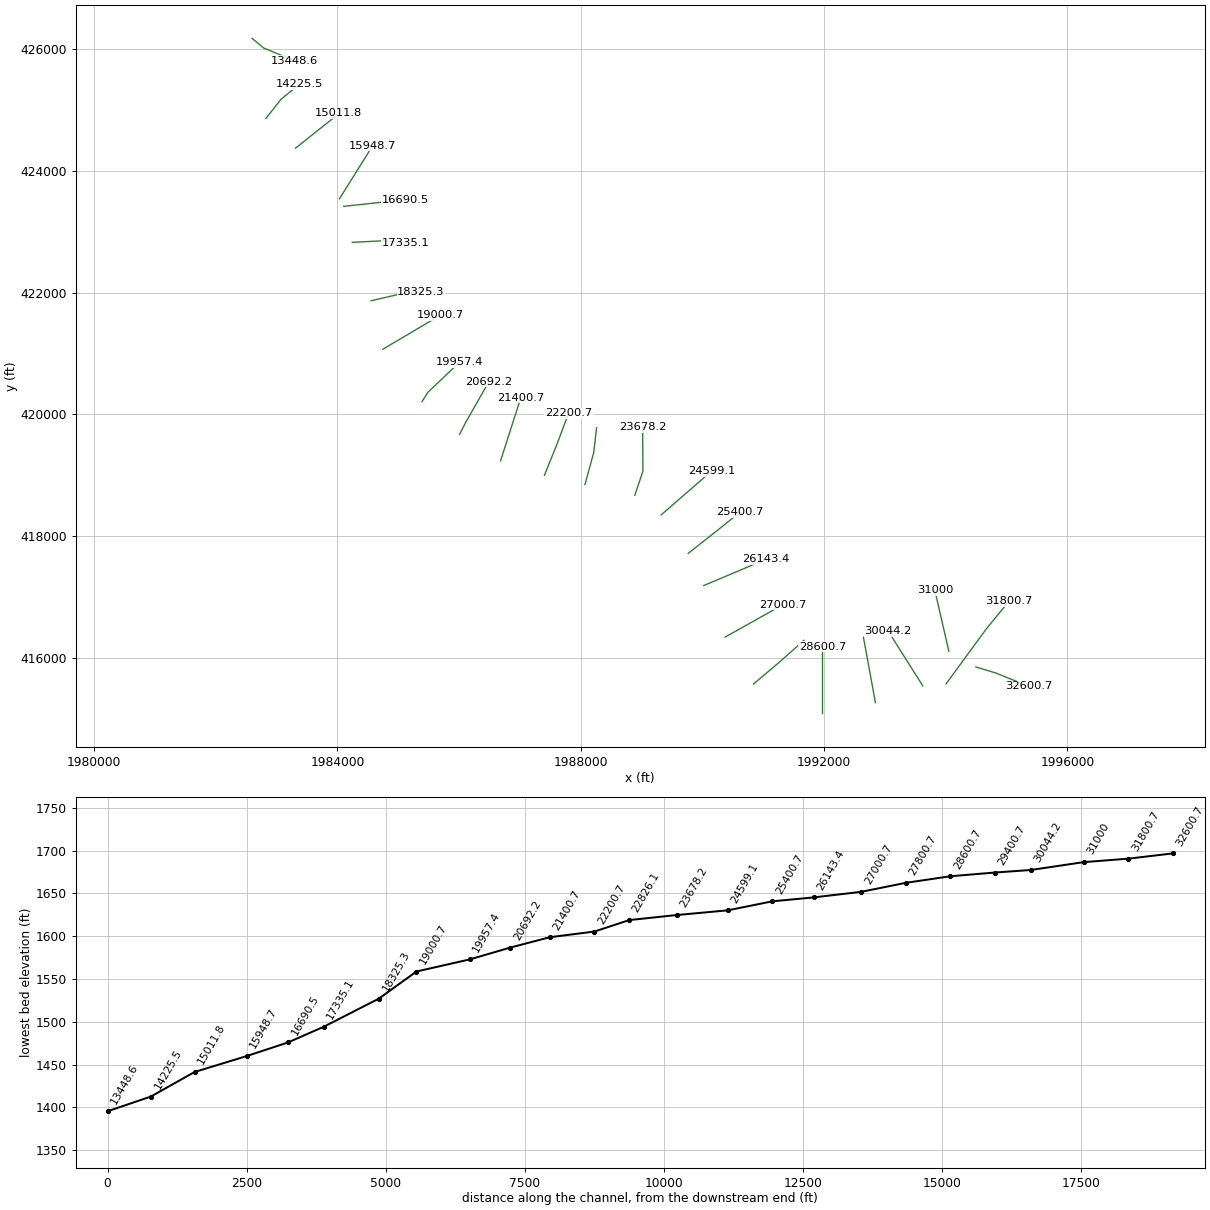
HEC-RAS study MeadowRvr.prj: MeadowRvr

--- MeadowRvr.g01 (geometry) --- (continued)

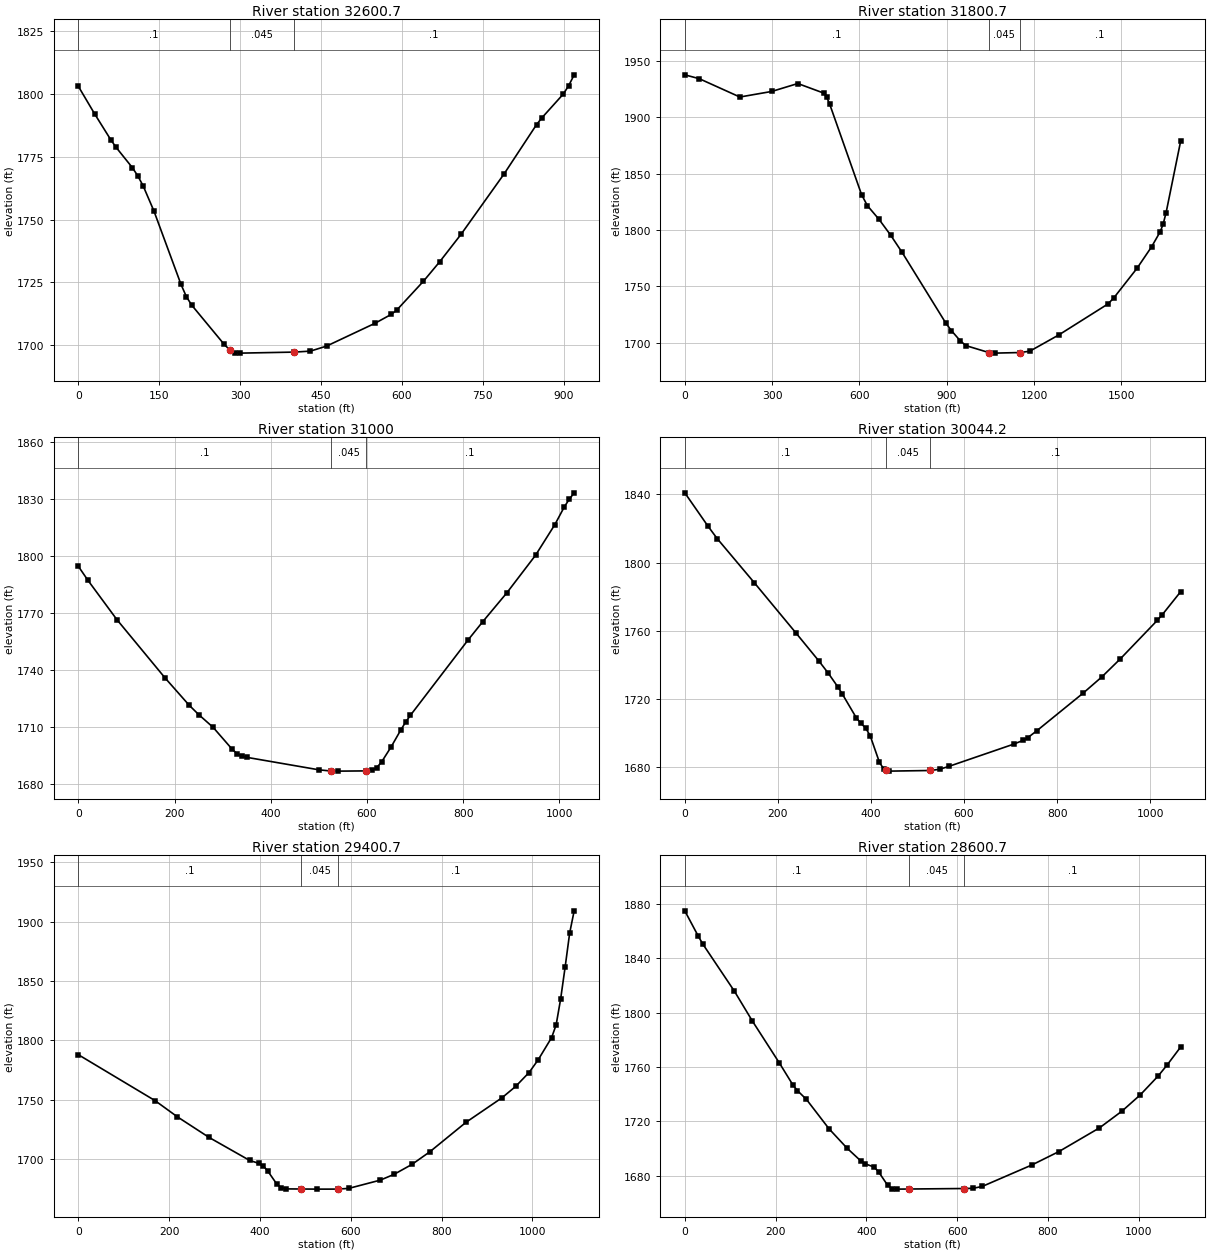
Type RM Length L Ch R = 1 ,32600.7 ,772.2,800,828.7
XS GIS Cut Line= 3
     1994495.635      415851.013     1994821.649      415752.646
     1995358.112      415535.734
#Sta/Elev= 30
       0 1803.04      30 1792.14    60.1 1781.78    70.1 1778.72   100.2 1770.66
   110.2  1767.4   120.2 1763.39   140.2 1753.38   190.3 1724.21   200.3 1719.31
   210.3 1715.91   270.4 1700.32   280.9 1698.09   290.4 1697.05   300.5 1696.84
   400.4 1697.25   430.3 1697.64   460.2 1699.64     550 1708.72     580 1712.25
     590  1713.9   639.8 1725.46   669.8 1733.17   709.7 1744.19   789.5 1768.23
   849.4 1787.77   859.3 1790.48   899.2 1799.99   909.2 1803.36   919.2 1807.61
#Mann= 3 , 0 , 0
       0      .1       0   280.9    .045       0   400.4      .1       0
Bank Sta=280.9,400.4
XS Rating Curve= 0 ,0
Exp/Cntr=0.3,0.1

Type RM Length L Ch R = 1 ,31800.7 ,781.3,800.7,821.3
XS GIS Cut Line= 3
     1994006.039      415574.013      1994671.01      416481.678
      1995037.71      416929.109
#Sta/Elev= 30
       0 1937.67    49.8 1934.23   189.2 1917.98   298.7 1922.92   388.3 1929.95
     478  1921.4   487.9 1917.69   497.9  1911.6   607.4 1831.38   627.3 1821.58
   667.2 1809.47     707 1795.51   746.8 1780.06   896.2 1717.62   916.1 1710.66
     946 1701.79   965.9 1697.37  1045.5 1691.16  1065.4  1690.7  1150.2 1691.22
    1185 1692.35  1284.8  1706.8  1454.3 1734.38  1474.3 1739.78  1554.1 1766.06
  1603.9 1785.04  1633.9 1798.62  1643.8 1805.36  1653.8  1815.4  1703.7 1878.74
#Mann= 3 , 0 , 0
       0      .1       0  1045.5    .045       0  1150.2      .1       0
Bank Sta=1045.5,1150.2
XS Rating Curve= 0 ,0
Exp/Cntr=0.3,0.1

Type RM Length L Ch R = 1 ,31000   ,948.2,955.8,963.4
XS GIS Cut Line= 2
     1994050.858      416110.062      1993820.24      417114.477
#Sta/Elev= 30
       0  1794.4      20    1787      80 1766.39   180.1 1735.72   230.1 1721.39
   250.1 1716.41   280.2 1709.67   320.2 1698.04   330.2 1695.79   340.2 1694.48
   350.2  1693.9   500.3 1687.33   525.1  1686.7   540.3 1686.65   598.2 1686.77
   610.3 1687.08   620.3 1688.52   630.3 1691.47   650.4  1699.5   670.4 1708.37
   680.4 1712.47   690.4 1716.06   810.4 1755.74   840.4 1765.19   890.5 1780.38
   950.5 1800.26   990.5 1816.34  1010.5 1825.82  1020.5 1829.68  1030.6 1833.04
#Mann= 3 , 0 , 0
       0      .1       0   525.1    .045       0   598.2      .1       0
Bank Sta=525.1,598.2
XS Rating Curve= 0 ,0
Exp/Cntr=0.3,0.1

Type RM Length L Ch R = 1 ,30044.2 ,652.1,643.5,634.9
XS GIS Cut Line= 2
     1993621.828      415541.887     1993052.661      416442.438
#Sta/Elev= 30
       0 1840.97    49.8 1821.38    69.7 1814.04   149.4 1788.13     239 1758.56
   288.7 1741.95   308.6 1734.86   328.6 1727.02   338.5 1722.72   368.4 1708.83
   378.3 1705.51   388.3 1702.88   398.3 1698.23   418.2  1682.6   428.1  1678.4
     432 1678.03   438.1 1677.44   527.7 1677.81   547.6 1678.53   567.5 1680.24
   706.9 1693.32   726.8 1695.52   736.8 1697.07   756.7 1701.24   856.2 1723.35
   896.1 1732.82   935.9 1743.45  1015.6 1766.15  1025.5 1769.23  1065.3 1782.85
#Mann= 3 , 0 , 0
       0      .1       0     432    .045       0   527.7      .1       0
Bank Sta=432,527.7
XS Rating Curve= 0 ,0
Exp/Cntr=0.3,0.1

Type RM Length L Ch R = 1 ,29400.7 ,804.1,800,795.9
XS GIS Cut Line= 3
     1992844.213      415264.001      1992745.82      415801.062
     1992647.427      416338.123
#Sta/Elev= 30
       0 1787.84   168.8 1749.14   218.4 1735.38   287.9 1718.09   377.2  1698.7
   397.1 1696.26     407  1694.2     417 1689.84   436.8  1678.9   446.7  1675.7
   456.6 1674.68   491.1 1674.58   526.2 1674.48     571  1674.5   595.6  1675.1
   665.1 1682.08   694.9 1686.86   734.6 1695.28   774.3 1706.01   853.8 1730.82
   933.2 1751.55     963 1761.03   992.7 1772.81  1012.6 1783.43  1042.4 1802.29
  1052.3 1812.95  1062.2 1834.75  1072.2 1861.93  1082.1  1890.4    1092 1909.14
#Mann= 3 , 0 , 0
       0      .1       0   491.1    .045       0     571      .1       0
Bank Sta=491.1,571
XS Rating Curve= 0 ,0
Exp/Cntr=0.3,0.1

Type RM Length L Ch R = 1 ,28600.7 ,819.7,800,780.9
XS GIS Cut Line= 3
     1991970.433      415088.819     1991970.433      415634.819
     1991970.433      416180.819
#Sta/Elev= 30
       0  1875.1    29.8 1856.36    39.7 1850.61   109.2 1815.94   148.9  1793.9
   208.5 1762.92   238.3 1746.74   248.2 1742.64     268 1736.17   317.7 1714.54
   357.4 1700.28   387.2 1691.03   397.1 1688.78     417 1686.39   426.9  1682.8
   446.7 1672.98   456.7 1670.51   466.6 1670.13     494 1670.21   615.5 1670.58
   635.4 1670.75   655.2 1672.13   764.4 1687.92     824  1697.8   913.3 1715.25
     963 1727.63  1002.7 1739.41  1042.4  1753.4  1062.2 1761.53    1092 1774.78
#Mann= 3 , 0 , 0
       0      .1       0     494    .045       0   615.5      .1       0
Bank Sta=494,615.5
XS Rating Curve= 0 ,0
Exp/Cntr=0.3,0.1

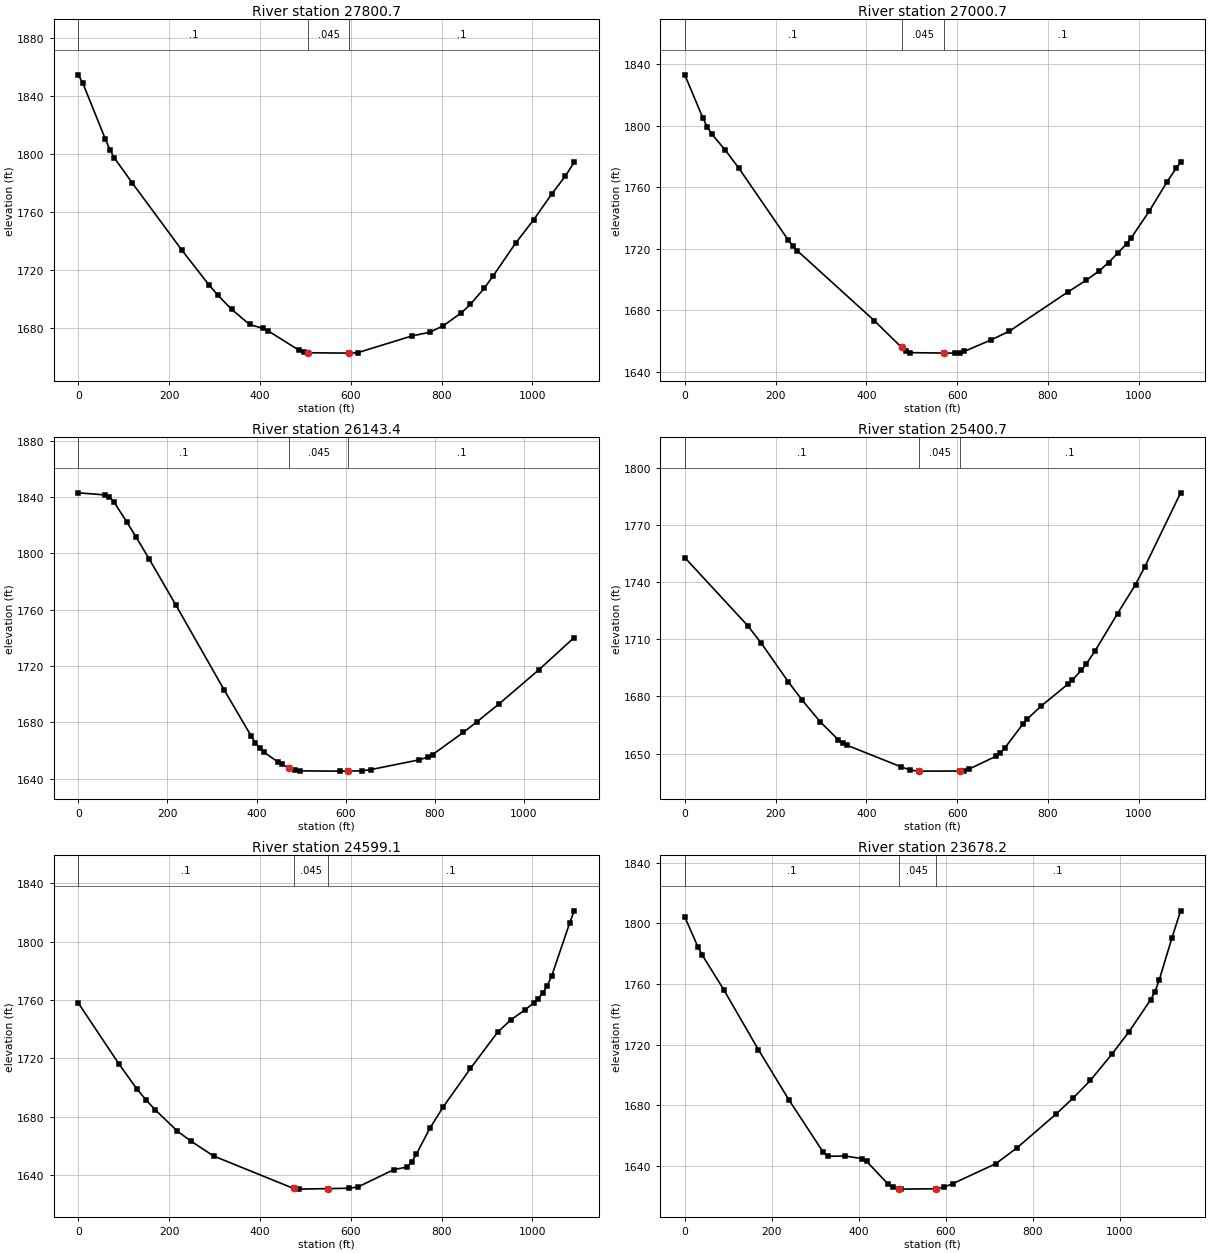
Type RM Length L Ch R = 1 ,27800.7 ,804.3,800,795.1
XS GIS Cut Line= 3
     1990842.602      415573.442     1991259.876      415925.517
     1991668.239      416288.271
#Sta/Elev= 30
       0 1854.28     9.9 1848.54    59.6 1809.93    69.5  1802.7    79.4    1797
   119.1  1779.6   228.3 1733.34   287.9 1709.42   307.7 1702.25   337.5 1692.68
   377.2 1682.21     407 1679.47   416.9 1678.03   486.4 1664.38   496.3 1663.17
   506.3  1662.7   595.6 1662.45   615.5 1662.77   734.6 1674.26   774.4 1676.88
   804.2 1681.38   843.9 1690.28   863.8 1696.11   893.6    1707   913.4 1715.52
   963.1 1738.22  1002.8  1754.3  1042.5 1771.97  1072.3  1784.3  1092.2 1793.93
#Mann= 3 , 0 , 0
       0      .1       0   506.3    .045       0   595.6      .1       0
Bank Sta=506.3,595.6
XS Rating Curve= 0 ,0
Exp/Cntr=0.3,0.1

Type RM Length L Ch R = 1 ,27000.7 ,859.7,857.2,854.7
XS GIS Cut Line= 3
     1990373.743      416342.626     1990850.192      416609.295
     1991326.641      416875.964
#Sta/Elev= 30
       0 1832.98    39.7 1804.99    49.6 1798.94    59.6 1794.38    89.4 1783.91
   119.1 1772.25   228.3 1725.31   238.2 1721.49   248.2 1718.44     417 1673.18
   477.6 1655.63   486.4 1653.43   496.4 1652.28     571 1651.99   595.6 1651.96
   605.6 1652.23   615.5 1653.08     675  1660.6   714.8 1666.24   843.8 1691.76
   883.5 1699.28   913.3 1705.58   933.2  1710.9     953  1716.8   972.9 1723.11
   982.8 1726.77  1022.5 1744.13  1062.2 1763.39  1082.1 1772.17    1092 1776.11
#Mann= 3 , 0 , 0
       0      .1       0   477.6    .045       0     571      .1       0
Bank Sta=477.6,571
XS Rating Curve= 0 ,0
Exp/Cntr=0.3,0.1

Type RM Length L Ch R = 1 ,26143.4 ,736.7,742.8,748.9
XS GIS Cut Line= 2
     1990022.354      417188.508     1991047.647      417620.687
#Sta/Elev= 30
       0 1843.05    59.6 1841.57    69.5 1840.16    79.5 1836.78   109.3 1822.06
   129.2 1811.85     159 1796.07   218.6 1763.48   327.8 1702.77   387.4 1670.59
   397.4 1665.45   407.3 1661.47   417.2 1658.71     447 1652.08     457 1650.15
     473  1647.6   486.8 1646.08   496.7 1645.56   586.1 1645.39     606 1645.43
   635.8 1645.56   655.7 1646.43     765 1653.42   784.8 1655.37   794.8  1657.1
   864.3 1672.97   894.1  1680.3   943.8 1693.06  1033.2 1717.26  1112.7 1740.28
#Mann= 3 , 0 , 0
       0      .1       0     473    .045       0     606      .1       0
Bank Sta=473,606
XS Rating Curve= 0 ,0
Exp/Cntr=0.3,0.1

Type RM Length L Ch R = 1 ,25400.7 ,800.5,801.5,802.5
XS GIS Cut Line= 3
     1989766.224      417716.906     1990195.033      418054.947
     1990622.101      418395.099
#Sta/Elev= 30
       0 1752.83     139 1717.02   168.8 1707.84   228.3 1687.56   258.1  1678.2
   297.8 1666.83   337.6 1657.37   347.5 1655.55   357.4  1654.4   476.5 1643.08
   496.4 1641.36   516.2 1640.84   605.6 1640.89   615.5 1641.08   625.4 1641.84
     685 1648.61   694.9 1650.41   704.9 1653.03   744.6  1665.5   754.5 1668.26
   784.3 1674.85   843.8  1686.5   853.8 1688.71   873.6 1693.78   883.5  1696.8
   903.4 1703.85     953 1723.47   992.7 1738.72  1012.6 1747.78    1092 1786.81
#Mann= 3 , 0 , 0
       0      .1       0   516.2    .045       0   605.6      .1       0
Bank Sta=516.2,605.6
XS Rating Curve= 0 ,0
Exp/Cntr=0.3,0.1

Type RM Length L Ch R = 1 ,24599.1 ,901.4,920.9,940.3
XS GIS Cut Line= 3
     1989322.506      418350.084     1989734.855      418707.973
     1990147.205      419065.861
#Sta/Elev= 30
       0 1757.95    89.4 1716.16     129 1698.99   148.9 1691.54   168.8 1684.87
   218.4 1670.01   248.2 1663.18   297.8 1653.04     474 1630.77   486.4 1630.29
   549.2 1630.65   595.6 1630.89   615.5 1631.72   694.9 1643.69   724.7 1645.45
   734.6 1649.08   744.6 1654.33   774.3 1672.09   804.1 1686.95   863.7 1713.11
   923.2 1737.85     953 1746.58   982.8 1753.02  1002.6 1757.92  1012.6 1760.92
  1022.5 1764.63  1032.4 1769.64  1042.4 1776.39  1082.1 1812.86    1092 1821.22
#Mann= 3 , 0 , 0
       0      .1       0     474    .045       0   549.2      .1       0
Bank Sta=474,549.2
XS Rating Curve= 0 ,0
Exp/Cntr=0.3,0.1

Type RM Length L Ch R = 1 ,23678.2 ,858.3,852.1,845.9
XS GIS Cut Line= 3
     1988889.017      418672.295     1989022.315      419068.825
     1989017.269      419790.646
#Sta/Elev= 30
       0 1804.18    29.9 1784.66    39.8 1779.22    89.6 1756.28   169.3  1716.7
     239 1683.84   318.7 1648.96   328.7 1646.41   368.5 1646.62   408.4 1644.84
   418.3 1643.05   467.8 1627.94   477.7 1625.93   492.7 1624.89   497.4 1624.78
   576.6 1625.02   596.3 1626.13   616.1 1628.38     715 1641.53   764.4 1652.12
   853.4 1674.19     893 1684.82   932.5 1696.44     982 1713.71  1021.5 1728.56
    1071  1749.5  1080.8 1754.66  1090.7  1762.4  1120.4 1790.61  1140.2 1808.27
#Mann= 3 , 0 , 0
       0      .1       0   492.7    .045       0   576.6      .1       0
Bank Sta=492.7,576.6
XS Rating Curve= 0 ,0
Exp/Cntr=0.3,0.1

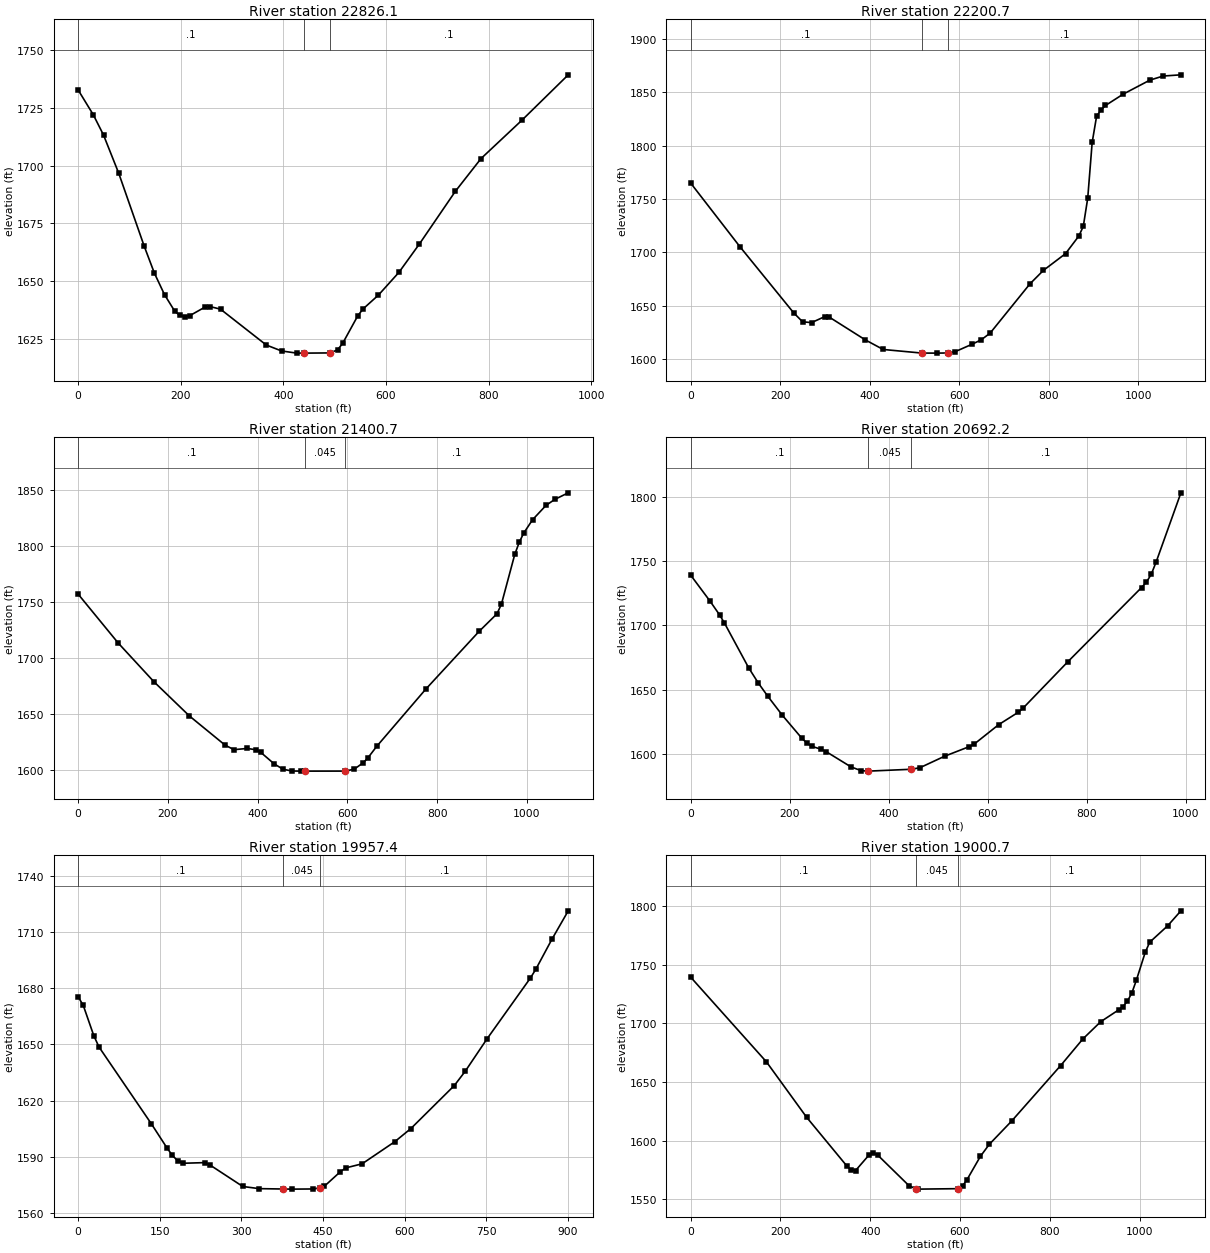
Type RM Length L Ch R = 1 ,22826.1 ,627.9,625.3,623.3
XS GIS Cut Line= 3
     1988068.914      418847.224     1988213.212      419372.883
     1988259.594       419780.01
#Sta/Elev= 30
       0 1732.76    29.7 1721.97    49.6 1713.22    79.3 1696.64   128.8 1665.18
   148.7 1653.48   168.5 1644.15   188.3 1637.04   198.2 1635.19   208.1  1634.7
     218 1635.14   247.8 1638.86   257.7 1638.99   277.5  1637.9   366.7 1622.39
   396.4 1619.83   426.2 1618.89   440.2 1618.89   490.4 1618.98   505.5 1620.29
   515.4  1623.1   545.1  1635.1   555.1 1637.98   585.1 1643.98   625.1 1653.83
     665  1666.1     735 1688.87     785 1703.03   864.9 1719.66   954.9 1739.24
#Mann= 3 , 0 , 0
       0      .1       0   440.2    .045       0   490.4      .1       0
Bank Sta=440.2,490.4
XS Rating Curve= 0 ,0
Exp/Cntr=0.3,0.1

Type RM Length L Ch R = 1 ,22200.7 ,798.3,800,801.1
XS GIS Cut Line= 3
     1987402.674       418999.18     1987608.192      419509.033
     1987800.187       420019.15
#Sta/Elev= 30
       0 1764.94   109.9 1705.31   229.9  1643.3   249.9 1634.86   269.9 1634.11
   299.8 1639.81   309.8 1639.18   389.8 1617.94   429.8 1608.91   515.8 1605.54
   549.7 1605.48   574.8 1605.64   589.4 1606.61     629 1613.94   648.8 1617.98
   668.6 1624.18   757.8 1670.52   787.6 1683.05   837.1  1698.8   866.8  1715.3
   876.8 1724.39   886.7 1750.86   896.6 1803.09   906.5 1827.69   916.4 1833.58
   926.3 1837.76   965.9 1848.42  1025.4 1861.54  1055.1  1865.4  1094.8 1866.53
#Mann= 3 , 0 , 0
       0      .1       0   515.8    .045       0   574.8      .1       0
Bank Sta=515.8,574.8
XS Rating Curve= 0 ,0
Exp/Cntr=0.3,0.1

Type RM Length L Ch R = 1 ,21400.7 ,713.1,708.4,703.8
XS GIS Cut Line= 3
      1986681.56      419236.632     1986848.433      419756.506
     1987015.307       420276.38
#Sta/Elev= 30
       0 1756.99    89.4 1713.26   168.8 1678.78   248.2 1648.08   327.6 1622.06
   347.4 1618.05   377.2 1619.13   397.1 1617.89     407 1615.65   436.8 1605.39
   456.6 1600.56   476.5 1598.99   496.4 1598.88   504.5 1598.88   595.6 1598.91
   615.5 1600.69   635.4 1606.42   645.3  1610.5   665.1 1620.88   774.3 1671.92
   893.4 1723.64   933.2 1739.33   943.1 1747.88   972.9  1792.4   982.8 1803.12
   992.7 1811.33  1012.6 1823.34  1042.4 1836.09  1062.2  1841.5    1092 1847.33
#Mann= 3 , 0 , 0
       0      .1       0   504.5    .045       0   595.6      .1       0
Bank Sta=504.5,595.6
XS Rating Curve= 0 ,0
Exp/Cntr=0.3,0.1

Type RM Length L Ch R = 1 ,20692.2 ,741.5,734.9,728.2
XS GIS Cut Line= 3
     1986007.507      419671.787     1986105.424      419862.467
     1986488.973      420537.033
#Sta/Elev= 30
       0 1738.99      39 1718.87    58.5 1708.07    68.2  1701.8   116.9 1667.18
   136.4 1655.33   155.9 1644.88   185.1 1630.21   224.3 1612.44   234.2 1608.77
   244.2 1606.14   264.1 1603.73     274 1601.87   323.8  1590.1   343.7 1587.27
   358.8 1586.82   445.9 1588.27   463.1 1589.48   512.8 1598.37   562.6 1605.83
   572.5 1607.75   622.2 1622.93     662  1632.6     672 1635.96   761.5 1671.62
   910.8 1729.41   920.7 1733.61   930.6 1739.86   940.6 1749.61   990.3 1802.96
#Mann= 3 , 0 , 0
       0      .1       0   358.8    .045       0   445.9      .1       0
Bank Sta=358.8,445.9
XS Rating Curve= 0 ,0
Exp/Cntr=0.3,0.1

Type RM Length L Ch R = 1 ,19957.4 ,961.8,956.7,951.5
XS GIS Cut Line= 3
     1985389.085      420207.752     1985486.498      420362.613
     1986006.793      420856.459
#Sta/Elev= 30
       0 1675.54     9.6 1670.82    28.9 1654.71    38.5 1648.65   134.8 1607.64
   163.7 1594.69   173.3 1590.84     183 1588.01   192.9 1586.68   232.8 1587.02
   242.7 1585.68   302.5 1574.31   332.4 1573.15   376.8 1572.95   392.2 1572.89
     432 1572.98   445.1  1573.6     452 1574.32   481.8 1582.18   491.8 1584.22
   521.7 1586.38   581.5 1598.13   611.4 1605.21   691.1 1628.13     711 1635.69
   750.8 1652.86   830.6 1685.35   840.5 1689.98   870.4 1706.14   900.3 1721.26
#Mann= 3 , 0 , 0
       0      .1       0   376.8    .045       0   445.1      .1       0
Bank Sta=376.8,445.1
XS Rating Curve= 0 ,0
Exp/Cntr=0.3,0.1

Type RM Length L Ch R = 1 ,19000.7 ,682.3,675.4,668.5
XS GIS Cut Line= 3
     1984745.036      421069.973     1985215.342      421347.333
     1985685.649      421624.692
#Sta/Elev= 30
       0 1739.28   168.8 1667.11   258.1 1620.02   347.4 1578.66   357.4 1575.17
   367.3 1574.61   397.1 1587.77     407  1589.5     417  1587.6   486.4 1561.64
   502.8 1558.98   506.3 1558.76   595.6 1559.15   605.6 1561.54   615.5 1566.81
   645.3 1586.66   665.1 1596.89   714.8 1616.68     824 1663.97   873.6 1686.68
   913.3 1701.36     953 1711.36     963 1714.31   972.9 1718.86   982.8 1725.94
   992.7 1736.61  1012.6 1760.57  1022.5 1769.09  1062.2 1782.95    1092 1795.82
#Mann= 3 , 0 , 0
       0      .1       0   502.8    .045       0   595.6      .1       0
Bank Sta=502.8,595.6
XS Rating Curve= 0 ,0
Exp/Cntr=0.3,0.1

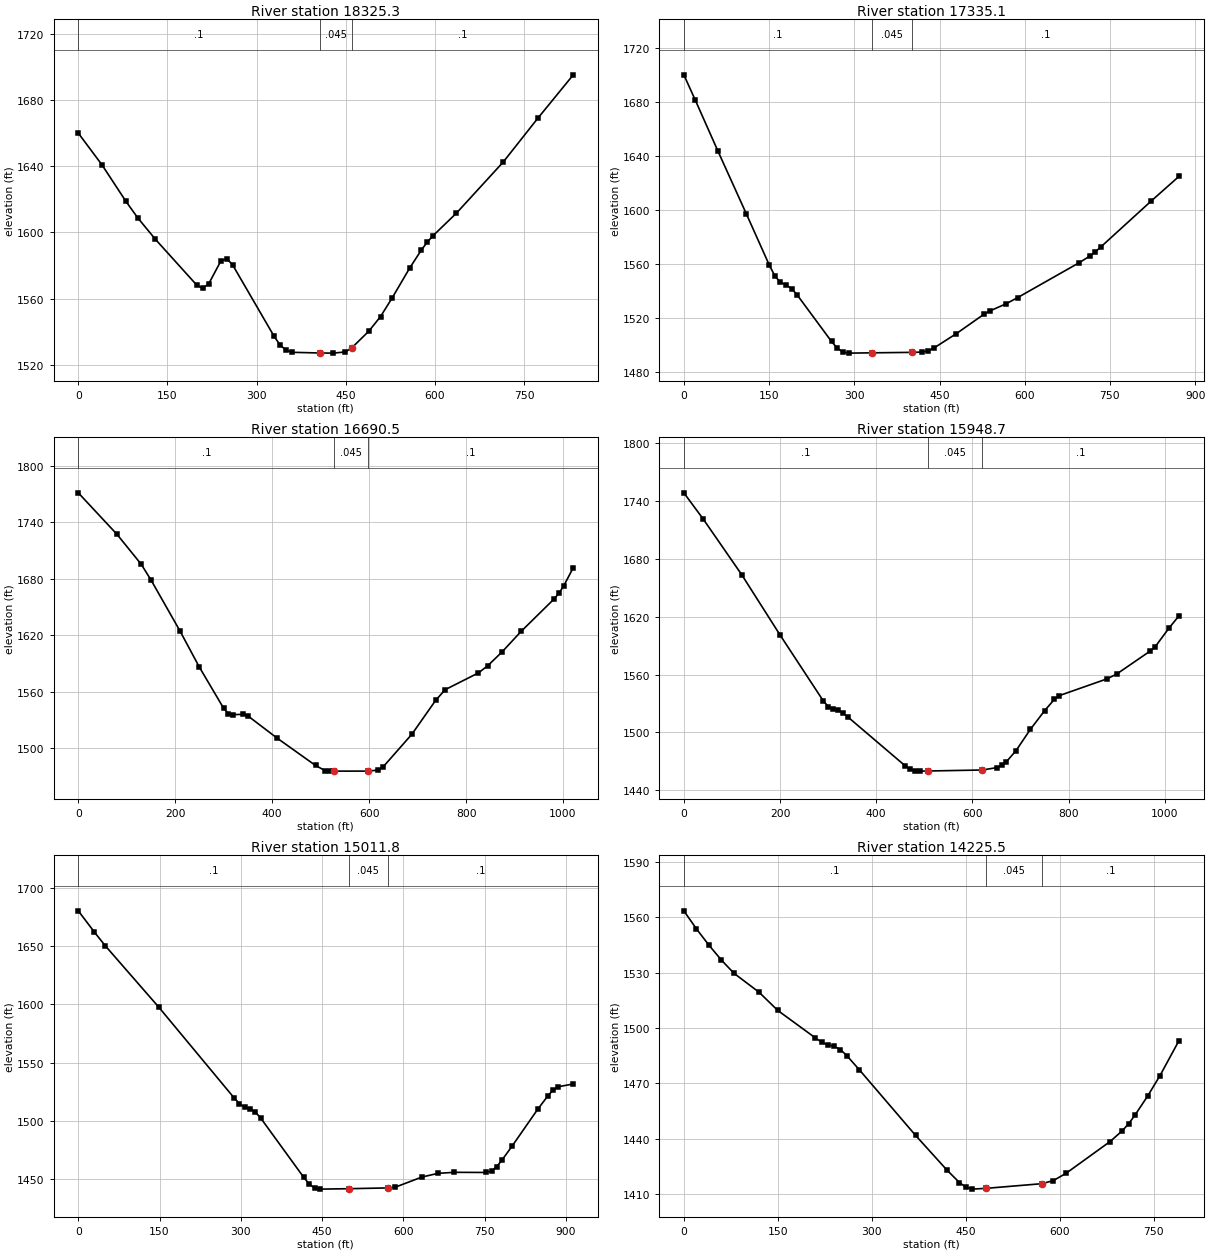
Type RM Length L Ch R = 1 ,18325.3 ,994.2,990.2,986.2
XS GIS Cut Line= 3
     1984554.216      421867.185     1985020.923       421974.69
     1985372.337      422014.704
#Sta/Elev= 30
       0 1659.96    39.9 1640.76    79.8  1618.9    99.8 1608.86   129.7 1595.81
   199.6    1568   209.5  1566.2   219.5 1569.02   239.5  1582.5   249.4  1584.2
   259.4 1580.48   329.3 1537.24   339.2 1532.07   349.2 1528.85   359.2 1527.55
   406.3 1527.13     429 1527.05     449 1527.77   459.8 1530.15   488.8 1540.36
   508.4 1549.15     528 1560.43   557.5  1578.5   577.2  1589.4     587 1594.12
   596.8 1598.02   636.1 1611.64   714.7 1642.47   773.7 1669.28   832.6 1695.17
#Mann= 3 , 0 , 0
       0      .1       0   406.3    .045       0   459.8      .1       0
Bank Sta=406.3,459.8
XS Rating Curve= 0 ,0
Exp/Cntr=0.3,0.1

Type RM Length L Ch R = 1 ,17335.1 ,643.2,644.6,646.1
XS GIS Cut Line= 3
     1984243.716      422826.383     1984722.949      422850.459
     1985113.372      422822.518
#Sta/Elev= 30
       0 1700.48      20 1681.87      60 1643.95     110 1597.44     150 1559.83
     160 1551.53   169.9 1546.66   179.9 1544.74   189.9 1542.01   199.9 1537.08
   259.9 1502.86   269.9 1497.95   279.9    1495   289.9  1494.2   330.4 1494.42
     401 1494.76   419.9 1494.99   429.8  1495.9   439.8 1497.88   479.8 1508.69
   528.8 1523.18   538.6 1525.45   567.9 1530.91   587.5 1535.35   695.1 1561.03
   714.7 1566.16   724.5 1569.38   734.3 1573.03   822.3 1606.81   871.3 1625.12
#Mann= 3 , 0 , 0
       0      .1       0   330.4    .045       0     401      .1       0
Bank Sta=330.4,401
XS Rating Curve= 0 ,0
Exp/Cntr=0.3,0.1

Type RM Length L Ch R = 1 ,16690.5 ,721.4,741.8,762.1
XS GIS Cut Line= 3
     1984104.571      423417.749     1984750.049      423487.321
     1985121.103      423514.377
#Sta/Elev= 30
       0 1771.25    79.9 1727.14   129.8 1695.43   149.8 1678.92   209.8  1624.6
   249.7 1586.28   299.6 1542.77   309.6 1536.85   319.6 1535.75   339.6 1536.13
   349.6 1534.56   409.5 1511.12   489.4 1481.84   509.4  1476.3   519.4 1475.82
     528 1475.83   597.4 1475.84   619.2 1476.95   629.2  1480.5   688.4 1515.11
   737.3 1550.98   756.9 1562.29   825.4 1580.06     845 1587.82   874.4 1602.44
   913.6 1624.17   982.1 1658.82   991.9 1664.91  1001.7 1672.74  1021.2 1691.82
#Mann= 3 , 0 , 0
       0      .1       0     528    .045       0   597.4      .1       0
Bank Sta=528,597.4
XS Rating Curve= 0 ,0
Exp/Cntr=0.3,0.1

Type RM Length L Ch R = 1 ,15948.7 ,944.5,936.9,929.3
XS GIS Cut Line= 3
     1984033.555       423542.46     1984378.996      424094.148
     1984579.983      424414.954
#Sta/Elev= 30
       0 1748.66    40.1 1721.58   120.2 1663.84   200.3 1600.99   290.4 1532.49
   300.4  1526.9   310.4 1524.15   320.4 1522.91   330.5  1520.3   340.5 1516.36
   460.6  1465.3   470.7  1461.9   480.7 1460.26   490.7 1459.91     508 1460.05
   620.9 1461.08   650.9 1463.55   660.9  1465.8   670.8 1469.61   690.8 1481.16
   720.6 1503.15   750.5 1522.75   770.5 1534.28   780.4 1538.18     880 1555.63
     900 1560.57   969.7 1584.42   979.7 1588.56  1009.6 1608.68  1029.5 1620.86
#Mann= 3 , 0 , 0
       0      .1       0     508    .045       0   620.9      .1       0
Bank Sta=508,620.9
XS Rating Curve= 0 ,0
Exp/Cntr=0.3,0.1

Type RM Length L Ch R = 1 ,15011.8 ,786,786.3,786.6
XS GIS Cut Line= 3
     1983310.448      424372.525     1983907.449       424847.85
     1984019.538      424948.343
#Sta/Elev= 30
       0 1680.31    29.7 1662.05    49.6 1650.41   148.7 1597.49   287.4 1519.76
   297.3 1514.78   307.2 1511.51   317.1 1510.23     327 1507.39     337 1502.12
   416.2 1451.36   426.2 1445.72   436.1 1442.13     446 1441.29   499.5 1441.66
   571.5 1442.33   584.7  1442.9   634.3 1451.67     664 1454.84   693.7 1455.72
   753.2 1455.59   763.1 1456.98   772.5 1460.67   781.9 1466.13   800.8 1478.28
   847.8 1509.73   866.6 1521.25     876 1526.25   885.4 1529.17   913.7  1531.6
#Mann= 3 , 0 , 0
       0      .1       0   499.5    .045       0   571.5      .1       0
Bank Sta=499.5,571.5
XS Rating Curve= 0 ,0
Exp/Cntr=0.3,0.1

Type RM Length L Ch R = 1 ,14225.5 ,801,776.6,752.2
XS GIS Cut Line= 3
      1982824.66      424862.696      1983072.58      425176.386
      1983374.06      425423.755
#Sta/Elev= 30
       0 1563.44      20  1553.7      40 1544.83      60 1536.71      80 1529.57
     120 1519.31   149.9 1509.42   209.9 1494.54   219.9 1492.25   229.9  1490.7
   239.9 1490.02   249.9 1488.21   259.9 1484.97   279.9  1477.3   369.8 1441.67
   419.8 1422.88   439.8 1416.11   449.8 1413.64   459.8 1412.56   482.5 1412.99
   571.6 1415.52   589.8 1417.23   609.8 1421.13   679.8 1438.29   699.8 1444.26
   709.8 1448.06   719.8 1452.68   739.8 1462.89   759.8 1474.16   789.8 1492.94
#Mann= 3 , 0 , 0
       0      .1       0   482.5    .045       0   571.6      .1       0
Bank Sta=482.5,571.6
XS Rating Curve= 0 ,0
Exp/Cntr=0.3,0.1

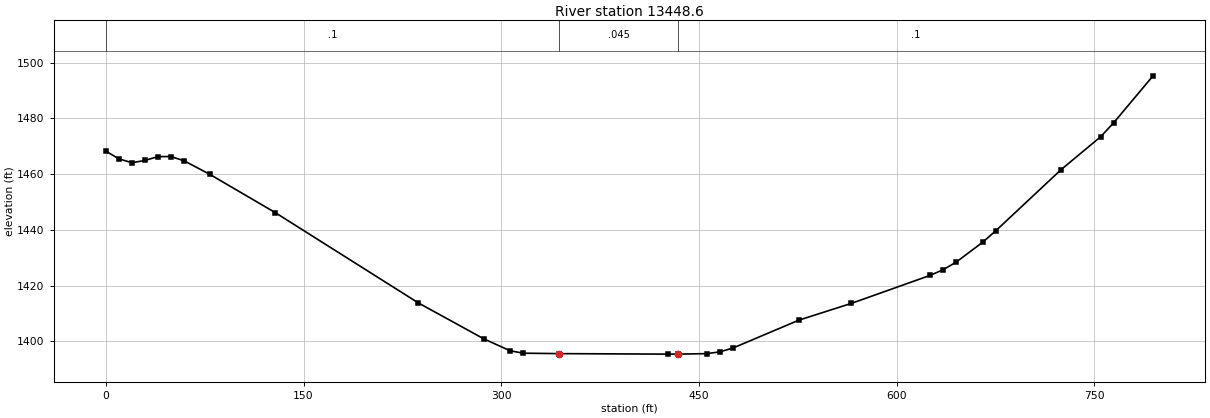
Type RM Length L Ch R = 1 ,13448.6 ,742.1,733.3,724.5
XS GIS Cut Line= 3
     1982597.168      426177.457      1982786.56      426018.986
     1983292.893      425810.269
#Sta/Elev= 30
       0 1468.23     9.9 1465.46    19.8 1464.08    29.6  1464.9    39.5 1466.28
    49.4 1466.29    59.3 1464.78      79 1459.87   128.4 1446.22   237.1  1413.8
   286.8  1400.9   306.7 1396.64   316.6 1395.77   343.6 1395.61   426.2 1395.43
   434.3 1395.44     456  1395.6     466 1396.26     476 1397.65   525.8 1407.61
   565.6 1413.62   625.3 1423.65   635.3  1425.7   645.2 1428.43   665.2 1435.53
   675.1  1439.6   724.9 1461.64   754.8 1473.38   764.7 1478.41   794.6 1495.25
#Mann= 3 , 0 , 0
       0      .1       0   343.6    .045       0   434.3      .1       0
Bank Sta=343.6,434.3
XS Rating Curve= 0 ,0
Exp/Cntr=0.3,0.1