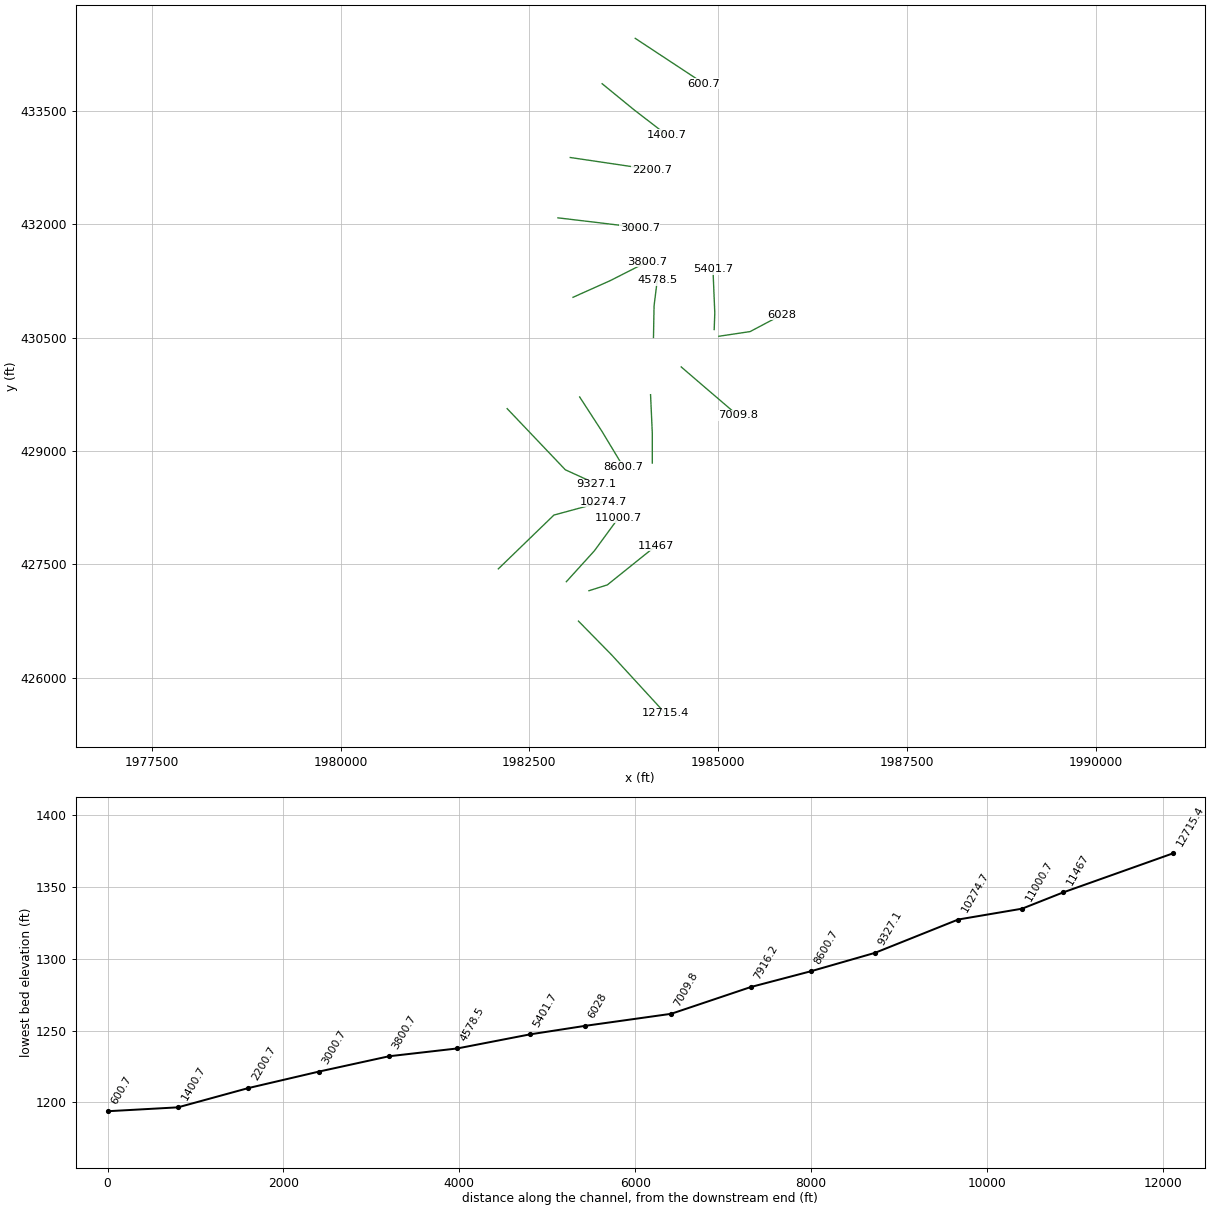
HEC-RAS study MeadowRvr.prj: MeadowRvr

--- MeadowRvr.g01 (geometry) --- (continued)

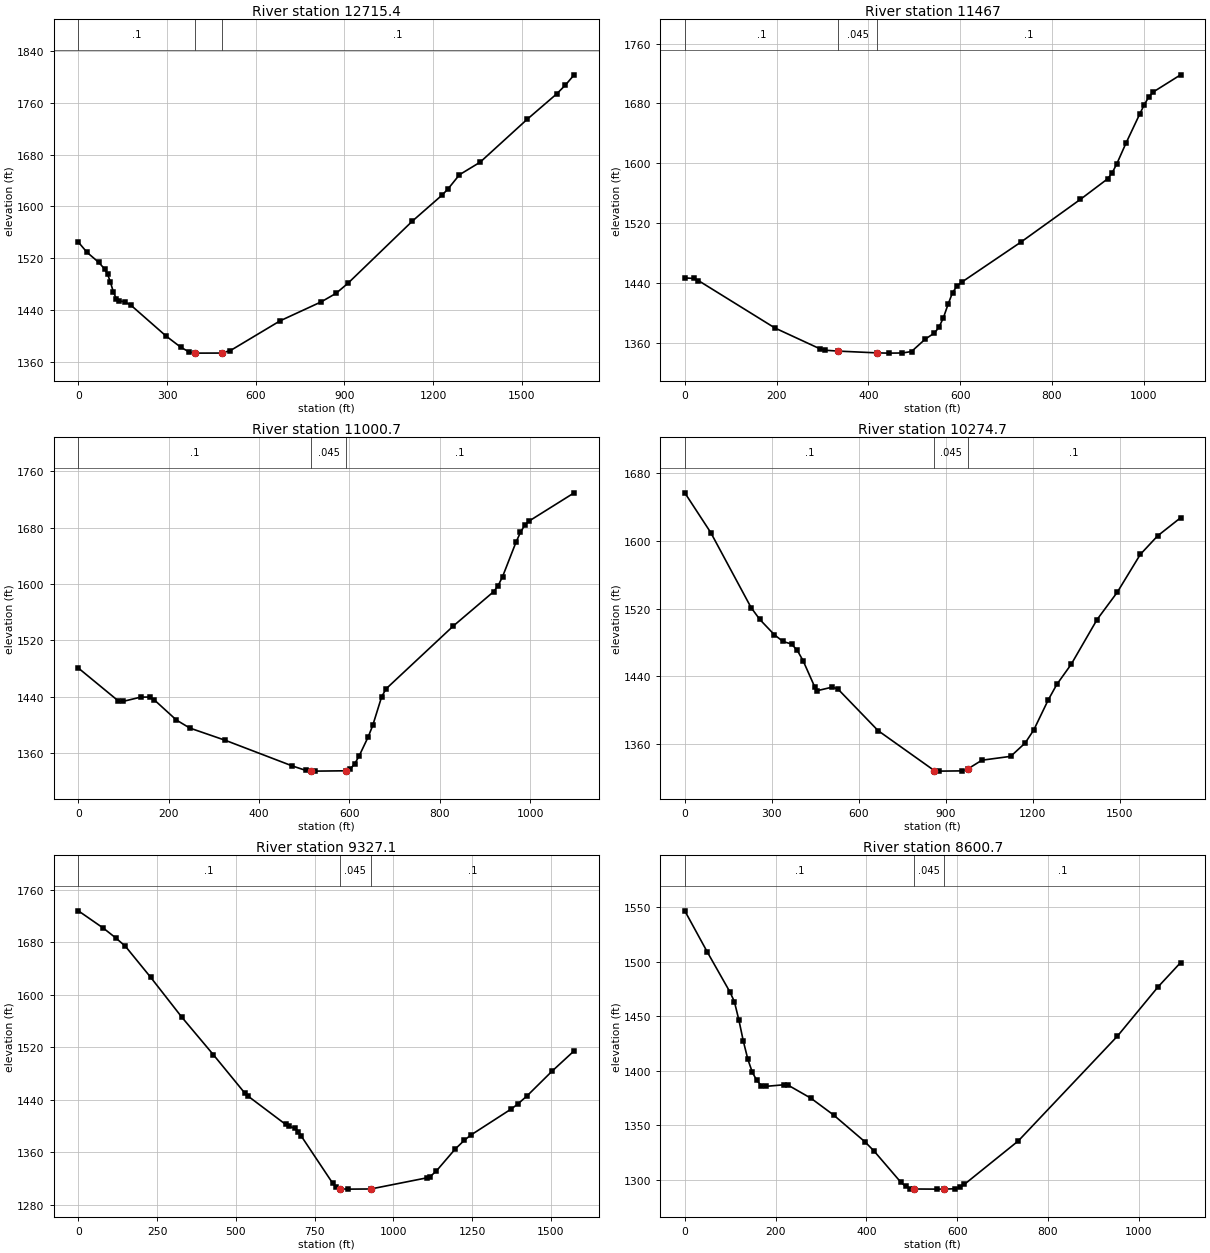
Type RM Length L Ch R = 1 ,12715.4 ,1215.2,1248.3,1281.3
XS GIS Cut Line= 3
     1983149.883      426749.497     1983586.643      426305.006
     1984299.792       425528.73
#Sta/Elev= 30
       0 1544.86    29.7 1528.93    69.2 1513.51      89  1503.3    98.9  1495.4
   108.8 1482.61   118.7 1467.55   128.6 1457.44   138.5 1454.35   158.3 1452.18
     178 1447.35   296.7 1399.78   346.2  1382.6   375.9  1374.8   395.7 1373.35
   484.7 1373.46   514.4 1377.28   682.8 1423.32     822 1452.64   871.8 1465.74
   911.6 1481.05  1130.3 1577.46  1229.8 1617.23  1249.7 1626.57  1289.4    1649
  1359.1 1668.31  1518.2 1734.56  1617.6 1773.62  1647.5 1787.38  1677.3 1803.34
#Mann= 3 , 0 , 0
       0      .1       0   395.7    .045       0   484.7      .1       0
Bank Sta=395.7,484.7
XS Rating Curve= 0 ,0
Exp/Cntr=0.3,0.1

Type RM Length L Ch R = 1 ,11467   ,462.7,466.3,472.3
XS GIS Cut Line= 3
     1983289.027      427151.471     1983532.531      427228.774
      1984175.72      427745.095
#Sta/Elev= 30
       0  1446.7    19.6 1446.01    29.5 1443.19   196.5 1379.73   295.2 1351.74
   305.2 1350.09   334.5 1348.87   419.4 1346.49   444.3 1346.18   474.1 1346.36
     494 1348.34   523.8 1364.86   543.7 1372.99   553.6 1380.55   563.5 1393.57
   573.5 1411.24   583.4 1427.13   593.4 1436.05   603.3 1441.01   732.5 1494.65
   861.6 1551.55   921.3 1579.16   931.2 1587.28   941.2 1599.12     961 1626.49
   990.8 1665.24  1000.8 1677.86  1010.7 1688.36  1020.6 1695.22  1080.3 1718.16
#Mann= 3 , 0 , 0
       0      .1       0   334.5    .045       0   419.4      .1       0
Bank Sta=334.5,419.4
XS Rating Curve= 0 ,0
Exp/Cntr=0.3,0.1

Type RM Length L Ch R = 1 ,11000.7 ,727.5,725.9,722.1
XS GIS Cut Line= 3
     1982989.662      427270.797     1983360.963      427679.818
     1983683.178      428119.203
#Sta/Elev= 30
       0 1480.94    88.8 1434.18    98.6  1433.6   138.1 1439.73   157.8 1439.84
   167.7 1436.02     217 1407.29   246.6 1395.93   325.5 1378.49   473.5 1342.24
   503.1 1335.97   515.3    1335   522.8 1334.88     592 1335.36     602 1337.98
   611.9 1345.53   621.8 1356.84   641.6 1383.58   651.5 1399.54   671.3 1440.28
   681.2 1451.56   829.8 1540.48     919 1589.05   928.9 1597.49   938.8 1610.33
   968.5 1659.03   978.4 1673.12   988.3 1683.69   998.2 1689.46  1097.3 1729.17
#Mann= 3 , 0 , 0
       0      .1       0   515.3    .045       0     592      .1       0
Bank Sta=515.3,592
XS Rating Curve= 0 ,0
Exp/Cntr=0.3,0.1

Type RM Length L Ch R = 1 ,10274.7 ,983.4,947.6,911.9
XS GIS Cut Line= 3
     1982089.066      427440.556     1982825.211      428152.542
     1983486.461      428331.314
#Sta/Elev= 30
       0 1657.09    89.5 1609.96   228.7 1521.01   258.5 1507.07   308.2 1489.11
   338.1 1481.02   367.9  1477.9   387.8 1470.36   407.7 1458.23   447.4 1427.46
   457.4 1422.72   507.1 1426.78     527  1424.9   666.2 1375.34   860.6 1327.84
     875 1327.34   954.5 1327.63   975.4  1329.9  1024.1 1340.28  1123.4 1344.85
    1173 1360.57  1202.8 1376.03  1252.5 1411.54  1282.2 1430.01  1331.9  1453.9
  1421.2 1506.99  1490.7 1539.26  1570.1 1584.09  1629.7 1606.05  1709.1 1627.57
#Mann= 3 , 0 , 0
       0      .1       0   860.6    .045       0   975.4      .1       0
Bank Sta=860.6,975.4
XS Rating Curve= 0 ,0
Exp/Cntr=0.3,0.1

Type RM Length L Ch R = 1 ,9327.1  ,730.6,726.4,721.5
XS GIS Cut Line= 3
     1982206.088      429560.343     1982975.951      428751.638
     1983392.329      428561.558
#Sta/Elev= 30
       0 1727.63    79.8 1701.14   119.6 1686.11   149.5 1673.63   229.3  1626.7
     329 1565.53   428.7 1508.69   528.4 1450.36   538.3 1445.86     658 1402.67
   667.9 1399.94   687.9 1396.72   697.8 1391.65   707.8 1384.88   807.5 1313.15
   817.5 1307.48   830.9 1304.48   857.4 1304.12   928.6 1304.35  1106.6 1321.29
  1116.6 1323.01  1136.4 1331.53  1196.2 1364.91    1226 1378.61  1245.9 1386.27
  1375.3  1426.3  1395.2 1433.59    1425 1446.15  1504.6 1483.84  1574.3  1514.6
#Mann= 3 , 0 , 0
       0      .1       0   830.9    .045       0   928.6      .1       0
Bank Sta=830.9,928.6
XS Rating Curve= 0 ,0
Exp/Cntr=0.3,0.1

Type RM Length L Ch R = 1 ,8600.7  ,696.5,684.5,673.3
XS GIS Cut Line= 3
     1983166.048      429714.591     1983463.293      429256.672
      1983745.26      428788.679
#Sta/Elev= 30
       0 1546.85    49.6 1509.01    99.3 1472.46   109.2 1463.54   119.1 1446.65
     129 1427.08     139  1410.4   148.9 1398.46   158.8  1391.1   168.7 1386.28
   178.7 1385.71   218.4 1387.15   228.3 1386.63   277.9 1374.82   327.6 1359.47
     397 1334.75   416.9 1326.34   476.4 1297.46   486.4 1293.94   496.3 1291.93
   505.4 1291.48   555.9 1291.36   570.9 1291.36   595.6 1291.71   605.5 1293.09
   615.5 1295.61   734.7 1335.62   953.2 1431.88  1042.6 1477.04  1092.3 1499.36
#Mann= 3 , 0 , 0
       0      .1       0   505.4    .045       0   570.9      .1       0
Bank Sta=505.4,570.9
XS Rating Curve= 0 ,0
Exp/Cntr=0.3,0.1

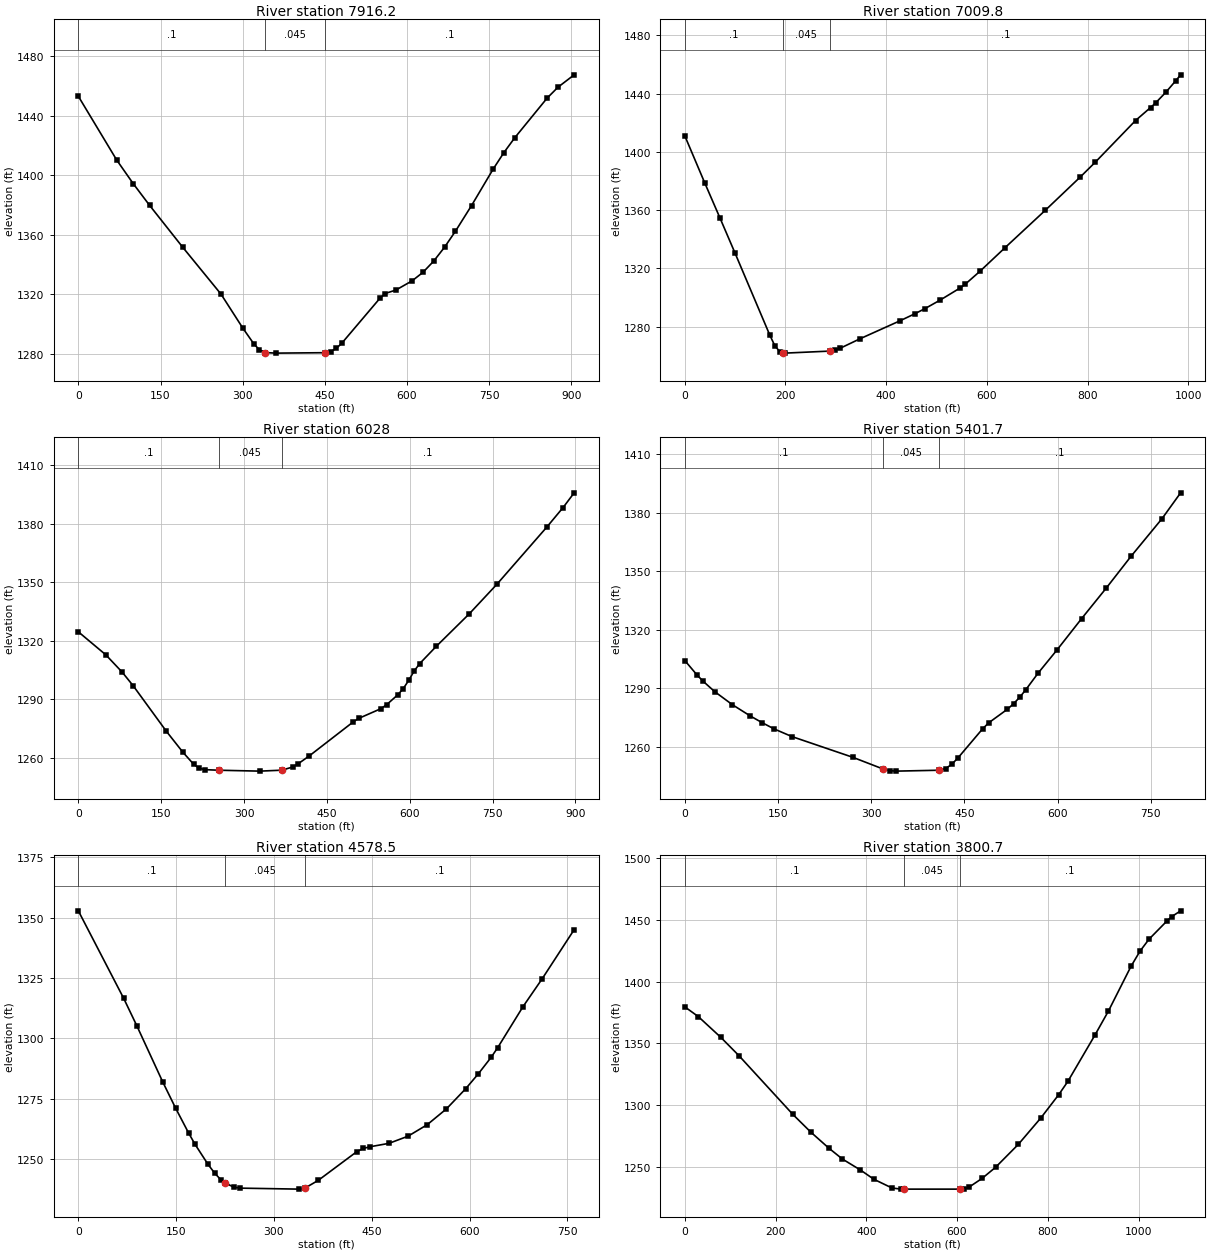
Type RM Length L Ch R = 1 ,7916.2  ,887.7,906.3,924.9
XS GIS Cut Line= 3
     1984104.571      429744.979     1984127.762      429234.781
     1984127.762      428840.537
#Sta/Elev= 30
       0 1453.14    70.1 1410.21   100.1 1394.41   130.2  1379.7   190.3 1351.69
   260.4 1320.05   300.4  1297.1   320.4 1286.56   330.5 1282.59   341.3 1280.73
   360.5 1280.36   450.6 1280.65   460.6 1281.41   470.7  1283.5   480.7 1286.94
   550.2 1317.14     560 1320.46   579.7 1322.81   609.3    1329     629  1334.7
   648.7 1342.29   668.4 1351.59   688.1 1362.24   717.7 1379.62   757.1 1404.12
   776.8 1415.28   796.6 1425.24   855.7 1451.92   875.4 1459.21     905 1467.56
#Mann= 3 , 0 , 0
       0      .1       0   341.3    .045       0   450.6      .1       0
Bank Sta=341.3,450.6
XS Rating Curve= 0 ,0
Exp/Cntr=0.3,0.1

Type RM Length L Ch R = 1 ,7009.8  ,962.4,981.8,1001.3
XS GIS Cut Line= 3
     1984510.411      430112.167     1984811.892      429853.202
     1985258.525      429471.519
#Sta/Elev= 30
       0 1411.01    39.7 1378.59    69.6 1354.77    99.4 1330.76   168.9 1274.04
   178.8 1266.82   188.8 1262.66   194.2 1262.14   198.7 1261.71   288.8 1263.12
   298.1 1263.72     308 1264.96   347.8 1271.53   427.3  1283.9   457.2 1288.79
   477.1  1292.3     507  1298.1   546.8 1306.45   556.8 1308.98   586.6 1318.03
   636.4 1334.24   716.1 1359.84   785.8 1382.78   815.7 1392.99   895.3 1421.49
   925.2 1430.44   935.2  1433.6   955.1 1440.76     975 1448.74   984.9  1452.9
#Mann= 3 , 0 , 0
       0      .1       0   194.2    .045       0   288.8      .1       0
Bank Sta=194.2,288.8
XS Rating Curve= 0 ,0
Exp/Cntr=0.3,0.1

Type RM Length L Ch R = 1 ,6028    ,593.2,626.3,659.4
XS GIS Cut Line= 3
     1985009.014      430518.006     1985422.583      430579.848
     1985846.453      430803.876
#Sta/Elev= 30
       0 1324.65    49.8 1312.85    79.6 1303.92    99.6 1296.91   159.3 1273.73
   189.2 1263.01   209.1 1256.72     219 1254.78     229 1254.06     254 1253.76
   328.6  1253.3   368.4 1253.78   388.3 1255.44   398.3 1257.13   418.2 1261.12
   498.1 1278.61   508.1 1280.37     548 1285.32     558 1287.29     578 1292.32
     588 1295.48     598 1299.72   607.9 1304.55   617.9 1308.35   647.9 1317.18
   707.8 1333.88   757.8 1349.02   847.7 1378.16   877.6 1388.31   897.6 1395.83
#Mann= 3 , 0 , 0
       0      .1       0     254    .045       0   368.4      .1       0
Bank Sta=254,368.4
XS Rating Curve= 0 ,0
Exp/Cntr=0.3,0.1

Type RM Length L Ch R = 1 ,5401.7  ,824.6,823.2,821.9
XS GIS Cut Line= 3
     1984947.171      430606.904     1984954.902      430827.217
     1984930.848      431404.217
#Sta/Elev= 30
       0 1304.12    19.2 1296.88    28.8 1293.69    47.9 1288.21    76.7 1281.43
   105.4 1275.67   124.6 1272.21   143.8 1269.02   172.5 1265.09   270.2 1254.49
   319.2 1248.45     330 1247.61   339.9 1247.37   409.6 1247.83   419.6 1248.62
   429.5 1250.84   439.5 1254.09   479.3 1269.07   489.3  1272.2   519.2 1279.12
   529.1 1281.94   539.1  1285.3     549 1289.23   568.9 1297.76   598.8 1309.46
   638.6 1325.61   678.5 1341.37   718.3 1357.64   768.1 1376.93     798 1390.16
#Mann= 3 , 0 , 0
       0      .1       0   319.2    .045       0   409.6      .1       0
Bank Sta=319.2,409.6
XS Rating Curve= 0 ,0
Exp/Cntr=0.3,0.1

Type RM Length L Ch R = 1 ,4578.5  ,803.4,777.8,753.3
XS GIS Cut Line= 3
     1984143.223      430502.546     1984150.953       430919.98
      1984193.47      431260.112
#Sta/Elev= 30
       0 1352.88    69.6  1316.6    89.5 1305.38   129.2 1282.14   149.1 1271.19
     169 1260.91   178.9 1256.19   198.8 1247.89   208.8 1244.32   218.7 1241.44
   225.3 1240.15   238.6  1238.4   248.5 1238.02     338 1237.61   347.9 1238.11
   367.8 1241.22   427.3 1253.19   437.1 1254.46   446.9 1255.14   476.3 1256.57
   505.6 1259.54     535  1264.3   564.4 1270.84   593.8 1279.14   613.4 1285.39
     633  1292.2   642.8  1296.1   681.9 1313.21   711.3 1324.75   760.3 1345.09
#Mann= 3 , 0 , 0
       0      .1       0   225.3    .045       0   347.9      .1       0
Bank Sta=225.3,347.9
XS Rating Curve= 0 ,0
Exp/Cntr=0.3,0.1

Type RM Length L Ch R = 1 ,3800.7  ,812.1,800,786.7
XS GIS Cut Line= 3
     1983077.657      431033.405     1983575.924      431256.315
     1984063.389      431504.075
#Sta/Elev= 30
       0 1379.52    29.8 1371.64    79.4 1354.86   119.1 1340.15   238.2 1292.54
   277.9 1278.18   317.6 1265.25   347.4 1256.47   387.1 1247.61   416.8 1240.11
   456.5  1233.1   476.4 1232.16   483.1 1232.16   605.5 1232.16   615.4 1232.24
   625.4 1233.52   655.2 1240.84     685 1249.86   734.8 1268.26   784.5 1289.64
   824.2 1308.59   844.1 1319.21   903.8 1356.65   933.6 1376.14   983.3 1412.26
  1003.2 1424.56  1023.1 1434.24  1062.8 1449.04  1072.8 1452.42  1092.7 1457.16
#Mann= 3 , 0 , 0
       0      .1       0   483.1    .045       0   605.5      .1       0
Bank Sta=483.1,605.5
XS Rating Curve= 0 ,0
Exp/Cntr=0.3,0.1

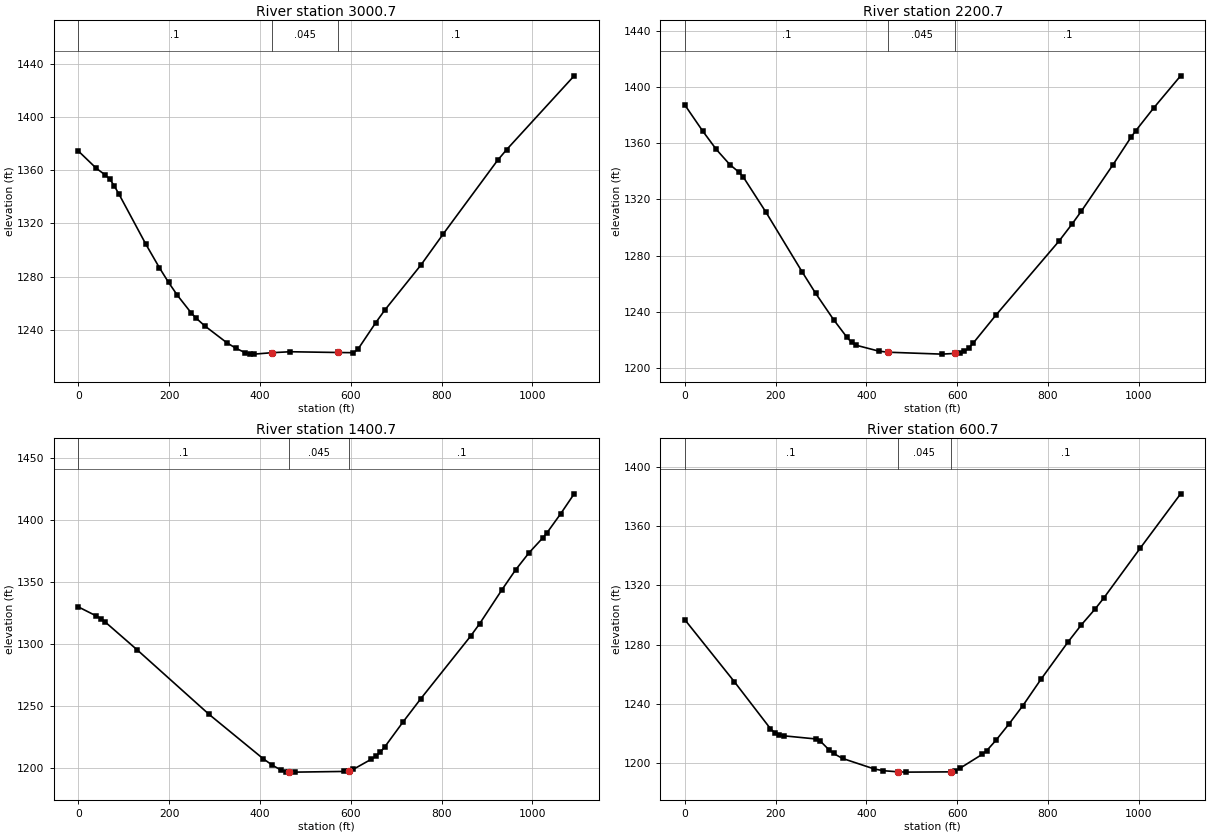
Type RM Length L Ch R = 1 ,3000.7  ,800.6,800,799.4
XS GIS Cut Line= 3
     1982878.562      432084.632     1983420.748      432020.214
     1983962.729      431954.055
#Sta/Elev= 30
       0 1374.66    39.7 1361.58    59.6 1356.51    69.5 1353.38    79.4 1348.19
    89.4 1342.19   148.9 1304.24   178.7 1286.52   198.6 1275.63   218.4 1265.71
   248.2 1252.71   258.1 1249.02     278 1242.88   327.6  1229.9   347.4 1225.84
   367.3 1222.53   377.2 1221.61   387.2 1221.45   426.5 1222.53   466.6 1223.25
     571 1222.68   605.6 1222.53   615.5 1224.98   655.2 1245.26     675  1254.7
   754.5 1288.66   804.1  1312.3   923.2 1367.59   943.1 1375.64    1092 1431.37
#Mann= 3 , 0 , 0
       0      .1       0   426.5    .045       0     571      .1       0
Bank Sta=426.5,571
XS Rating Curve= 0 ,0
Exp/Cntr=0.3,0.1

Type RM Length L Ch R = 1 ,2200.7  ,812.2,800,788.5
XS GIS Cut Line= 3
     1983041.287      432882.929     1983581.425      432803.135
     1984121.563      432723.342
#Sta/Elev= 30
       0 1387.23    39.7 1368.54    69.5 1355.55    99.3 1344.76   119.1 1339.46
     129 1335.86   178.7 1310.98   258.1 1268.69   287.9 1253.39   327.6 1234.58
   357.4 1221.87   367.3 1218.36   377.2 1216.36   426.9 1212.18   447.6 1211.38
   565.8 1210.02   595.6 1210.52   605.6 1210.93   615.5 1211.94   625.4 1214.34
   635.4 1217.95     685 1237.69     824 1290.34   853.8 1302.91   873.6 1311.81
   943.1 1344.74   982.8 1364.29   992.7 1368.68  1032.4 1384.96    1092 1407.93
#Mann= 3 , 0 , 0
       0      .1       0   447.6    .045       0   595.6      .1       0
Bank Sta=447.6,595.6
XS Rating Curve= 0 ,0
Exp/Cntr=0.3,0.1

Type RM Length L Ch R = 1 ,1400.7  ,797.7,800,801.6
XS GIS Cut Line= 3
     1983463.595      433859.022     1983886.622      433513.368
     1984319.355      433180.497
#Sta/Elev= 30
       0 1330.08    39.7 1322.75    49.7 1320.62    59.6 1317.75   129.1 1295.54
     288 1243.26   407.2 1207.45   427.1 1202.26     447 1198.17   456.9 1196.99
     465  1196.7   476.8 1196.61     586 1197.17   595.9 1197.63   605.8  1198.9
   645.6 1207.08   655.5 1209.59   665.4 1212.84   675.3 1217.14     715 1237.01
   754.7 1256.07   863.9 1306.37   883.8  1316.4   933.4 1344.08   963.2    1360
     993 1373.89  1022.8 1385.72  1032.7 1390.13  1062.5 1405.32  1092.2 1421.42
#Mann= 3 , 0 , 0
       0      .1       0     465    .045       0   595.9      .1       0
Bank Sta=465,595.9
XS Rating Curve= 0 ,0
Exp/Cntr=0.3,0.1

Type RM Length L Ch R = 1 ,600.7   ,597,600.7,604.3
XS GIS Cut Line= 3
     1983901.338       434459.53     1984357.342      434159.235
     1984813.345       433858.94
#Sta/Elev= 30
       0 1296.84   109.2 1254.93   188.6 1223.25   198.6 1220.27   208.5 1218.93
   218.4 1218.41   287.9 1216.32   297.8 1215.04   317.7 1208.94   327.6 1206.49
   347.4 1203.15     417 1196.06   436.8 1194.87   468.8 1194.13   486.4  1193.9
   585.7 1194.08   595.6 1194.82   605.6 1196.44   655.2 1205.94   665.1 1208.48
     685  1215.3   714.8 1226.71   744.6 1238.82   784.2  1256.5   843.8 1281.71
   873.6 1293.45   903.4 1303.95   923.2 1311.65  1002.6 1344.97    1092 1381.83
#Mann= 3 , 0 , 0
       0      .1       0   468.8    .045       0   585.7      .1       0
Bank Sta=468.8,585.7
XS Rating Curve= 0 ,0
Exp/Cntr=0.3,0.1

Chan Stop Cuts=-1
Use User Specified Reach Order=0
Composite Channel Slope=5